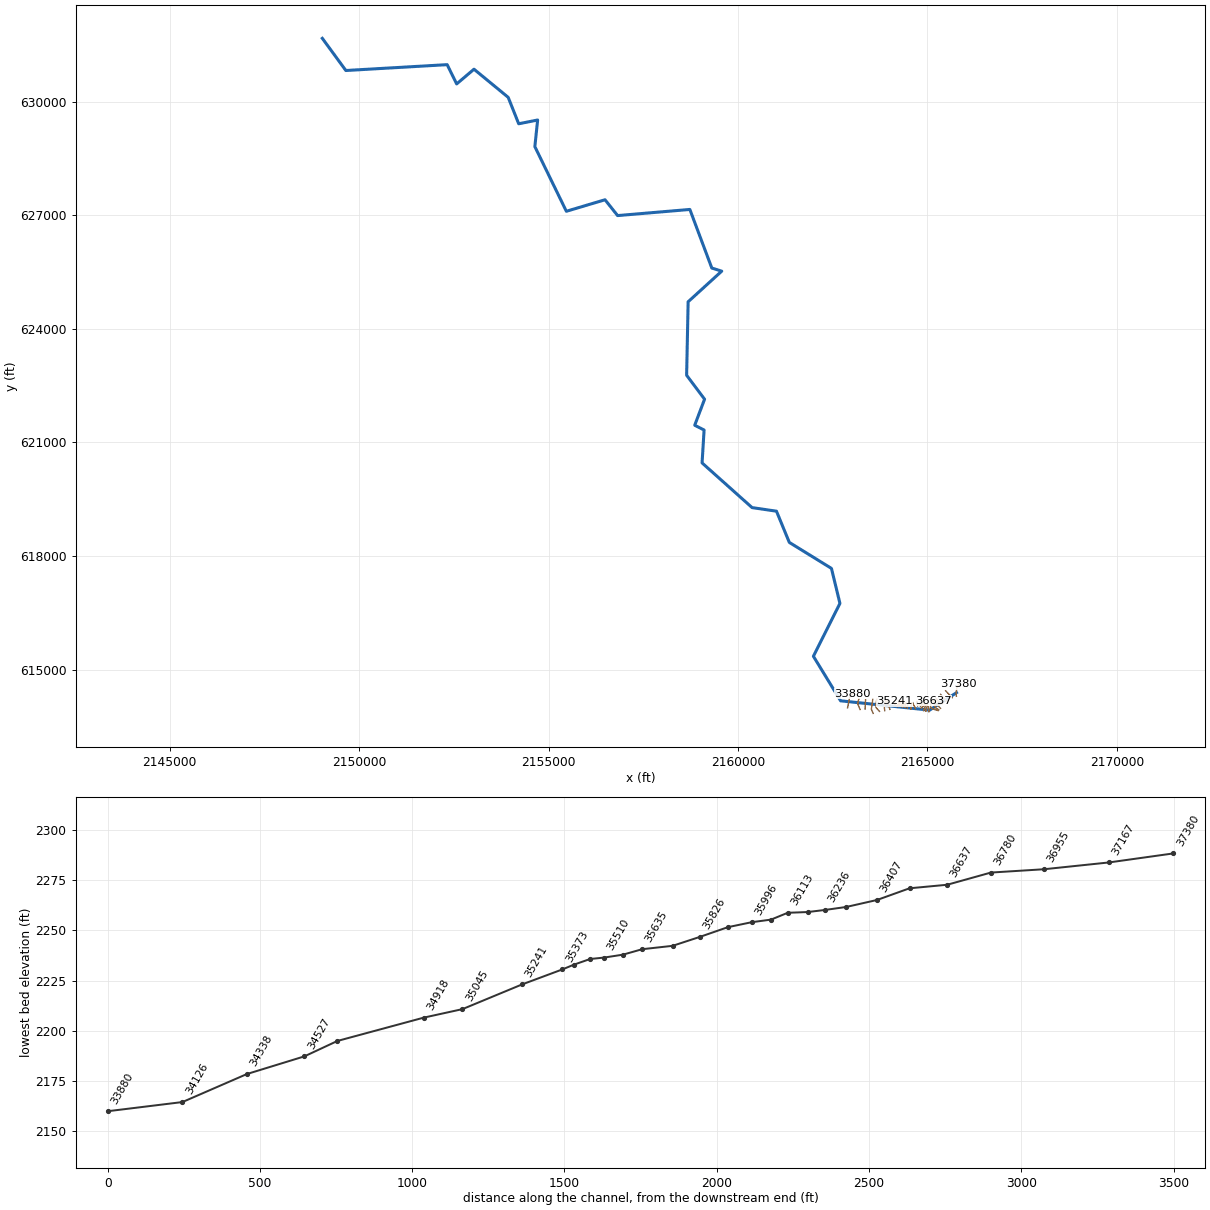
--- LFRFLIKANA.prj (project) ---

Proj Title=LFRFLIKANA
Current Plan=p01
Default Exp/Contr=0,0
English Units
Geom File=g01
Flow File=f01
Plan File=p01
BEGIN DESCRIPTION:
---------- MODELED AS PART OF WVEMD CTP PROGRAM, 2023----------
Stream Name: Left Fork Right Fork Little Kanawha River
Flood Zone:  AFH
Upshur County, WV
HEC-RAS Version: RAS 6.3
Vertical Datum: NAVD88
Projection: NAD 1983 StatePlane West Virginia S FIPS 4702 (US Feet)
Terrain: 1-meter LIDAR (FEMA Region III 3DEP collected 2016-2018)
Land Use: 2019 NLCD
Hydrologic Method:
WV SIR2010-5033 regression equations
Additional Model Notes:
Coincident Peak with Right Fork Little Kanawha River. KWSE used as tie-in.
END DESCRIPTION:
DSS Export Rating Curves= 0
DSS Export Rating Curve Sorted= 0
DSS Export Volume Flow Curves= 0
DXF OffsetX= 0
DXF OffsetY= 0
DXF ScaleX= 0
DXF ScaleY= 0

--- LFRFLIKANA.p01 (plan) ---

Plan Title=Floodplain
Program Version=6.30
Short Identifier=Floodplain
Geom File=g01
Flow File=f01
Subcritical Flow
K Sum by GR= 0
Std Step Tol= 0.01
Critical Tol= 0.01
Num of Std Step Trials= 20
Max Error Tol= 0.3
Flow Tol Ratio= 0.001
Split Flow NTrial= 30
Split Flow Tol= 0.02
Split Flow Ratio= 0.02
Log Output Level= 0
Friction Slope Method= 1
Unsteady Friction Slope Method= 2
Unsteady Bridges Friction Slope Method= 1
Parabolic Critical Depth
Global Vel Dist= 0 , 0 , 0
Global Log Level= 0
CheckData=False
Encroach Param=-1 ,0,0, 0
Mapping Interval=1HOUR
Computation Time Step Use Courant=        0
Computation Time Step Use Time Series=    0
Computation Time Step Count To Double=0
Computation Time Step Max Doubling=0
Computation Time Step Max Halving=0
Computation Time Step Residence Courant=0
Run HTab= 0
Run UNet= 0
Run Sediment= 0
Run PostProcess= 0
Run WQNet= 0
Run RASMapper=-1
UNET Theta= 0
UNET Theta Warmup= 0
UNET ZTol= 0
UNET ZSATol= 0
UNET MxIter= 0
UNET Max Iter WO Improvement= 0
UNET MaxInSteps= 0
UNET DtIC= 0
UNET DtMin= 0
UNET MaxCRTS= 0
UNET WFStab= 0
UNET SFStab= 0
UNET WFX= 1
UNET SFX= 1
UNET Gravity=32.17405
UNET 1D Methodology=Finite Difference
UNET DSS MLevel= 1
UNET Pardiso=0
UNET DZMax Abort= 0
UNET Use Existing IB Tables= 0
UNET Froude Reduction=False
UNET Froude Limit= 0
UNET Froude Power= 0
UNET D1 Cores= 0
UNET WindReference=Eulerian
UNET WindDragFormulation=Hsu (1988)
UNET D2 Coriolis=0
UNET D2 Cores= 0
UNET D2 Theta= 1
UNET D2 Theta Warmup= 1
UNET D2 Z Tol= 0.01
UNET D2 Volume Tol= 0.01
UNET D2 Max Iterations= 20
UNET D2 Equation= 0
UNET D2 RampUpFraction=0.1
UNET D2 TimeSlices= 1
UNET D2 Turbulence Formulation=Non-Conservative (original)
UNET D2 Eddy Viscosity=0.3
UNET D2 Transverse Eddy Viscosity=0.1
UNET D2 Smagorinsky Mixing=0
UNET D2 BCVolumeCheck=0
UNET D2 Cores=0
UNET D2 SolverType=PARDISO (Direct)
UNET D2 Minimum Iterations= 3
UNET D2 Maximum Iterations= 30
UNET D2 Restart Number= 10
UNET D2 Relaxation Coeff=1.3
UNET D2 SOR Precondition Iterations= 10
UNET D2 ILUT Maximum Fill= 8
UNET D2 ILUT Tolerance=1E-08
UNET D2 Convergence Tolerance=0.00001
UNET D1D2 MaxIter= 0
UNET D1D2 ZTol=0.01
UNET D1D2 QTol=0.1
UNET D1D2 MinQTol=1
Write IC File= 0
Write IC File at Fixed DateTime=0
Write IC File at Sim End=0
Echo Input=False
Echo Parameters=False
Echo Output=False
Write Detailed= 0
HDF Write Warmup=0
HDF Write Time Slices=0
HDF Flush=0
HDF Compression= 1
HDF Chunk Size= 1
HDF Spatial Parts= 1
HDF Use Max Rows=0
HDF Fixed Rows= 1
Calibration Method= 0
Calibration Iterations= 20
Calibration Max Change=0.05
Calibration Tolerance=0.2
Calibration Maximum=1.5
Calibration Minimum=0.5
Calibration Optimization Method= 1
WQ AD Non Conservative
WQ ULTIMATE=-1
WQ Max Comp Step=1HOUR
WQ Output Interval=15MIN
WQ Output Selected Increments= 0
WQ Output face flow=0
WQ Output face velocity=0
WQ Output face area=0
WQ Output face dispersion=0
WQ Output cell volume=0
WQ Output cell surface area=0
WQ Output cell continuity=0
WQ Output cumulative cell continuity=0
WQ Output face conc=0
WQ Output face dconc_dx=0
WQ Output face courant=0
WQ Output face peclet=0
WQ Output face adv mass=0
WQ Output face disp mass=0
WQ Output cell mass=0
WQ Output cell source sink temp=0
WQ Output nsm pathways=0
WQ Output nsm derived pathways=0
WQ Create Restart=0
WQ Fixed Restart=0
WQ System Summary=0
WQ Write To DSS=0
Sorting and Armoring Iterations= 10
XS Update Threshold= 0.02
Bed Roughness Predictor= 0
Hydraulics Update Threshold= 0.02
Energy Slope Method= 1
Volume Change Method= 1
Sediment Retention Method= 0
Sediment TS Multiplier= 1
Warm Up Method= 0
XS Weighting Method= 0
Number of US Weighted Cross Sections= 1
Number of DS Weighted Cross Sections= 1
Upstream XS Weight=0
Main XS Weight=1
Downstream XS Weight=0
Number of DS XS's Weighted with US Boundary= 1
Upstream Boundary Weight= 1
Weight of XSs Associated with US Boundary= 0
Number of US XS's Weighted with DS Boundary= 1
Downstream Boundary Weight= 0.5
Weight of XSs Associated with DS Boundary= 0.5
Percentile Method= 0
Sediment Output Level= 3
Mass or Volume Output= 0
Output Increment Type= 1
Profile and TS Output Increment= 1
Transport Output Increment 1
XS Output Flag= 0
XS Output Increment= 10
Read HDF5 Sediment Hotstart= 0
Sediment Hotstart Type= 0
Write Gradation File= 0
Read Gradation Hotstart= 0
Write HDF5 File= 1
Write Binary Output= 1
Write DSS Sediment File= 0
DSS Sediment Output Type= 1
SV Curve= 0
Specific Gage Flag= 0
Subcell Erosion Methods= 0
Subcell Deposition Methods= 0
Advection Scheme= 1
Matrix Solver= 0
Implicit Weighting Factor= 1
Maximum Outer Loop Convergence Iterations= 5
Convergence Maximum Absolute= 0.001
Convergence RMSE= 0.0001
Grain Fractions Max Abs Error= 0.001
Max Subgrid Regions= 1
Max Subgrid Length Scale= 3.402823E+38
Initial Layer Thickness= 3.402823E+38
Min Layer Thickness= 3.402823E+38
Max Layer Thickness= 3.402823E+38
Number of Layers= 5

--- LFRFLIKANA.f01 (steady flow) ---

Flow Title=Flows
Program Version=6.30
Number of Profiles= 1
Profile Names=01pct
River Rch & RM=LFRFLIKANA,Main            ,36979
     709
River Rch & RM=LFRFLIKANA,Main            ,32309
     789
River Rch & RM=LFRFLIKANA,Main            ,28758
     886
River Rch & RM=LFRFLIKANA,Main            ,23681
    1290
River Rch & RM=LFRFLIKANA,Main            ,21820
    1520
River Rch & RM=LFRFLIKANA,Main            ,16774
    1930
River Rch & RM=LFRFLIKANA,Main            ,15249
    2190
River Rch & RM=LFRFLIKANA,Main            ,11361
    2640
River Rch & RM=LFRFLIKANA,Main            ,8314
    2960
River Rch & RM=LFRFLIKANA,Main            ,0
    4460
Boundary for River Rch & Prof#=LFRFLIKANA,Main            , 1
Up Type= 0
Dn Type= 1
Dn Known WS=1335.7
DSS Import GetInterval= 0
DSS Import GetPeak= 0
DSS Import FillOption= 0

--- LFRFLIKANA.g01 (geometry) ---

Geom Title=Geometry
Program Version=6.31

River Reach=LFRFLIKANA      ,Main
Reach XY= 30
2165767.17363661614392.774335297     2165056.865      613931.572
     2162708.089      614177.673     2161990.018      615353.921
      2162690.29      616750.486     2162466.624      617674.195
     2161354.649      618360.874      2161015.63      619185.426
     2160372.477      619279.546     2159052.603      620459.972
     2159105.629      621329.166     2158858.355      621454.792
     2159118.593      622142.329     2158644.619      622774.522
     2158684.825      624715.829     2159571.619      625524.099
     2159309.292      625606.085     2158730.097      627153.574
2156823.43577506626991.4801652072156491.55149961627409.508318326
     2155471.005      627105.098     2154639.928      628812.552
       2154713.3      629515.399       2154213.4      629415.985
     2153936.365      630114.0252153033.95592255630857.148504125
     2152576.514      630467.952     2152326.178      630977.238
      2149652.32      630822.7382149031.11094837       631672.33

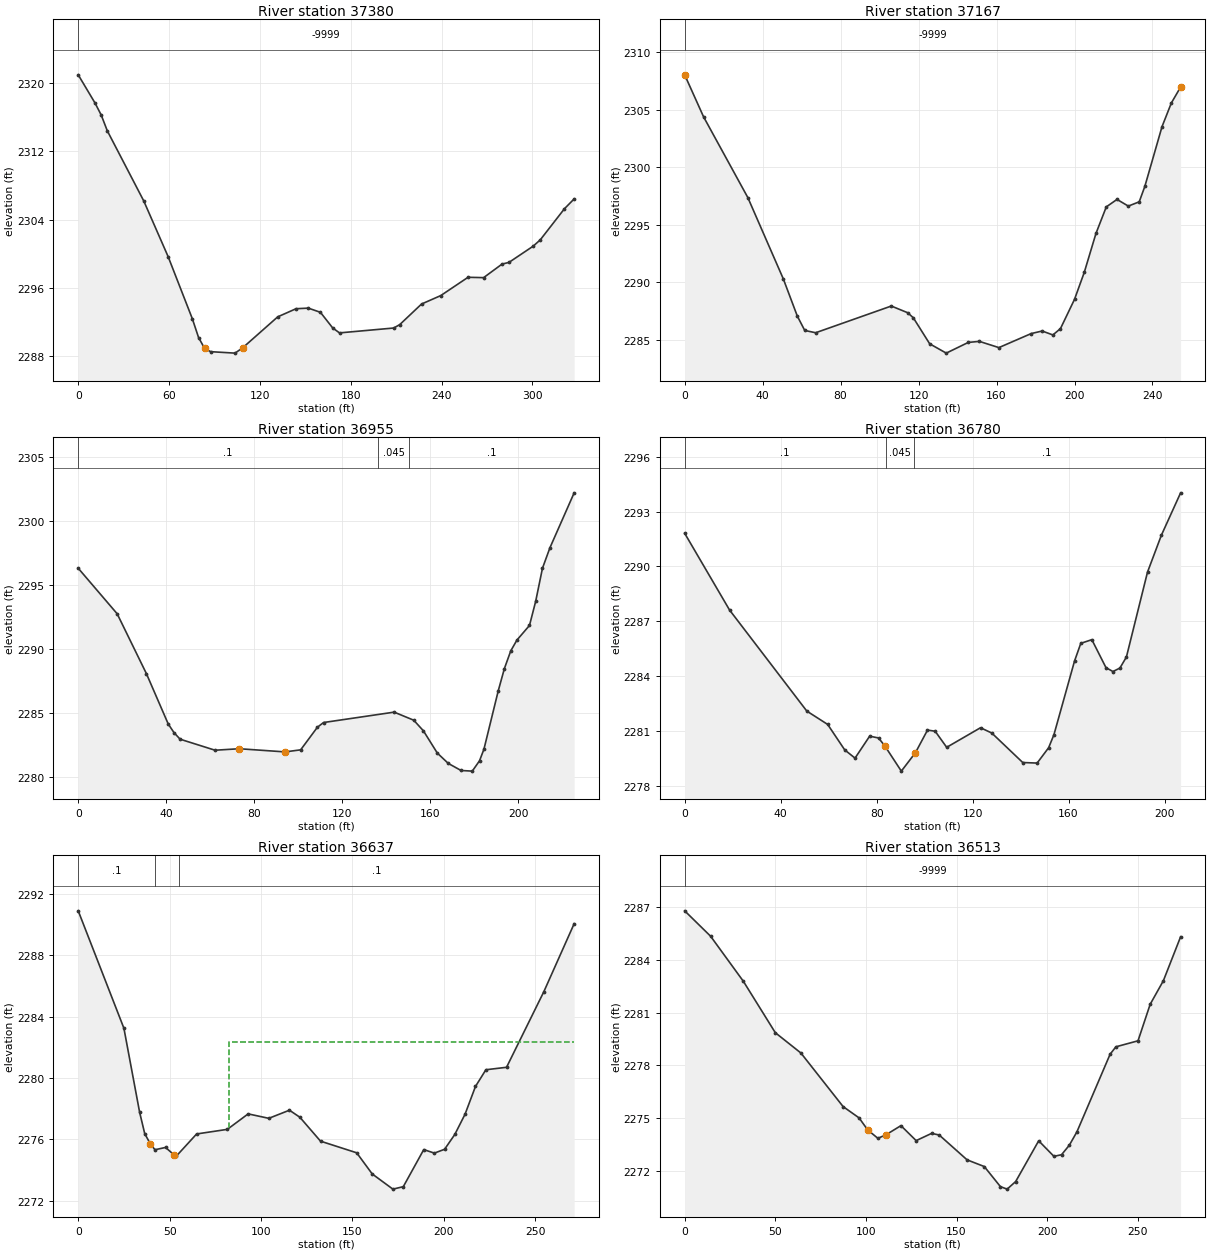
Type RM Length L Ch R = 1 ,37380   ,212.4,212.4,212.4
XS GIS Cut Line= 4
2165763.76045965 614298.08530517 2165756.9472534614370.305291374
2165773.29894839 614508.613378162165826.44195711614611.492792469
#Sta/Elev= 30
       0 2320.95    11.1 2317.65    15.2 2316.24    19.2  2314.4    43.3 2306.18
    59.4 2299.66    75.4 2292.38    79.5 2290.19    83.5 2288.91    87.5 2288.53
   103.6 2288.36   108.7 2288.99   131.8 2292.61   143.9 2293.56     152 2293.63
     160 2293.14   168.1 2291.31   172.6 2290.73   208.4  2291.3   212.4  2291.7
   226.8 2294.11   239.5  2295.1   257.5 2297.24   267.8  2297.2     280 2298.79
   284.5 2298.98   300.5 2300.88   305.2 2301.62   321.2 2305.27327.6064 2306.42
#Mann= 1 ,-1,0
       0   -9999       0
Bank Sta=83.5,108.7
XS Rating Curve= 0 ,0
Exp/Cntr(USF)=0,0
Exp/Cntr=0.3,0.1

Type RM Length L Ch R = 1 ,37167   ,212.4,212.4,212.4
XS GIS Cut Line= 2
2165653.38651847614260.6126708192165477.60579733614444.569239451
#Sta/Elev= 30
       0 2308.02     9.7 2304.37    32.4 2297.36    50.6  2290.3    57.8 2287.06
    61.6 2285.82    67.2 2285.62     106 2287.94   114.4 2287.36   117.3 2286.92
   125.7 2284.66   134.2 2283.85   145.5 2284.78   151.2 2284.87   161.2 2284.33
   177.8 2285.55   183.4 2285.77   188.9 2285.43   192.8 2285.98     200 2288.52
     205 2290.86     211 2294.24   216.3 2296.55   221.8  2297.2   227.6 2296.62
   233.2 2296.99   236.1 2298.34   244.9 2303.52   249.7 2305.58254.4384 2306.96
#Mann= 1 ,-1,0
       0   -9999       0
Bank Sta=0,254.4384
XS Rating Curve= 0 ,0
Exp/Cntr(USF)=0,0
Exp/Cntr=0.3,0.1

Type RM Length L Ch R = 1 ,36955   ,157.8,174.7,162.2
XS GIS Cut Line= 3
2165486.68429941614173.1081287962165472.14941153 614204.16752595
2165346.34737117614348.045560467
#Sta/Elev= 30
       0  2296.3    17.7 2292.75      31 2288.08    40.9 2284.16    43.5 2283.49
    46.3 2282.97    62.2 2282.11    73.22282.226      942281.979   101.1 2282.14
   108.7  2283.9   111.5 2284.27   143.6 2285.08   152.5 2284.45   156.9 2283.62
   163.2 2281.89   168.2 2281.08     174 2280.53   179.1 2280.48   182.4 2281.29
   184.4 2282.19   190.9 2286.74   193.7 2288.48   196.6 2289.86   199.4  2290.7
   205.1 2291.84   207.9 2293.71     211  2296.3   214.4  2297.9   225.4 2302.18
#Mann= 3 ,-1,0
       0      .1       0   136.2    .045       0   150.4      .1       0
Bank Sta=73.2,94
XS Rating Curve= 0 ,0
Exp/Cntr(USF)=0,0
Exp/Cntr=0.3,0.1

Type RM Length L Ch R = 1 ,36780   ,144.7,143.4,139.7
XS GIS Cut Line= 4
2165397.65671595614105.1271916452165361.70113148 614125.35220791
2165262.35893625614187.6581052362165235.65260578614227.795761978
#Sta/Elev= 30
       0 2291.81    18.7 2287.62    50.9  2282.1    59.6 2281.37    66.7 2279.98
      71 2279.53    77.1 2280.73    80.8 2280.63    83.42280.201    90.3 2278.82
    96.22279.831   101.2 2281.06   104.4    2281   109.2 2280.12   123.3 2281.19
     128  2280.9   140.9 2279.29   146.9 2279.26   151.7  2280.1   153.9 2280.81
   162.5 2284.84   165.1  2285.8   169.7    2286   175.6 2284.47   178.5 2284.26
   181.4 2284.45   184.1 2285.05   192.9 2289.69   198.7 2291.71   206.7 2294.02
#Mann= 3 ,-1,0
       0      .1       0    83.7    .045       0    95.5      .1       0
Bank Sta=83.4,96.2
XS Rating Curve= 0 ,0
Exp/Cntr(USF)=0,0
Exp/Cntr=0.3,0.1

Type RM Length L Ch R = 1 ,36637   ,116.1,123.7,108.9
XS GIS Cut Line= 3
2165345.80888228613979.3239393112165179.81512386614145.731885442
2165161.50713212614177.084690463
#Sta/Elev= 30
       0 2290.91      25 2283.25    33.6 2277.77    36.4 2276.37    39.52275.695
      42 2275.32    47.8 2275.47    52.32275.001    53.5 2274.88    64.8 2276.35
    81.6 2276.65      93 2277.66   104.3 2277.37   115.6  2277.9   121.3 2277.44
   132.6 2275.88   152.4 2275.12   160.9 2273.74   172.2 2272.75   177.9 2272.91
   189.1 2275.33   194.9  2275.1   200.5 2275.35   206.1 2276.32   211.7 2277.64
   217.4 2279.45   223.1 2280.54   234.4  2280.7   254.8 2285.63   271.4 2290.07
#Mann= 3 ,-1,0
       0      .1       0    42.1    .045       0    55.4      .1       0
#XS Ineff= 2 , 0
                           82.65         2282.35
Permanent Ineff=
       F       F
Bank Sta=39.5,52.3
XS Rating Curve= 0 ,0
Exp/Cntr(USF)=0,0
Exp/Cntr=0.3,0.1

Type RM Length L Ch R = 1 ,36513   ,112.8,106.5,119.5
XS GIS Cut Line= 3
2165299.38063168 613940.818305622165212.30785586613991.712956275
2165157.12088527614155.434302358
#Sta/Elev= 30
       0 2286.77    14.3 2285.33    32.4 2282.77      50 2279.86    64.1 2278.71
    87.4 2275.67    96.2 2275.03     1012274.345   106.6 2273.87   111.2 2274.08
   119.3 2274.59   127.7 2273.74   136.2 2274.15   140.4 2274.06   155.8 2272.65
   165.3 2272.27   174.2 2271.13   177.9 2270.99   182.6 2271.42   195.3 2273.73
   203.7 2272.85   207.9 2272.94   212.2 2273.48   216.4 2274.24   234.7 2278.64
   237.9 2279.06   250.1  2279.4   256.8 2281.47   264.1 2282.81   273.6  2285.3
#Mann= 1 ,-1,0
       0   -9999       0
Bank Sta=101,111.2
XS Rating Curve= 0 ,0
Exp/Cntr(USF)=0,0
Exp/Cntr=0.3,0.1

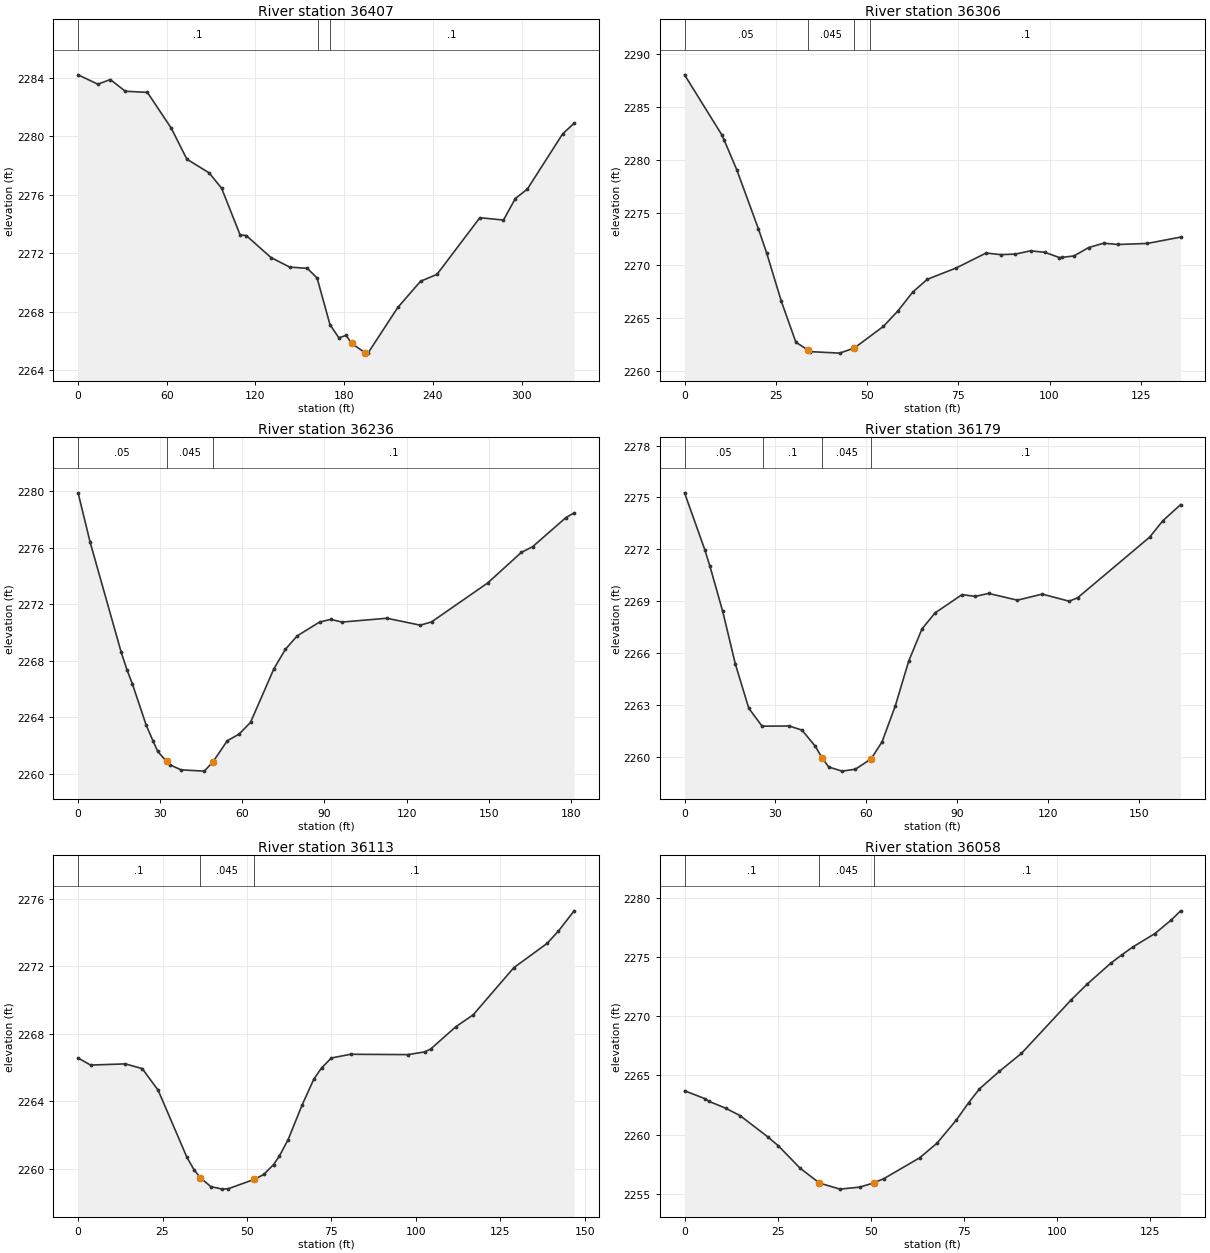
Type RM Length L Ch R = 1 ,36407   ,117.5,101,95.9
XS GIS Cut Line= 4
  2165285.022462 613918.190159882165142.40435978613961.666716732
2165081.94337429614004.9893635822165089.51397144614116.900479366
#Sta/Elev= 30
       0 2284.19    13.4 2283.55    21.8 2283.87    31.9 2283.07    46.9 2282.99
      63 2280.55    73.6 2278.43    88.7 2277.49    97.1 2276.44   109.6 2273.26
   113.8 2273.21   130.5 2271.71   143.1 2271.06   155.1 2270.97   161.7 2270.31
   170.4 2267.13   176.4 2266.23   181.4 2266.39   185.12265.839   194.32265.202
   196.1 2265.18   216.3  2268.3   231.7 2270.09   242.8 2270.56   271.8 2274.43
   287.8 2274.27   295.8 2275.74   303.9 2276.38   327.9 2280.17   335.6 2280.88
#Mann= 3 ,-1,0
       0      .1       0     162    .045       0   170.4      .1       0
Bank Sta=185.1,194.3
XS Rating Curve= 0 ,0
Exp/Cntr(USF)=0,0
Exp/Cntr=0.3,0.1

Type RM Length L Ch R = 1 ,36306   ,73.8,69.6,65.9
XS GIS Cut Line= 4
2165038.90470139613887.3354078412165033.66117866613907.560424106
2165034.41025333613962.9919501652165027.66858125614022.168849607
#Sta/Elev= 30
       0 2288.06    10.2 2282.38    10.9 2281.84    14.3 2279.07    20.2  2273.5
    22.5 2271.18    26.5 2266.62    30.5 2262.73    33.72262.018    34.5 2261.84
    42.5  2261.7    46.5 2262.18    54.5 2264.24    58.5 2265.72    62.5 2267.48
    66.5 2268.69    74.5 2269.78    82.6 2271.18    86.6 2271.03    90.6 2271.08
    94.8 2271.39    98.7 2271.25   102.7 2270.75   103.5 2270.77   106.7 2270.91
   110.7  2271.7   114.8 2272.11   118.8 2271.99   126.8 2272.09   135.9 2272.69
#Mann= 4 ,-1,0
       0     .05       0    33.7    .045       0    46.5     .05       0
   50.89      .1       0
Bank Sta=33.7,46.5
XS Rating Curve= 0 ,0
Exp/Cntr(USF)=0,0
Exp/Cntr=0.3,0.1

Type RM Length L Ch R = 1 ,36236   ,58,56.9,55.5
XS GIS Cut Line= 4
2164957.25556166613900.8187520172164958.00463633613916.549320223
2164979.72780195613978.7225183712165000.70189289614076.102226313
#Sta/Elev= 30
       0 2279.87     4.4 2276.38    15.7 2268.64    17.9 2267.34    19.8 2266.39
    24.9 2263.45    27.4 2262.33    29.1  2261.6    32.32260.897    33.4 2260.67
    37.6  2260.3    46.1 2260.21    49.3 2260.87    54.5 2262.36    58.8 2262.82
      63 2263.66    71.5 2267.43    75.7 2268.81      80 2269.76    88.2 2270.74
    92.3 2270.93    96.4 2270.74   112.8 2271.01     125 2270.52   129.1 2270.75
   149.6  2273.5   161.9 2275.66     166 2276.06   178.2 2278.12   181.2 2278.45
#Mann= 3 ,-1,0
       0     .05       0    32.3    .045       0    49.3      .1       0
Bank Sta=32.3,49.3
XS Rating Curve= 0 ,0
Exp/Cntr(USF)=0,0
Exp/Cntr=0.3,0.1

Type RM Length L Ch R = 1 ,36179   ,71.4,66,58.9
XS GIS Cut Line= 4
2164895.96371942613917.0712493962164900.38693048613932.306754149
2164934.78968315 614007.501342122164962.80335318614066.477489548
#Sta/Elev= 30
       0 2275.27     6.7 2271.97     8.4 2271.01    12.6 2268.41    16.8 2265.35
    21.2 2262.81    25.6 2261.77    34.6 2261.78    38.8 2261.54    43.2  2260.6
    45.4 2259.94    47.6 2259.41      52 2259.17    56.4 2259.28    61.6 2259.88
    65.2 2260.86    69.6 2262.95      74 2265.53    78.4  2267.4    82.7 2268.32
    91.6 2269.38      96 2269.28   100.4 2269.45   109.9 2269.06   118.1 2269.41
     127    2269   129.8  2269.2   153.6 2272.71   157.9 2273.65   163.8 2274.59
#Mann= 4 ,-1,0
       0     .05       0   25.86      .1       0    45.4    .045       0
    61.6      .1       0
Bank Sta=45.4,61.6
XS Rating Curve= 0 ,0
Exp/Cntr(USF)=0,0
Exp/Cntr=0.3,0.1

Type RM Length L Ch R = 1 ,36113   ,54,54.8,55.3
XS GIS Cut Line= 3
2164837.17781938613986.9193832712164902.27886678614037.760201235
2164943.19952514614087.360999249
#Sta/Elev= 30
       0 2266.57     3.7 2266.15      14 2266.22      19 2265.94    23.7 2264.66
    32.2 2260.69    34.3 2259.95    36.2 2259.47    39.3 2258.94    42.7 2258.79
    44.4 2258.81    52.2 2259.37      55 2259.66    57.9 2260.25    59.6 2260.75
    62.2 2261.73    66.4 2263.81    69.8 2265.31    72.1 2265.98      75 2266.57
    80.7 2266.79    97.7 2266.77   102.6 2266.93   104.4  2267.1   111.9 2268.43
     117 2269.13     129 2271.92   138.9 2273.37   142.2 2274.09   146.9  2275.3
#Mann= 3 ,-1,0
       0      .1       0    36.2    .045       0    52.2      .1       0
Bank Sta=36.2,52.2
XS Rating Curve= 0 ,0
Exp/Cntr(USF)=0,0
Exp/Cntr=0.3,0.1

Type RM Length L Ch R = 1 ,36058   ,57.5,62.9,68.3
XS GIS Cut Line= 3
2164812.99743035614032.800121434 2164879.3384977614091.701069075
 2164899.1788169614131.381707486
#Sta/Elev= 28
       0  2263.7     5.4 2263.04     6.6  2262.8      11 2262.23    14.9  2261.6
    22.4 2259.79    25.2 2259.04      31 2257.16    36.22255.904    41.7 2255.39
      47 2255.56    50.7 2255.91    53.5 2256.28    63.1 2258.04    67.7 2259.26
    72.9 2261.22    76.2 2262.68    79.1 2263.85    84.5 2265.35    90.4 2266.86
   103.8  2271.4     108  2272.7   114.3 2274.46   117.4  2275.2   120.3 2275.85
   126.2 2276.98   130.6 2278.13   133.1  2278.9
#Mann= 3 ,-1,0
       0      .1       0    36.2    .045       0    50.7      .1       0
Bank Sta=36.2,50.7
XS Rating Curve= 0 ,0
Exp/Cntr(USF)=0,0
Exp/Cntr=0.3,0.1

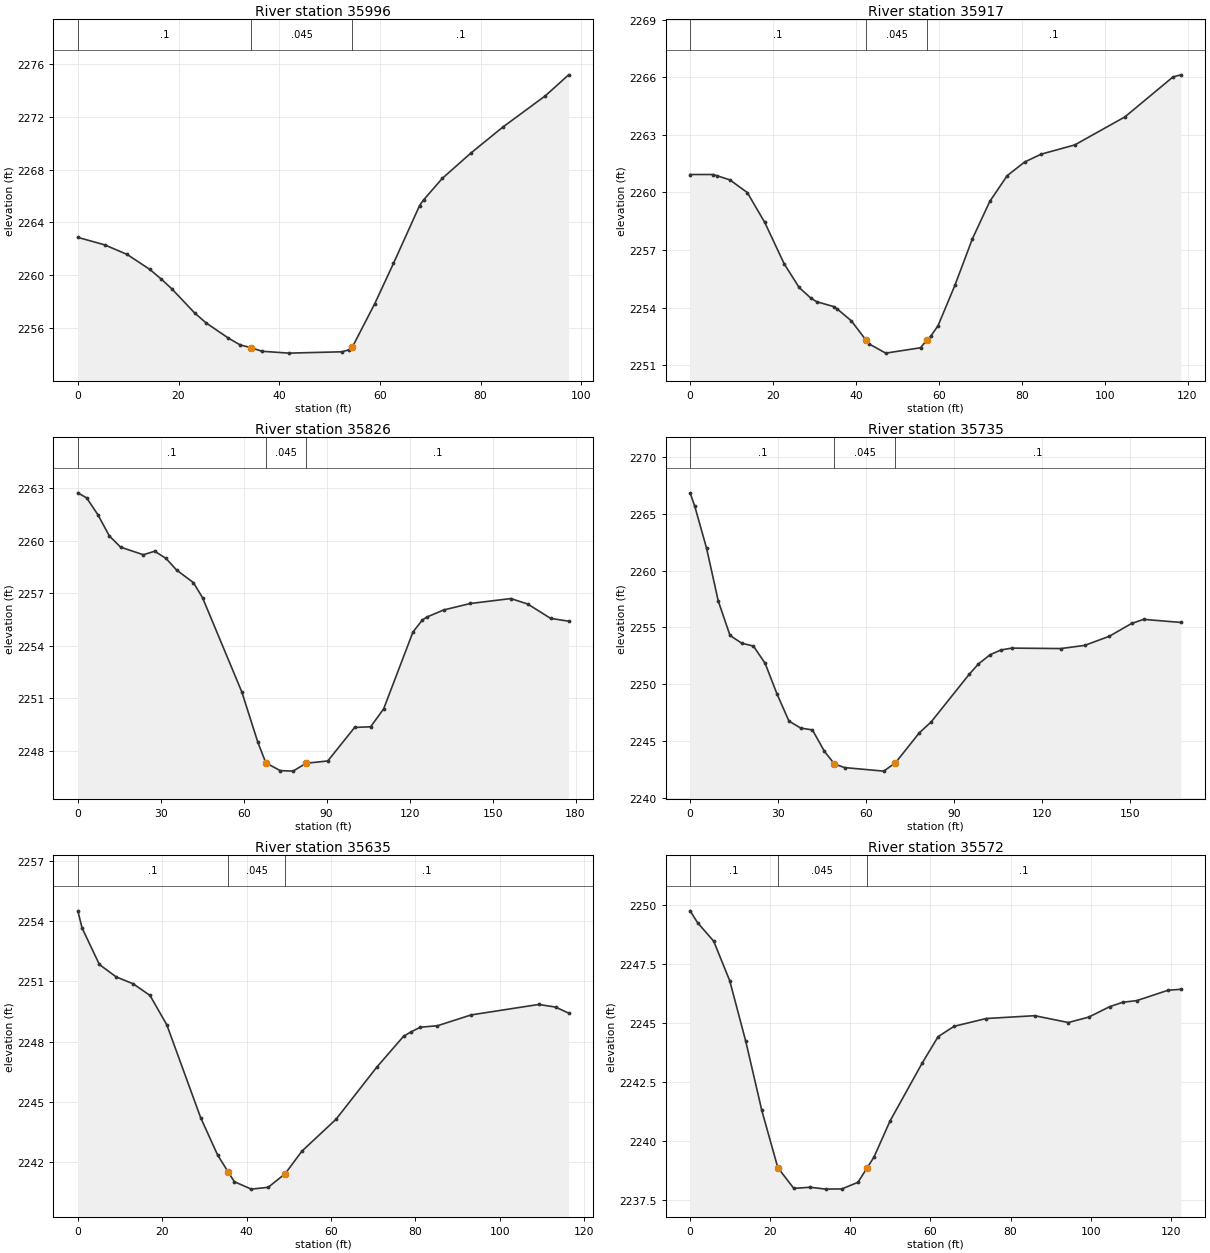
Type RM Length L Ch R = 1 ,35996   ,67.4,78.8,89.7
XS GIS Cut Line= 3
2164780.75691164614064.420630167 2164814.2374503614131.381707486
2164817.95751015614153.702066593
#Sta/Elev= 25
       0 2262.87     5.3 2262.31     9.8 2261.58    14.3 2260.45    16.6 2259.71
    18.7 2258.97    23.2 2257.16    25.5  2256.4    29.9 2255.26    32.2 2254.75
    34.5 2254.52    36.6 2254.26    41.9 2254.12    52.4 2254.22    53.8 2254.36
    54.5 2254.55      59 2257.87    62.7  2260.9    67.9 2265.28    68.7 2265.71
    72.4 2267.33    78.1 2269.25    84.4  2271.2    92.9 2273.58    97.5 2275.16
#Mann= 3 ,-1,0
       0      .1       0    34.5    .045       0    54.5      .1       0
Bank Sta=34.5,54.5
XS Rating Curve= 0 ,0
Exp/Cntr(USF)=0,0
Exp/Cntr=0.3,0.1

Type RM Length L Ch R = 1 ,35917   ,87,90.7,93.3
XS GIS Cut Line= 3
2164739.21624331614043.9603009872164715.65586425614122.081557859
2164719.99593408614158.662146394
#Sta/Elev= 30
       0 2260.93     5.5 2260.93     6.6 2260.86     9.6 2260.65    13.8 2259.99
      18 2258.44    22.7 2256.28    26.3 2255.05    29.1  2254.5    30.5 2254.31
    34.7 2254.05    35.5 2253.93    38.9 2253.31    42.5 2252.29    43.1 2252.12
    47.2 2251.63    55.6 2251.91    57.1 2252.31      58  2252.5    59.8 2253.05
    63.9 2255.17    68.1 2257.58    72.3 2259.53    76.5 2260.87    80.7 2261.58
    84.7 2261.99    92.8 2262.47   104.9 2263.93   116.5 2266.01   118.4 2266.12
#Mann= 3 ,-1,0
       0      .1       0    42.5    .045       0    57.1      .1       0
Bank Sta=42.5,57.1
XS Rating Curve= 0 ,0
Exp/Cntr(USF)=0,0
Exp/Cntr=0.3,0.1

Type RM Length L Ch R = 1 ,35826   ,100.9,90.7,82.6
XS GIS Cut Line= 4
2164684.06568956613966.1136369442164675.13754592614003.500238447
2164627.70678282614081.6214953192164614.31456735614127.378231487
#Sta/Elev= 30
       0 2262.72     3.2 2262.43     7.3 2261.46    11.4 2260.26    15.5 2259.62
    23.7 2259.19    27.8 2259.39    31.9 2258.98    35.7 2258.32    41.8  2257.6
    45.1 2256.74    59.3 2251.37    65.1  2248.5      68 2247.32    73.2 2246.88
    77.8 2246.85    82.6  2247.3    90.4 2247.43   100.1 2249.34   105.9 2249.38
   110.6  2250.4   121.2 2254.78   124.6 2255.47   126.3 2255.64   132.3 2256.04
     142 2256.41   156.6 2256.69   162.7 2256.38     171 2255.56   177.5  2255.4
#Mann= 3 ,-1,0
       0      .1       0      68    .045       0    82.6      .1       0
Bank Sta=68,82.6
XS Rating Curve= 0 ,0
Exp/Cntr(USF)=0,0
Exp/Cntr=0.3,0.1

Type RM Length L Ch R = 1 ,35735   ,98.7,100,100.8
XS GIS Cut Line= 4
2164565.26694252613959.6081114292164565.35630535 613984.39954013
2164576.25198454614060.4747287882164570.36990391614125.841565818
#Sta/Elev= 30
       0 2266.84     1.6 2265.65     5.6 2261.98     9.6 2257.32    13.6 2254.29
    17.6  2253.6    21.6 2253.35    25.6 2251.82    29.6 2249.15    33.7 2246.75
    37.7 2246.13    41.7 2245.97    45.8 2244.08    49.2 2242.97    52.7 2242.65
      66 2242.34      70 2243.07    78.1  2245.7    82.2 2246.68    95.1 2250.85
    98.3 2251.78   102.3 2252.59     106 2253.01   109.7 2253.17   126.4 2253.13
   134.5 2253.41   142.9 2254.21   150.5 2255.34   154.6  2255.7   167.3 2255.43
#Mann= 3 ,-1,0
       0      .1       0    49.2    .045       0      70      .1       0
Bank Sta=49.2,70
XS Rating Curve= 0 ,0
Exp/Cntr(USF)=0,0
Exp/Cntr=0.3,0.1

Type RM Length L Ch R = 1 ,35635   ,62.6,62.8,63.5
XS GIS Cut Line= 3
2164469.45118898613988.1373435282164474.42304897614068.591077927
 2164473.9710617614104.298072407
#Sta/Elev= 25
       0 2254.51       1 2253.66     5.1 2251.84     9.1 2251.22    13.1 2250.88
    17.1  2250.3    21.1 2248.83    29.1 2244.22    33.1 2242.37    35.6 2241.52
    37.1 2241.03    41.1 2240.66    45.1 2240.75    49.1 2241.42    53.1 2242.55
    61.2 2244.14    70.8 2246.72    77.2 2248.27      79 2248.49    81.2 2248.72
    85.2 2248.79    93.2 2249.33   109.2 2249.85   113.2 2249.72   116.3 2249.42
#Mann= 3 ,-1,0
       0      .1       0    35.6    .045       0    49.1      .1       0
Bank Sta=35.6,49.1
XS Rating Curve= 0 ,0
Exp/Cntr(USF)=0,0
Exp/Cntr=0.3,0.1

Type RM Length L Ch R = 1 ,35572   ,65.4,62,57.7
XS GIS Cut Line= 4
2164408.10867381614003.295902112 2164410.8987187614072.489015342
2164412.57274563614097.599419336 2164433.2190778614116.571724577
#Sta/Elev= 27
       0 2249.76     1.9 2249.25     5.9 2248.47     9.9 2246.79    13.9 2244.22
    17.9 2241.29    21.9 2238.86    25.9 2237.98    29.9 2238.03    33.9 2237.95
    37.9 2237.96    41.9 2238.24    44.12238.829    45.9 2239.31    49.9 2240.84
    57.9 2243.29    61.9 2244.42    65.9 2244.86    73.9 2245.19      86 2245.31
    94.4 2245.02    99.5 2245.25   104.7 2245.69     108 2245.88   111.5 2245.95
   119.3 2246.39   122.5 2246.43
#Mann= 3 ,-1,0
       0      .1       0    21.9    .045       0    44.1      .1       0
Bank Sta=21.9,44.1
XS Rating Curve= 0 ,0
Exp/Cntr(USF)=0,0
Exp/Cntr=0.3,0.1

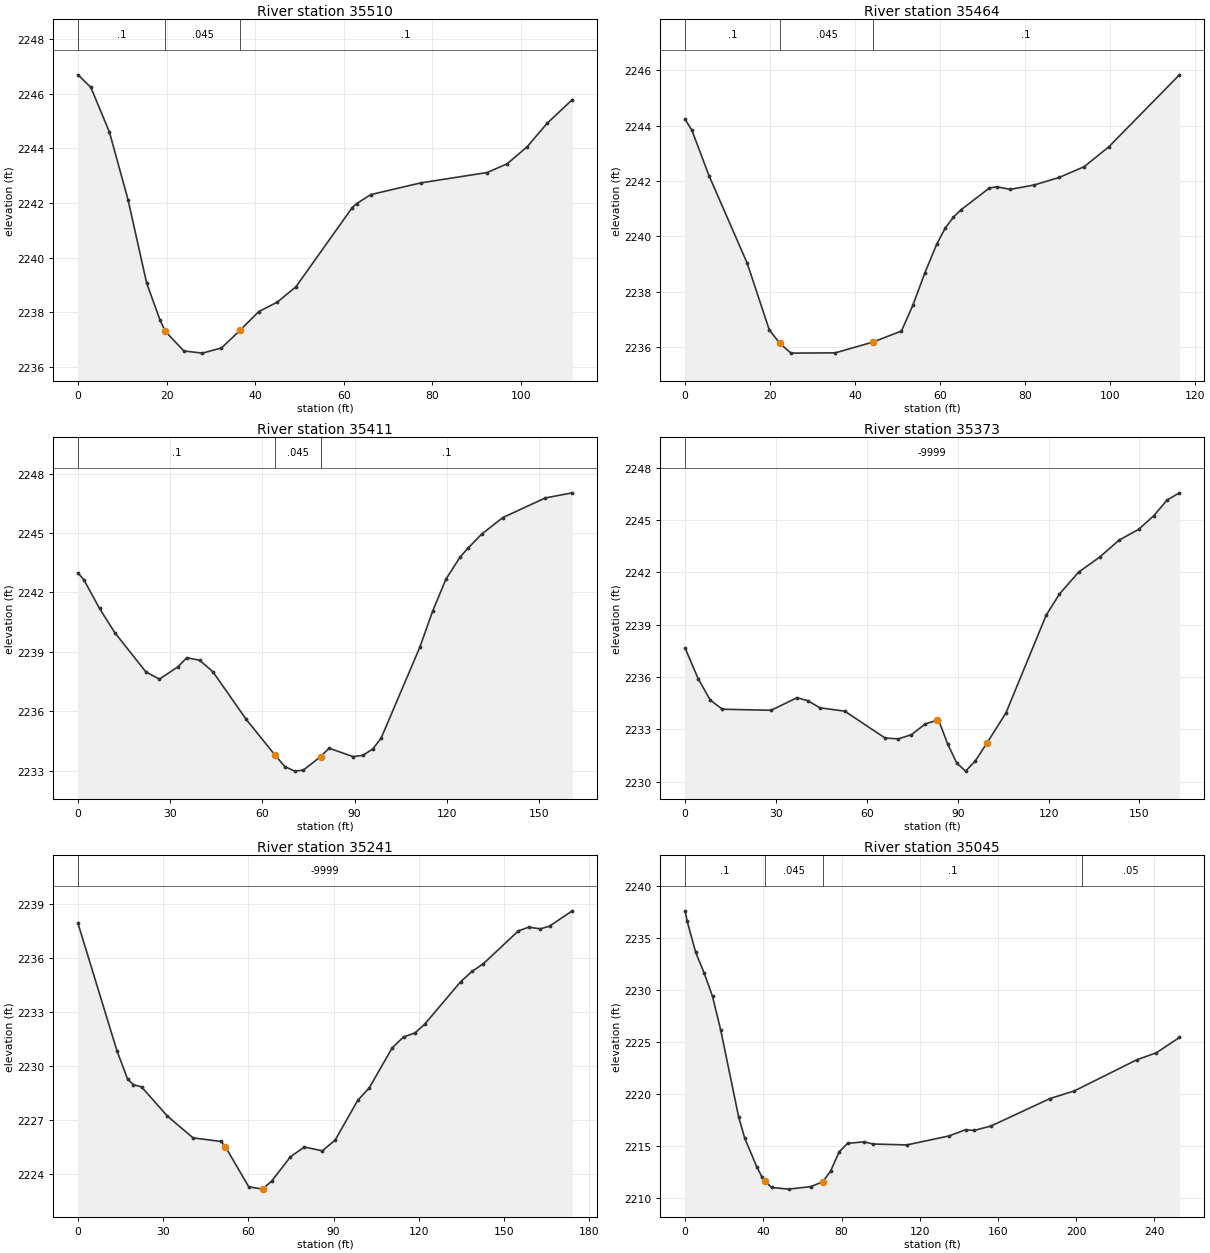
Type RM Length L Ch R = 1 ,35510   ,51.3,46.1,40.6
XS GIS Cut Line= 3
2164339.47356956614014.4560816652164362.90994662614085.323221828
2164379.65021595 614118.24575151
#Sta/Elev= 23
       0  2246.7     2.9 2246.24     7.1  2244.6    11.3 2242.12    15.5 2239.07
    18.5 2237.72    19.7  2237.3    23.9 2236.58    28.1  2236.5    32.4 2236.69
    36.6 2237.34    40.8 2238.02      45 2238.37    49.2 2238.93    61.9 2241.83
    62.9 2241.98    66.1 2242.31    77.4 2242.74    92.4 2243.12    96.9 2243.44
   101.4 2244.06   105.9 2244.92   111.6 2245.79
#Mann= 3 ,-1,0
       0      .1       0    19.7    .045       0    36.6      .1       0
Bank Sta=19.7,36.6
XS Rating Curve= 0 ,0
Exp/Cntr(USF)=0,0
Exp/Cntr=0.3,0.1

Type RM Length L Ch R = 1 ,35464   ,49,53,57.6
XS GIS Cut Line= 4
2164293.30508099614035.6084406362164294.81170523614046.154810314
2164334.98835163614094.8689940632164356.58329906614131.530183895
#Sta/Elev= 24
       0 2244.23     1.6 2243.83     5.6  2242.2    14.6 2239.03    19.8 2236.62
    22.3 2236.13    24.9 2235.78    35.3 2235.79    44.2 2236.18    50.9 2236.58
    53.6 2237.52    56.4 2238.68    59.2 2239.72    61.2  2240.3    63.1 2240.69
    64.9 2240.96    71.6 2241.75    73.4 2241.79    76.5  2241.7    82.2 2241.86
      88 2242.13    93.9 2242.52    99.7 2243.24   116.3 2245.84
#Mann= 3 ,-1,0
       0      .1       0    22.3    .045       0    44.2      .1       0
Bank Sta=22.3,44.2
XS Rating Curve= 0 ,0
Exp/Cntr(USF)=0,0
Exp/Cntr=0.3,0.1

Type RM Length L Ch R = 1 ,35411   ,38.7,38,36.3
XS GIS Cut Line= 4
 2164273.2167578614035.6084406362164257.14609924614056.701179991
 2164285.7719598614144.0853858932164306.86469915614180.746575725
#Sta/Elev= 30
       0 2242.98     1.9 2242.64       7 2241.19      12 2239.96    22.1 2237.98
    26.5 2237.62    32.5 2238.24    35.4  2238.7    39.6 2238.57    43.9 2237.99
    54.7 2235.59    64.2 2233.76    67.3  2233.2    70.5 2232.97    73.3 2233.02
    78.9  2233.7    81.7 2234.13    89.5  2233.7    92.7 2233.77    95.9 2234.09
    98.6 2234.63   111.2 2239.23   115.4 2241.06   119.7 2242.67   124.3 2243.78
   126.9 2244.24   131.3 2244.94   138.2 2245.78     152 2246.77   160.8 2247.03
#Mann= 3 ,-1,0
       0      .1       0    64.2    .045       0    78.9      .1       0
Bank Sta=64.2,78.9
XS Rating Curve= 0 ,0
Exp/Cntr(USF)=0,0
Exp/Cntr=0.3,0.1

Type RM Length L Ch R = 1 ,35373   ,115.3,132.1,148
XS GIS Cut Line= 3
2164231.60820316614036.9076535582164226.24402962614087.867302201
2164274.52159149614188.892570562
#Sta/Elev= 30
       0 2237.65     4.3  2235.9     8.3 2234.67    12.3 2234.15    28.4 2234.09
    36.9 2234.81    40.5 2234.64    44.5 2234.23    52.7 2234.04      66  2232.5
    70.4 2232.45    74.7 2232.69    79.3 2233.31    83.32233.518    83.7 2233.52
    86.7 2232.15    89.7 2231.06    92.6  2230.6    95.7 2231.16    99.62232.199
   105.9 2233.93   119.2 2239.54   123.6 2240.76   129.9 2242.01   136.9 2242.88
   143.3 2243.85   149.7 2244.46   154.7 2245.24   159.1 2246.14   163.2 2246.56
#Mann= 1 ,-1,0
       0   -9999       0
Bank Sta=83.3,99.6
XS Rating Curve= 0 ,0
Exp/Cntr(USF)=0,0
Exp/Cntr=0.3,0.1

Type RM Length L Ch R = 1 ,35241   ,199.4,195.9,190.5
XS GIS Cut Line= 3
2164205.23434992614027.0733353992164135.05307942614076.691940656
2164126.55980464614164.306775165
#Sta/Elev= 30
       0 2237.91    13.7 2230.84    17.5 2229.24    19.5 2228.95    22.4 2228.82
    31.4 2227.21    40.5 2225.99    50.3 2225.79    51.92225.492    60.1 2223.27
      65 2223.14    68.3 2223.61    74.8 2224.94    79.7 2225.48      86 2225.27
    90.5 2225.86    98.5 2228.08   102.5 2228.76   110.6 2230.99   114.6  2231.6
   118.6 2231.82     122  2232.3   134.7 2234.67   138.7 2235.24   142.7 2235.67
     155 2237.49   158.6  2237.7   162.8 2237.61     166 2237.76     174 2238.61
#Mann= 1 ,-1,0
       0   -9999       0
Bank Sta=51.9,65
XS Rating Curve= 0 ,0
Exp/Cntr(USF)=0,0
Exp/Cntr=0.3,0.1

Type RM Length L Ch R = 1 ,35045   ,132.1,127.5,120.8
XS GIS Cut Line= 3
2164010.93214337613952.2068906862163938.21492406614131.320883514
2163964.24003413 614184.90199248
#Sta/Elev= 30
       0 2237.59       1 2236.61     5.4 2233.59     9.7 2231.62      14 2229.36
    18.2 2226.12    27.4 2217.75    30.5 2215.72    36.6    2213    39.2 2212.03
      412211.593    44.2 2210.99    52.9 2210.83    64.3 2211.07    70.4 2211.54
    74.4 2212.56    78.8 2214.42    83.1 2215.23    91.7 2215.38      96 2215.17
   113.4 2215.08   134.9 2215.94   143.5 2216.54   147.8 2216.47   156.5  2216.9
   186.7 2219.54   199.2 2220.28     231 2223.26   241.1 2223.94   252.9 2225.41
#Mann= 4 ,-1,0
       0      .1       0      41    .045       0    70.4      .1       0
  203.31     .05       0
Bank Sta=41,70.4
XS Rating Curve= 0 ,0
Exp/Cntr(USF)=0,0
Exp/Cntr=0.3,0.1

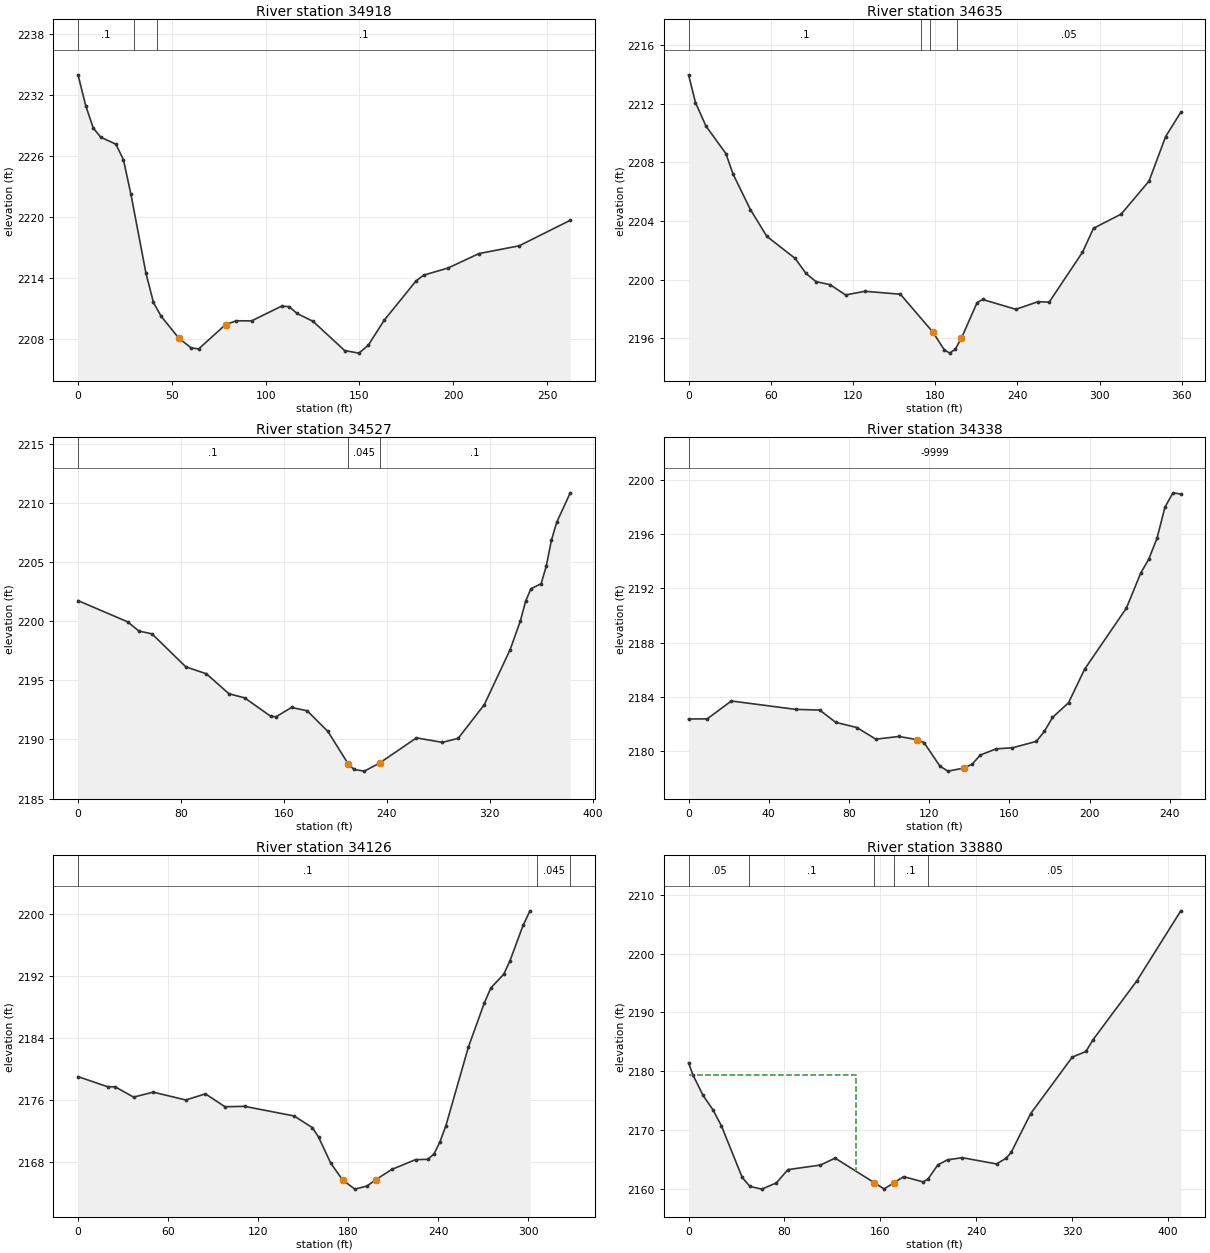
Type RM Length L Ch R = 1 ,34918   ,280.2,283.1,275.5
XS GIS Cut Line= 3
2163871.61812714613917.105304764 2163861.2590209614029.555711902
2163908.59859041614171.188244567
#Sta/Elev= 30
       0 2233.94     4.1 2230.91     8.1 2228.72    12.1 2227.81    20.2 2227.12
    24.2 2225.59    28.2 2222.19    36.2 2214.44    40.2 2211.56    44.3  2210.2
    53.6 2208.08    60.3 2207.09    64.3    2207    78.62209.378    84.4 2209.76
    92.5 2209.75   108.5  2211.2   112.5 2211.15   116.7 2210.48   125.2 2209.71
   142.1 2206.83   149.7 2206.58   154.7 2207.36   163.1  2209.8     180 2213.65
   184.2 2214.25   197.1 2214.94   213.7 2216.37   235.1 2217.13   262.3 2219.64
#Mann= 3 ,-1,0
       0      .1       0    29.7    .045       0    42.2      .1       0
Bank Sta=53.6,78.6
XS Rating Curve= 0 ,0
Exp/Cntr(USF)=0,0
Exp/Cntr=0.3,0.1

Type RM Length L Ch R = 1 ,34635   ,111,108.2,105.2
XS GIS Cut Line= 4
 2163734.3513484613897.4451232022163643.52840589613998.465042624
2163641.44888841614080.0586836712163663.73725135614220.158616172
#Sta/Elev= 30
       0 2213.97       5 2212.08    12.7 2210.47    27.2  2208.6    32.5 2207.19
    45.1 2204.78    57.1 2202.95    77.8 2201.44    85.7 2200.42      93 2199.86
   103.3 2199.65   114.6 2198.95   128.7  2199.2   154.6    2199   178.32196.417
   186.6 2195.21   190.6 2194.98   194.6 2195.24   199.22196.012   210.6 2198.43
   214.6 2198.64   238.9 2197.97   255.1 2198.49   263.2 2198.46   287.5 2201.86
   295.6  2203.5   315.8 2204.47   336.1 2206.72   348.2 2209.75   359.3 2211.42
#Mann= 4 ,-1,0
       0      .1       0  169.77     .05       0   176.5    .045       0
     196     .05       0
Bank Sta=178.3,199.2
XS Rating Curve= 0 ,0
Exp/Cntr(USF)=0,0
Exp/Cntr=0.3,0.1

Type RM Length L Ch R = 1 ,34527   ,181.3,189,187.9
XS GIS Cut Line= 4
2163567.36298696613845.9280295712163519.13998889613955.386580743
2163550.52320985 614164.352905712163555.88132075614215.637681434
#Sta/Elev= 30
       0 2201.73    38.5 2199.94    47.3 2199.16    57.5 2198.92    83.8 2196.13
    99.7 2195.55   117.3 2193.86   129.5 2193.51   149.7 2191.96   153.8 2191.91
   165.9  2192.7   178.1 2192.42   194.2 2190.67     210 2187.93   214.5 2187.46
   222.5 2187.32   234.3    2188     263 2190.13   283.2 2189.75   295.4 2190.09
   315.7 2192.93   335.8 2197.59   343.8 2200.03   347.8 2201.66   351.9 2202.73
   359.9 2203.16   363.9 2204.66   367.9 2206.84     372 2208.35   382.5 2210.84
#Mann= 3 ,-1,0
       0      .1       0     210    .045       0   234.3      .1       0
Bank Sta=210,234.3
XS Rating Curve= 0 ,0
Exp/Cntr(USF)=0,0
Exp/Cntr=0.3,0.1

Type RM Length L Ch R = 1 ,34338   ,210.4,211.6,210
XS GIS Cut Line= 2
2163354.73954557613959.8864790272163366.32199619614205.161903871
#Sta/Elev= 30
       0 2182.36     9.3 2182.37    21.3 2183.69    53.4 2183.07    65.4 2183.02
    73.4 2182.11    83.9 2181.73    93.4 2180.87   104.9 2181.07     1142180.833
   117.4 2180.62   125.4 2178.87   129.4 2178.51   137.32178.735   141.4 2179.02
   145.5  2179.7   153.5 2180.16   161.5 2180.23   173.5 2180.71   177.5 2181.46
   181.5 2182.47   189.5 2183.56   197.5 2186.03   218.4 2190.56   225.5 2193.13
   229.5 2194.16   233.6 2195.69   237.6    2198   241.6 2199.06   245.5 2198.97
#Mann= 1 ,-1,0
       0   -9999       0
Bank Sta=114,137.3
XS Rating Curve= 0 ,0
Exp/Cntr(USF)=0,0
Exp/Cntr=0.3,0.1

Type RM Length L Ch R = 1 ,34126   ,246.4,245.6,244.4
XS GIS Cut Line= 6
2163222.45850196613947.1002987792163168.74404186614073.067445149
2163160.10866692614083.3534374082163167.43086072614138.269890944
2163173.65472545614180.3725053222163193.42464873614229.431203815
#Sta/Elev= 30
       0 2179.06    19.7 2177.76    24.7 2177.75      37 2176.42    50.1 2177.06
    71.8 2176.05    84.9 2176.84    97.9 2175.18     111 2175.23     144 2173.99
   156.2 2172.48   160.3 2171.27   168.4 2167.91   176.4 2165.72   184.5 2164.56
   192.6 2164.96   198.3 2165.76     209 2167.09   224.9 2168.36     233  2168.4
   237.2 2169.09   241.1 2170.61   245.1 2172.71   260.1 2182.85   270.8 2188.58
   275.1 2190.49   283.7 2192.26   287.8 2193.97   296.6 2198.57   301.2 2200.43
#Mann= 3 ,-1,0
       0      .1       0   306.1    .045       0     328      .1       0
Bank Sta=176.4,198.3
XS Rating Curve= 0 ,0
Exp/Cntr(USF)=0,0
Exp/Cntr=0.3,0.1

Type RM Length L Ch R = 1 ,33880   ,219.9,214.3,211.8
XS GIS Cut Line= 3
2162891.73897394613993.3250273062162949.35172221614278.188060405
2163029.36942813614367.807891043
#Sta/Elev= 30
       0 2181.42     3.6  2179.4    12.1  2175.9    20.3 2173.47    27.4 2170.73
    44.7    2162    51.2 2160.44    61.1 2159.99    73.3 2161.06    82.9  2163.3
     110 2164.08   122.3 2165.26   154.9 2161.09   163.1 2160.03   171.52161.074
   179.4 2162.11   195.7 2161.22   199.8 2161.69     208 2164.11   216.1 2164.97
   228.4 2165.33     257 2164.27   265.1 2165.25   269.2 2166.23   285.5 2172.82
   320.2 2182.41   331.6 2183.37   337.5 2185.36   374.1 2195.36   410.8 2207.26
#Mann= 5 ,-1,0
       0     .05       0      50      .1       0   154.9    .045       0
   171.5      .1       0     200     .05       0
#XS Ineff= 2 , 0
          139.44 2179.32
Permanent Ineff=
       F       F
Bank Sta=154.9,171.5
XS Rating Curve= 0 ,0
Exp/Cntr(USF)=0,0
Exp/Cntr=0.3,0.1