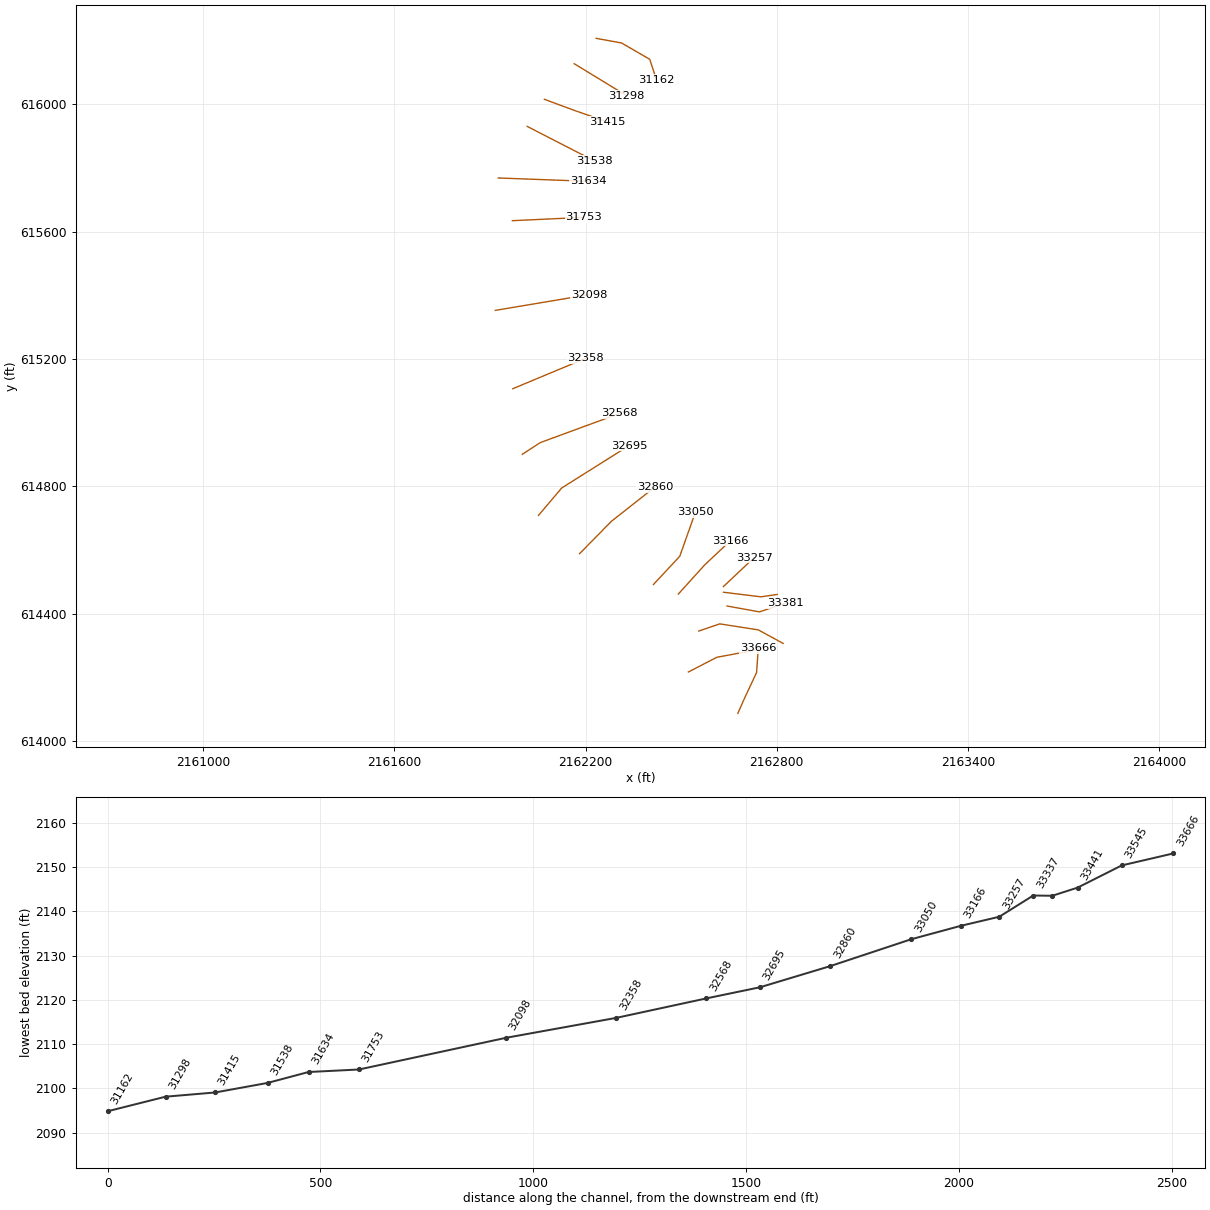
HEC-RAS study LFRFLIKANA.prj: LFRFLIKANA

--- LFRFLIKANA.g01 (geometry) --- (continued)

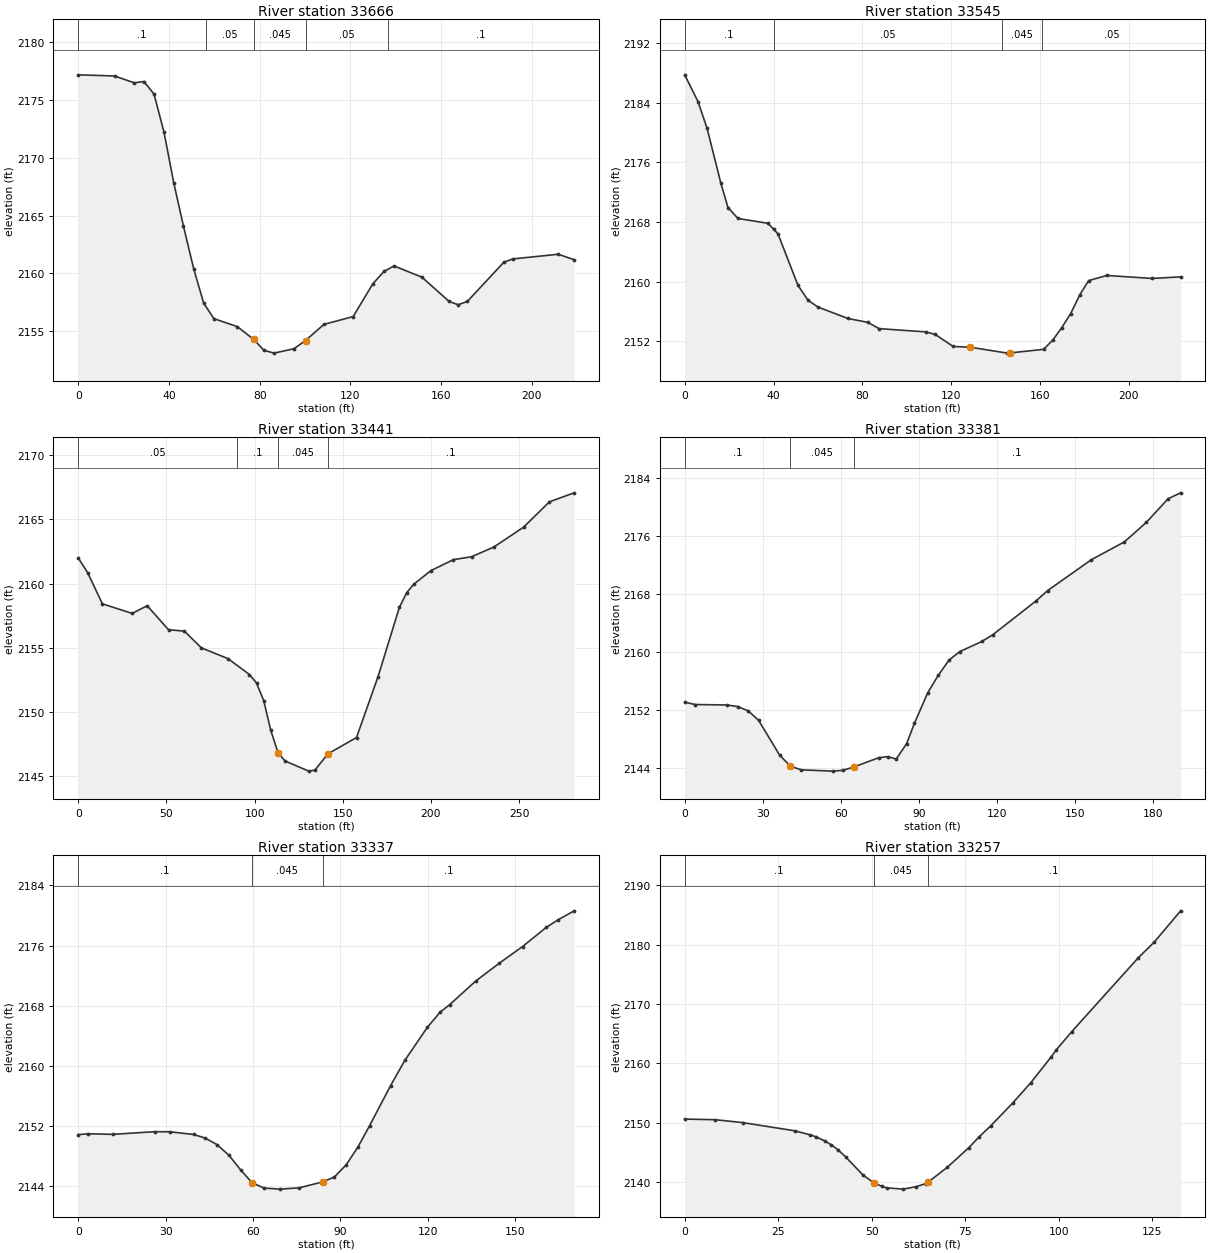
Type RM Length L Ch R = 1 ,33666   ,139.5,121.6,111.2
XS GIS Cut Line= 4
2162678.20139732614086.5541120122162696.77174743614129.118659509
2162736.99861463 614214.996241172162742.29627375 614292.15126225
#Sta/Elev= 30
       0 2177.16      16 2177.06    24.7 2176.47      29 2176.58    33.4  2175.5
    37.8 2172.22    42.1 2167.84    46.4 2164.08    50.9 2160.41    55.3 2157.44
    59.8  2156.1    70.1 2155.41    77.4  2154.3    81.8 2153.37    86.3 2153.12
    95.1  2153.5   100.2 2154.21   108.3  2155.6   121.2 2156.28   129.9 2159.12
   134.8 2160.18   139.2 2160.65   151.5 2159.68   163.5 2157.58   167.5  2157.3
   171.5 2157.58   187.6 2160.97   191.6 2161.26   211.6 2161.66   218.6 2161.19
#Mann= 5 ,-1,0
       0      .1       0   56.44     .05       0    77.4    .045       0
   100.2     .05       0  136.44      .1       0
Bank Sta=77.4,100.2
XS Rating Curve= 0 ,0
Exp/Cntr(USF)=0,0
Exp/Cntr=0.3,0.1

Type RM Length L Ch R = 1 ,33545   ,103.2,103.6,99
XS GIS Cut Line= 3
2162522.84908445614216.5580399582162612.17778856614262.736437845
2162732.84634272614285.338056004
#Sta/Elev= 30
       0 2187.77       6 2184.18    10.1 2180.57    16.3 2173.21    19.5 2169.94
      24 2168.48    37.5 2167.83      40 2167.06      42 2166.42      51 2159.51
    55.5 2157.51      60 2156.59    73.5 2155.05    82.5 2154.53    87.5 2153.69
   108.7 2153.25   112.8 2152.91   120.9 2151.29   128.5  2151.2   145.3  2150.4
   146.32150.422   161.6 2150.91   165.7 2152.14   169.7 2153.79   173.8 2155.71
   177.9 2158.23   181.9 2160.14   190.1 2160.83   210.4 2160.43   223.3 2160.64
#Mann= 4 ,-1,0
       0      .1       0      40     .05       0   142.7    .045       0
     161     .05       0
Bank Sta=128.5,146.3
XS Rating Curve= 0 ,0
Exp/Cntr(USF)=0,0
Exp/Cntr=0.3,0.1

Type RM Length L Ch R = 1 ,33441   ,60.3,59.5,58.9
XS GIS Cut Line= 4
2162555.18763927614345.0708760432162621.33715651614367.750710526
2162742.29627375614348.8508484572162820.29600451614306.363958526
#Sta/Elev= 30
       0    2162     5.3 2160.86    13.7 2158.42    30.6 2157.67    39.1 2158.27
    51.2  2156.4    60.2 2156.29    69.9 2154.98    84.9 2154.15    97.1 2152.91
   101.1 2152.25   105.2 2150.86   109.2 2148.55   113.3 2146.81   117.3 2146.17
   130.7 2145.38   134.2 2145.46   141.6 2146.73   157.8    2148     170 2152.74
   182.1 2158.14   186.2 2159.28   190.2 2159.94     200 2161.01   212.7 2161.86
     223 2162.09   235.5 2162.83   252.5 2164.39   267.2 2166.37   281.2 2167.07
#Mann= 4 ,-1,0
       0     .05       0   89.93      .1       0   113.3    .045       0
   141.6      .1       0
Bank Sta=113.3,141.6
XS Rating Curve= 0 ,0
Exp/Cntr(USF)=0,0
Exp/Cntr=0.3,0.1

Type RM Length L Ch R = 1 ,33381   ,43.7,44.6,45.6
XS GIS Cut Line= 3
2162644.21112851  614423.80190112162746.01523555614405.431235169
2162828.68323224614432.987234065
#Sta/Elev= 30
       0 2153.05       4 2152.72    16.2 2152.66    20.3 2152.44    24.4 2151.85
    28.4 2150.55    36.5 2145.74    40.6 2144.23    44.7 2143.72    56.9 2143.54
    60.8 2143.65      65 2144.11    74.5 2145.38      78 2145.54    81.3 2145.21
    85.3 2147.33    88.3 2150.13    93.4 2154.33    97.5 2156.77   101.6 2158.85
   105.7 2160.01   114.2 2161.41   118.4 2162.33   135.2 2167.05   139.5 2168.43
   156.3 2172.68     169 2175.14   177.4 2177.82   185.8 2181.09   190.6  2181.9
#Mann= 3 ,-1,0
       0      .1       0    40.6    .045       0      65      .1       0
Bank Sta=40.6,65
XS Rating Curve= 0 ,0
Exp/Cntr(USF)=0,0
Exp/Cntr=0.3,0.1

Type RM Length L Ch R = 1 ,33337   ,66.7,80,93.6
XS GIS Cut Line= 3
2162632.89150117614467.1160698852162750.69339646614452.649170464
2162801.67199442614460.227070161
#Sta/Elev= 30
       0 2150.85     3.3 2150.96    11.9 2150.89    26.2 2151.24    31.5 2151.23
    39.6 2150.87    43.6 2150.39    47.6 2149.53    51.7 2148.12    55.7 2146.18
    59.7 2144.44    63.8 2143.74    69.3  2143.6    75.8 2143.77    83.9 2144.56
    87.9 2145.21      92 2146.85      96  2149.2     100 2152.04   107.2 2157.37
   112.1 2160.74   119.8 2165.12   124.2 2167.15   127.5 2168.15   136.4 2171.28
   144.4 2173.63   152.5 2175.88   160.6 2178.42   164.7 2179.44   170.2 2180.63
#Mann= 3 ,-1,0
       0      .1       0    59.7    .045       0    83.9      .1       0
Bank Sta=59.7,83.9
XS Rating Curve= 0 ,0
Exp/Cntr(USF)=0,0
Exp/Cntr=0.3,0.1

Type RM Length L Ch R = 1 ,33257   ,90.2,90.5,90.5
XS GIS Cut Line= 2
2162632.89150117614485.0274691682162729.33749731614575.962265527
#Sta/Elev= 30
       0  2150.6     8.1  2150.5    15.5 2150.01    29.4 2148.63    33.6 2147.94
    35.2 2147.59    37.5  2146.9    39.2 2146.26      41 2145.42      43 2144.25
    47.7 2141.15    50.5  2139.9    52.7 2139.25      54    2139    58.5 2138.79
    61.9 2139.21    64.4  2139.7      65 2139.93    70.2 2142.46      76  2145.8
    78.8 2147.65    81.9  2149.5    87.7 2153.31    92.5  2156.7      98 2161.09
    99.3 2162.23   103.5 2165.35   121.3 2177.82   125.5 2180.41   132.6 2185.72
#Mann= 3 ,-1,0
       0      .1       0    50.5    .045       0      65      .1       0
Bank Sta=50.5,65
XS Rating Curve= 0 ,0
Exp/Cntr(USF)=0,0
Exp/Cntr=0.3,0.1

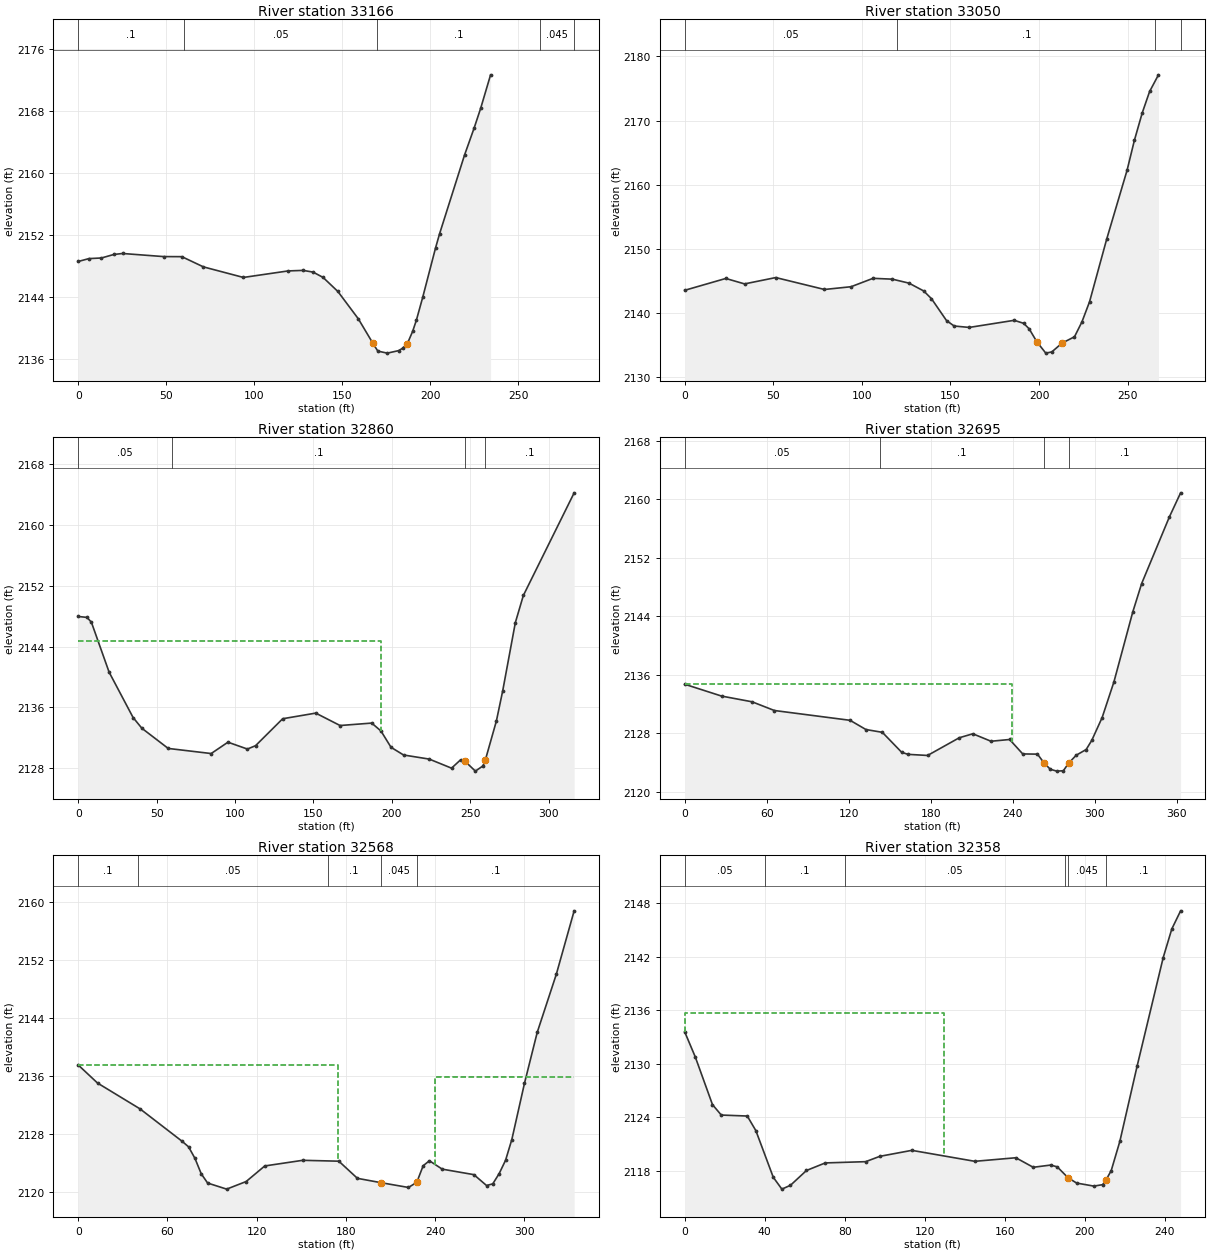
Type RM Length L Ch R = 1 ,33166   ,109.5,116,121.8
XS GIS Cut Line= 3
2162491.28352219614461.4962655112162574.33500352614553.228566438
2162654.93630029614629.007563404
#Sta/Elev= 30
       0 2148.56     6.1 2148.93    13.2 2149.01    20.2 2149.46    25.2 2149.59
    48.5 2149.19    58.9 2149.18    71.2 2147.86    93.9  2146.5   119.3 2147.34
   127.8 2147.41   133.5 2147.19   139.2  2146.5   147.6 2144.69   159.2 2141.17
   167.5 2138.01   170.3    2137   175.7 2136.74   182.1 2137.06   184.4 2137.37
   187.12137.967   190.1 2139.55   192.2 2140.97   195.8 2143.92   203.1 2150.29
   205.4 2152.13   219.6 2162.29   225.1  2165.8   228.8 2168.34   234.4 2172.63
#Mann= 5 ,-1,0
       0      .1       0      60     .05       0     170      .1       0
   262.3    .045       0   281.9      .1       0
Bank Sta=167.5,187.1
XS Rating Curve= 0 ,0
Exp/Cntr(USF)=0,0
Exp/Cntr=0.3,0.1

Type RM Length L Ch R = 1 ,33050   ,196.8,190.4,183.5
XS GIS Cut Line= 3
2162413.12901023614491.4651141822162495.80040666614580.095665362
 2162544.7123047614717.875659846
#Sta/Elev= 30
       0 2143.52    23.2 2145.37    33.8 2144.52    51.4 2145.51    78.9 2143.65
    93.9 2144.08   106.3 2145.39   117.2 2145.26   126.6 2144.64   134.9 2143.42
   139.3 2142.21   147.8 2138.79   152.1 2137.95   160.6 2137.73     186 2138.84
   191.3 2138.37   194.4 2137.52   198.8 2135.47   203.8 2133.72   207.2 2133.91
     2132135.287     220 2136.27   224.2 2138.59   228.5 2141.73   238.2 2151.53
   249.7 2162.27   253.8 2166.91   258.2 2171.17   262.4 2174.54   267.4 2177.14
#Mann= 4 ,-1,0
       0     .05       0     120      .1       0   265.7    .045       0
   279.9      .1       0
Bank Sta=198.8,213
XS Rating Curve= 0 ,0
Exp/Cntr(USF)=0,0
Exp/Cntr=0.3,0.1

Type RM Length L Ch R = 1 ,32860   ,166.6,164.9,163.2
XS GIS Cut Line= 3
2162181.23550963614588.2244804032162281.59377722614690.283735576
2162417.67278412614797.445953508
#Sta/Elev= 30
       0 2147.95     5.6 2147.83     8.4  2147.2    19.7 2140.64      35 2134.68
    40.6 2133.27    57.4 2130.62    84.8 2129.95    95.5 2131.44   107.9 2130.54
   113.1 2130.98   130.4 2134.52   151.5 2135.26     167 2133.63   187.2 2133.95
   193.1 2132.91   199.5 2130.77   207.5 2129.76   223.9 2129.22   238.1 2128.03
   243.9 2129.13   246.42128.994   253.3 2127.64   258.1 2128.32   259.62129.055
   266.7 2134.22   270.7 2138.15   278.8 2147.15   283.9 2150.71   316.3 2164.19
#Mann= 4 ,-1,0
       0     .05       0      60      .1       0   246.4    .045       0
   259.6      .1       0
#XS Ineff= 2 , 0
          193.04  2144.7
Permanent Ineff=
       F       F
Bank Sta=246.4,259.6
XS Rating Curve= 0 ,0
Exp/Cntr(USF)=0,0
Exp/Cntr=0.3,0.1

Type RM Length L Ch R = 1 ,32695   ,130.8,126.6,123.7
XS GIS Cut Line= 3
2162052.34061854614708.5505343052162125.10508751614794.544906719
2162336.78354268614927.788934306
#Sta/Elev= 30
       0 2134.73      27 2133.11    49.3 2132.33    65.6 2131.14     121  2129.8
   132.6 2128.54   144.6 2128.16   158.8 2125.42   163.5 2125.15   177.7    2125
   200.9 2127.42   210.8 2127.96   224.1 2126.94   237.7 2127.18   247.3 2125.21
   258.1 2125.18   262.8    2124   267.5 2123.11   272.2 2122.86     277 2122.91
   280.9 2123.95   286.4 2125.03   293.7 2125.81   297.8 2127.06   305.4 2130.18
     314 2135.04   327.8  2144.6   334.3 2148.48   354.6 2157.59   362.8 2160.87
#Mann= 4 ,-1,0
       0     .05       0  142.65      .1       0   262.8    .045       0
   280.9      .1       0
#XS Ineff= 2 , 0
          239.55  2134.7
Permanent Ineff=
       F       F
Bank Sta=262.8,280.9
XS Rating Curve= 0 ,0
Exp/Cntr(USF)=0,0
Exp/Cntr=0.3,0.1

Type RM Length L Ch R = 1 ,32568   ,210,210.9,210.7
XS GIS Cut Line= 3
2162001.31099096614900.3841343062162058.01057716614937.238865341
2162307.48875648615028.903196376
#Sta/Elev= 30
       0 2137.48      13 2134.98    41.6 2131.41    69.9 2126.93    74.2 2126.17
    78.5 2124.57    82.7 2122.45      87 2121.17    99.8 2120.33   112.9 2121.38
   125.4 2123.53   150.9 2124.31   175.2 2124.19   187.7 2121.82   203.3 2121.23
     222 2120.56   227.6 2121.27   231.9 2123.56   236.1 2124.25   244.7 2123.09
     266 2122.33   274.5 2120.83   278.7 2121.06     283 2122.48   287.3 2124.32
   291.5 2127.18     300 2134.94   308.6    2142   321.4    2150   333.4 2158.77
#Mann= 5 ,-1,0
       0      .1       0      40     .05       0  167.62      .1       0
   203.3    .045       0   227.6      .1       0
#XS Ineff= 2 , 0
           174.7 2137.54  240.17         2135.78
Permanent Ineff=
       F       F
Bank Sta=203.3,227.6
XS Rating Curve= 0 ,0
Exp/Cntr(USF)=0,0
Exp/Cntr=0.3,0.1

Type RM Length L Ch R = 1 ,32358   ,266.1,259.2,257
XS GIS Cut Line= 2
2161971.32889849615106.322838626  2162200.227228615201.872141309
#Sta/Elev= 30
       0 2133.59     5.3 2130.77    13.9 2125.42    18.3 2124.25    31.3 2124.14
    35.6  2122.5    44.3 2117.27    48.6 2115.94    52.9 2116.37    60.9 2118.03
    70.3 2118.88    90.5 2119.02    97.6 2119.62   113.6 2120.29   145.1 2119.06
   165.6 2119.46   174.3 2118.39     183 2118.64   186.3 2118.44   191.72117.219
     196 2116.62   204.6 2116.28     209 2116.44   210.8 2117.01   213.3 2118.02
   217.6 2121.29   226.3 2129.79   239.3 2141.92   243.6 2145.13     248 2147.16
#Mann= 6 ,-1,0
       0     .05       0      40      .1       0      80     .05       0
     190      .1       0   191.7    .045       0   210.8      .1       0
#XS Ineff= 2 , 0
          129.86 2135.71
Permanent Ineff=
       F       F
Bank Sta=191.7,210.8
XS Rating Curve= 0 ,0
Exp/Cntr(USF)=0,0
Exp/Cntr=0.3,0.1

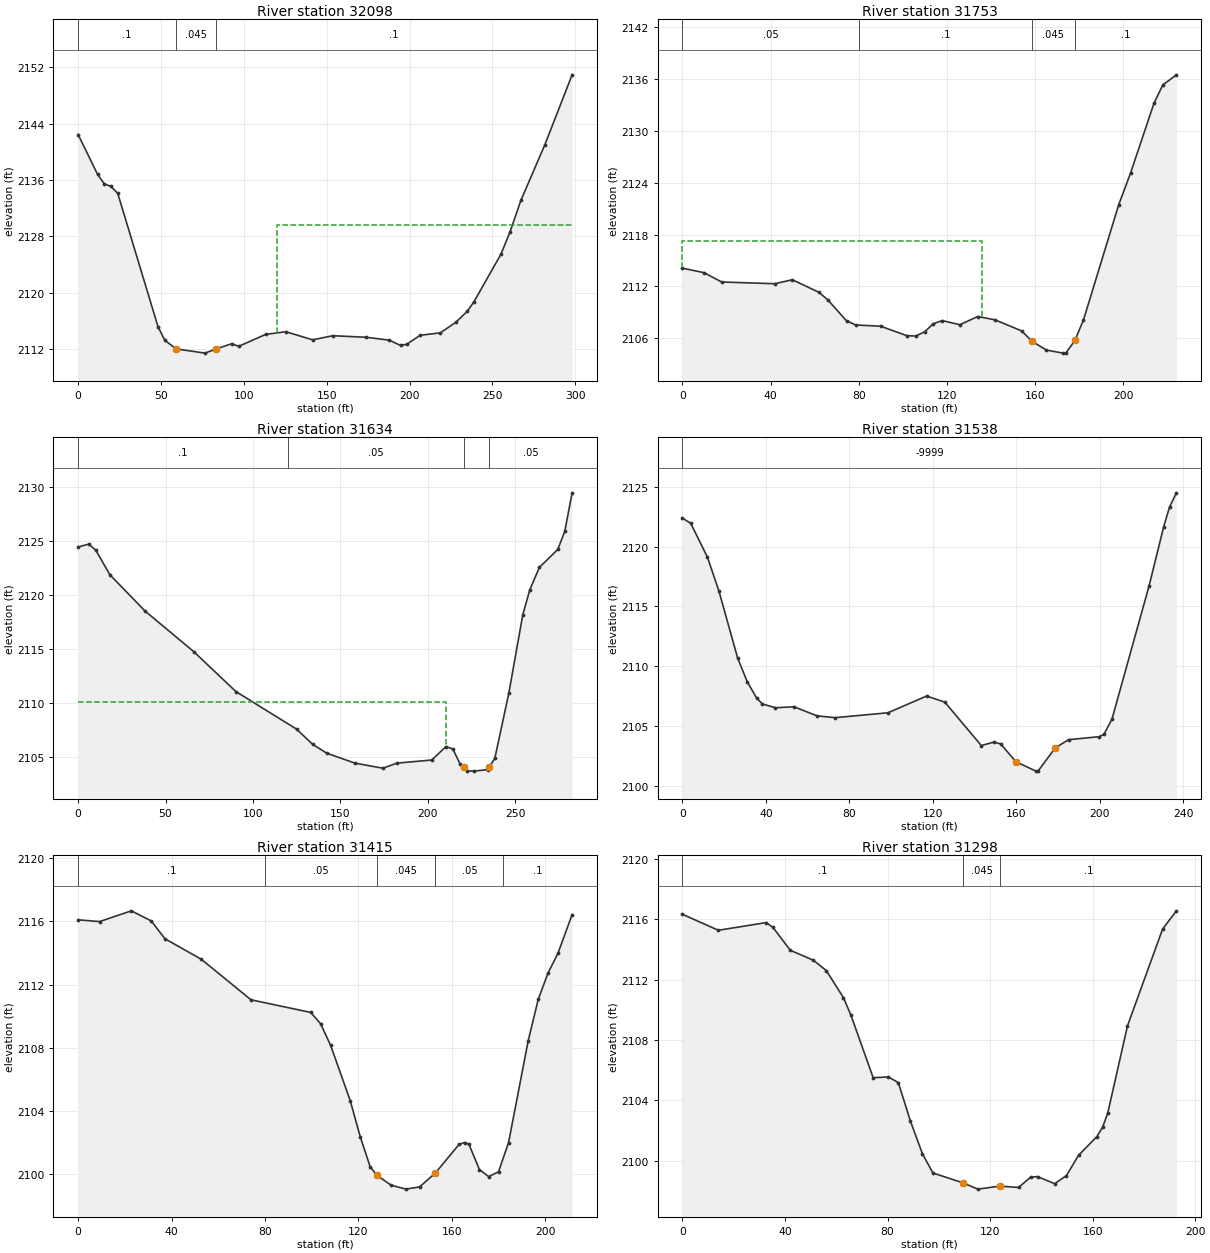
Type RM Length L Ch R = 1 ,32098   ,349.1,345.7,343.1
XS GIS Cut Line= 2
2161916.64015723615352.5544435532162210.63801164  615401.9040834
#Sta/Elev= 30
       0 2142.45    11.7 2136.81    15.8 2135.45    19.8 2135.09    23.9 2134.11
    48.2 2115.19    52.3 2113.25    59.2 2112.03    76.6 2111.43    83.42112.039
    92.8 2112.77    96.9 2112.39   113.1 2114.08   125.3 2114.47   141.5 2113.32
   153.7  2113.9   173.9 2113.68   187.7 2113.27   194.6 2112.52   198.3 2112.69
   206.4 2113.96   218.6 2114.31   227.8 2115.78   234.8 2117.35   238.8 2118.69
   255.1 2125.44   260.6 2128.61   267.2 2133.11   281.5 2140.91   298.1 2150.92
#Mann= 3 ,-1,0
       0      .1       0    59.2    .045       0    83.4      .1       0
#XS Ineff= 2 , 0
                             120          2129.6
Permanent Ineff=
       F       F
Bank Sta=59.2,83.4
XS Rating Curve= 0 ,0
Exp/Cntr(USF)=0,0
Exp/Cntr=0.3,0.1

Type RM Length L Ch R = 1 ,31753   ,120.4,118.6,117.4
XS GIS Cut Line= 2
2161970.36594017615634.3393076842162194.36430544615644.839231056
#Sta/Elev= 30
       0  2114.1     9.8 2113.58    17.8  2112.5    41.9  2112.3    49.9 2112.76
    61.9 2111.31    65.9 2110.45    74.5 2107.99    78.7 2107.52    89.9 2107.38
   101.9 2106.28   105.9 2106.24   109.9 2106.73   113.9 2107.67   117.9 2108.03
   125.9 2107.55     134  2108.5   141.8 2108.12     154 2106.83   158.6 2105.64
   165.1 2104.62   172.7 2104.26     174 2104.26   178.12105.729     182  2108.1
     198 2121.45   203.4 2125.14     214  2133.2     218 2135.32   224.2  2136.5
#Mann= 4 ,-1,0
       0     .05       0      80      .1       0   158.6    .045       0
   178.1      .1       0
#XS Ineff= 2 , 0
          136.06 2117.29
Permanent Ineff=
       F       F
Bank Sta=158.6,178.1
XS Rating Curve= 0 ,0
Exp/Cntr(USF)=0,0
Exp/Cntr=0.3,0.1

Type RM Length L Ch R = 1 ,31634   ,102.2,96.2,90.5
XS GIS Cut Line= 2
2161926.03293038615768.5049952122162208.36420327 615758.00507184
#Sta/Elev= 30
       0 2124.44     6.1  2124.7    10.1 2124.14    18.2 2121.86    38.2 2118.52
    66.2 2114.74    90.2 2111.06   124.9 2107.58   134.2 2106.16   142.2 2105.35
   158.3 2104.43   174.3 2103.96   182.3 2104.43   202.3 2104.72   210.3 2105.96
   214.3 2105.74   218.3 2104.39   220.42104.043   222.3 2103.71   226.3 2103.69
   234.3 2103.83   235.22104.081   238.3 2104.87   246.3  2110.9   254.3 2118.16
   258.3 2120.47   263.8 2122.55   274.3 2124.21   278.3 2125.88   282.5 2129.45
#Mann= 4 ,-1,0
       0      .1       0     120     .05       0   220.4    .045       0
   235.2     .05       0
#XS Ineff= 2 , 0
          210.59 2110.06
Permanent Ineff=
       F       F
Bank Sta=220.4,235.2
XS Rating Curve= 0 ,0
Exp/Cntr(USF)=0,0
Exp/Cntr=0.3,0.1

Type RM Length L Ch R = 1 ,31538   ,120.5,123.4,124.8
XS GIS Cut Line= 2
2162016.58511887615930.6773143772162227.03748957615822.423037362
#Sta/Elev= 30
       0 2122.38       4 2121.93      12  2119.1    17.5 2116.26    26.5 2110.65
      31 2108.71    35.5 2107.34    38.3 2106.84    44.5 2106.52    53.5  2106.6
    64.5 2105.84    73.2 2105.69    98.5  2106.1     117  2107.5   125.7 2106.99
   143.2 2103.36   149.3 2103.65   152.5 2103.49   159.82102.003   169.4 2101.22
   170.5 2101.25   178.62103.157     185 2103.85   199.8  2104.1     202 2104.31
   205.8 2105.56   223.6 2116.72   230.6 2121.66   233.4 2123.31   236.7 2124.49
#Mann= 1 ,-1,0
       0   -9999       0
Bank Sta=159.8,178.6
XS Rating Curve= 0 ,0
Exp/Cntr(USF)=0,0
Exp/Cntr=0.3,0.1

Type RM Length L Ch R = 1 ,31415   ,121,116.3,113.2
XS GIS Cut Line= 3
2162070.80315483616015.6808723162162166.52855937615980.192049091
2162269.86355524615944.369250525
#Sta/Elev= 30
       0  2116.1     9.2 2115.99    22.8 2116.67    31.3 2116.03    37.2  2114.9
    52.8  2113.6      74 2111.04    99.6 2110.24   103.8 2109.53   108.1 2108.16
   116.5 2104.66   120.8 2102.37     125 2100.49   127.8 2099.95     134 2099.31
   140.3 2099.06   146.2  2099.2   152.9 2100.07   163.1 2101.89   165.5 2102.01
   167.3 2101.91   171.8  2100.3   175.8 2099.85     180 2100.16   184.3 2102.01
   192.7 2108.45     197 2111.07   201.2 2112.74   205.4 2113.97   211.5 2116.43
#Mann= 5 ,-1,0
       0      .1       0      80     .05       0   127.8    .045       0
   152.9     .05       0  182.09      .1       0
Bank Sta=127.8,152.9
XS Rating Curve= 0 ,0
Exp/Cntr(USF)=0,0
Exp/Cntr=0.3,0.1

Type RM Length L Ch R = 1 ,31298   ,134.5,136.1,135.6
XS GIS Cut Line= 2
2162164.25411523616127.5589273142162328.75291472616027.226326206
#Sta/Elev= 30
       0 2116.34      14 2115.28    32.7 2115.79    35.3 2115.47    42.1 2113.95
    51.1 2113.29    56.1 2112.61    62.8 2110.81    65.7 2109.66    74.4  2105.5
    80.3 2105.55    84.2 2105.18    88.9 2102.64    93.6 2100.46    97.7 2099.18
   109.4 2098.53   115.2 2098.11   123.9 2098.31   131.1 2098.22   135.8  2098.9
   138.5 2098.94   145.2 2098.47   149.8 2099.01   154.5 2100.35   161.7  2101.6
   163.9 2102.22   165.9 2103.15   173.6 2108.94   187.3 2115.36   192.7 2116.57
#Mann= 3 ,-1,0
       0      .1       0   109.4    .045       0   123.9      .1       0
Bank Sta=109.4,123.9
XS Rating Curve= 0 ,0
Exp/Cntr(USF)=0,0
Exp/Cntr=0.3,0.1

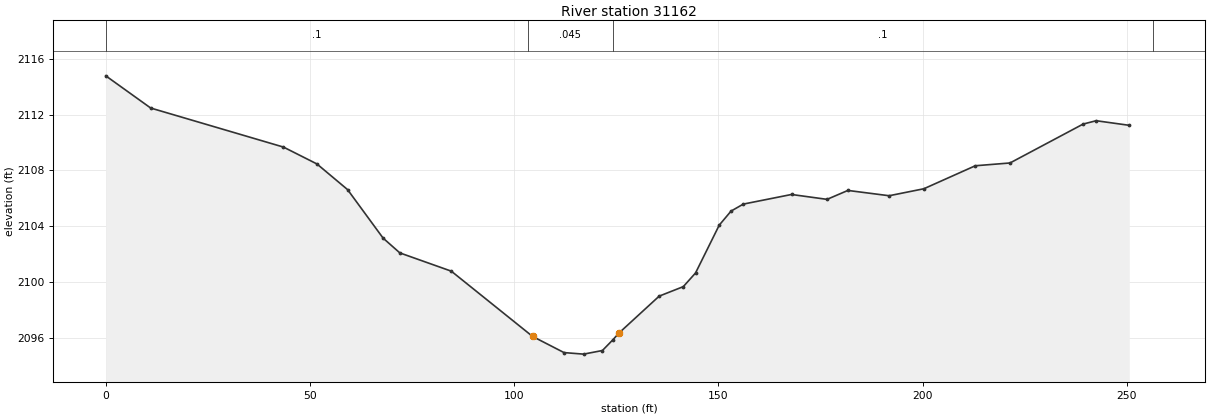
Type RM Length L Ch R = 1 ,31162   ,148.6,151.5,153.8
XS GIS Cut Line= 4
2162233.34696267616207.1984459762162313.06008636616192.619494977
2162401.55025578616141.3046570722162422.65817021616077.388475628
#Sta/Elev= 30
       0 2114.78      11 2112.47    43.5 2109.67    51.7 2108.46    59.2 2106.62
    67.9 2103.14      72 2102.08    84.6 2100.77   104.52096.089   112.2 2094.93
     117 2094.82   121.6 2095.08   124.2 2095.86   125.62096.319   135.5 2098.98
   141.4 2099.66   144.4 2100.64   150.2 2104.07   153.1 2105.08   156.1 2105.58
   167.9 2106.27   176.6 2105.92   181.7 2106.56   191.8 2106.18   200.3 2106.68
   212.9 2108.33   221.4 2108.53   239.3 2111.32   242.5 2111.56   250.6 2111.23
#Mann= 4 ,-1,0
       0      .1       0   103.3    .045       0   124.2      .1       0
  256.42     .05       0
Bank Sta=104.5,125.6
XS Rating Curve= 0 ,0
Exp/Cntr(USF)=0,0
Exp/Cntr=0.3,0.1