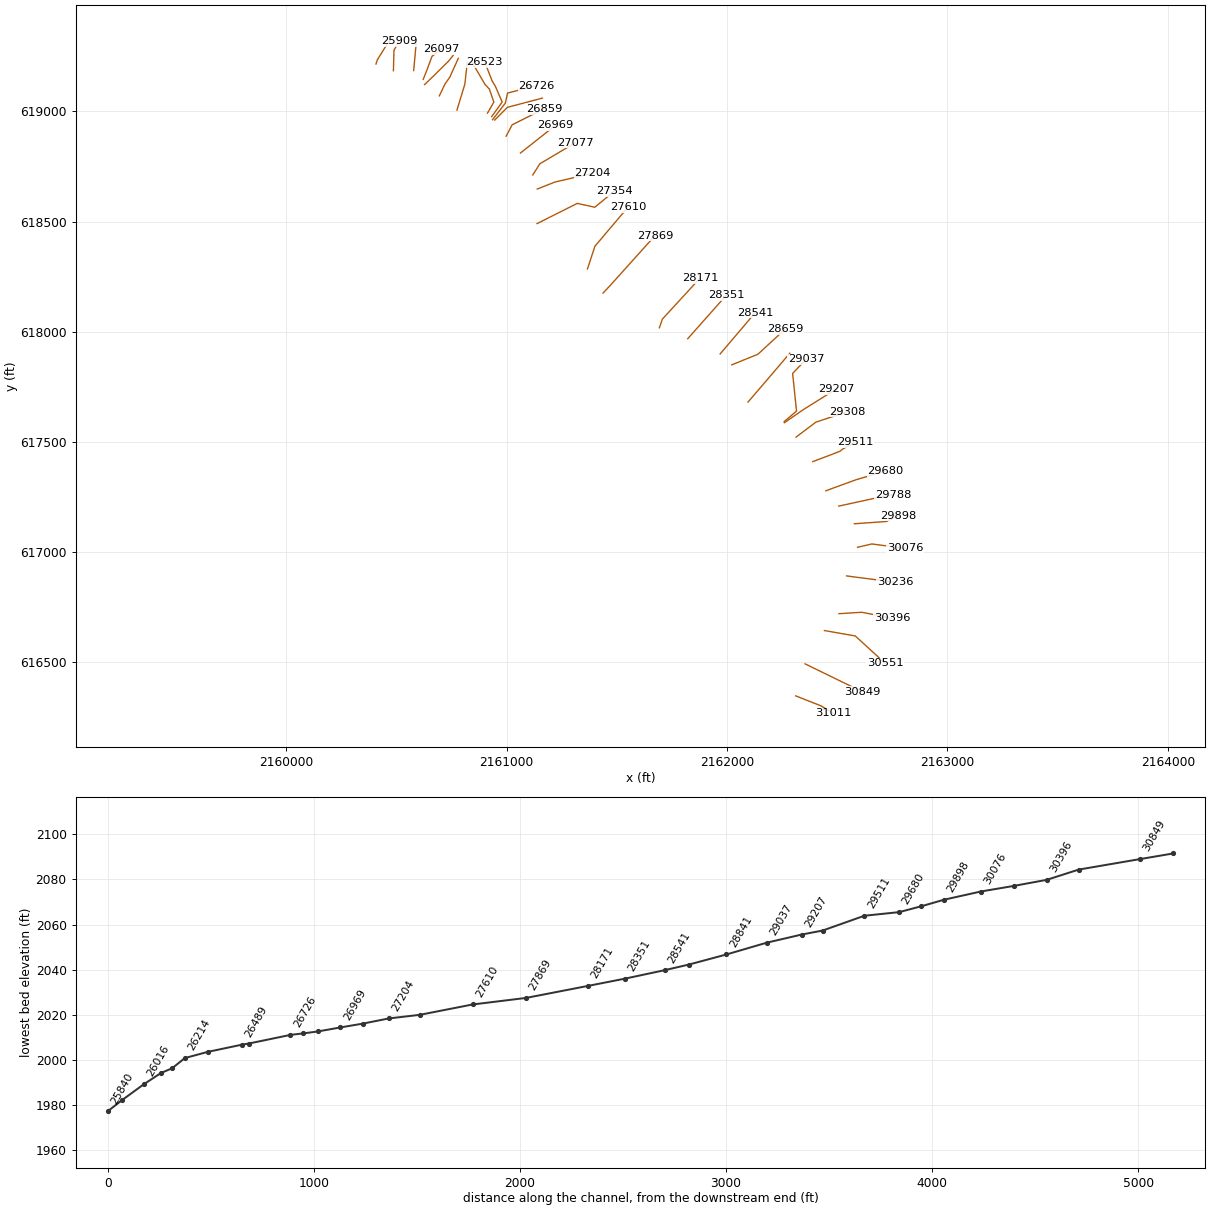
HEC-RAS study LFRFLIKANA.prj: LFRFLIKANA

--- LFRFLIKANA.g01 (geometry) --- (continued)

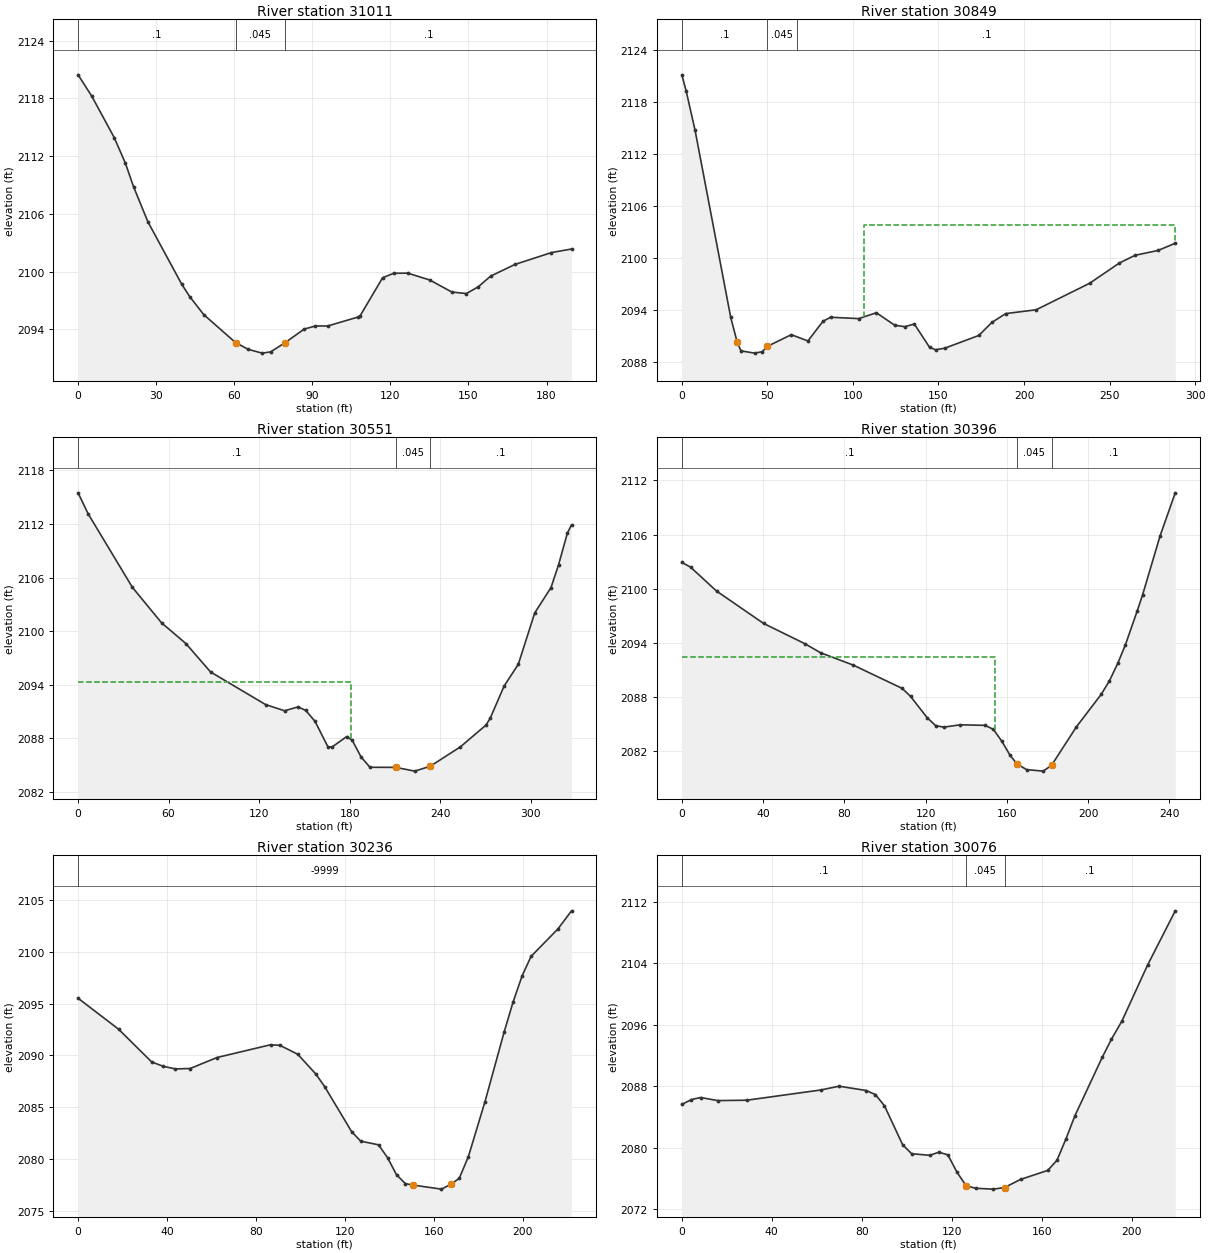
Type RM Length L Ch R = 1 ,31011   ,160.7,161.4,159.9
XS GIS Cut Line= 3
 2162311.2690389616347.9419950562162426.63856731616302.571955796
2162482.80844404 616268.54086268
#Sta/Elev= 30
       0 2120.44     5.3  2118.2    13.9 2113.91    18.2 2111.24    21.3 2108.82
    26.8 2105.18    39.8 2098.69    42.9 2097.39    48.3 2095.52    60.52092.615
    65.4 2091.91    70.7 2091.52      74 2091.65    79.52092.603    86.9 2094.02
    91.2 2094.34    95.9 2094.34   107.7 2095.28   108.4 2095.41     117 2099.35
   121.3 2099.82   126.7 2099.83   135.1 2099.12   143.6 2097.87   149.2 2097.71
   153.8 2098.42   158.5 2099.52   167.9 2100.74   181.9 2101.97   189.6 2102.34
#Mann= 3 ,-1,0
       0      .1       0    60.5    .045       0    79.5      .1       0
Bank Sta=60.5,79.5
XS Rating Curve= 0 ,0
Exp/Cntr(USF)=0,0
Exp/Cntr=0.3,0.1

Type RM Length L Ch R = 1 ,30849   ,300.3,298.4,295.7
XS GIS Cut Line= 2
2162353.96059593616493.212029246 2162613.2617895616366.912928458
#Sta/Elev= 30
       0 2121.12     2.5  2119.3     7.7 2114.77    28.6 2093.13    32.42090.262
    34.6 2089.28    42.5 2089.02      47 2089.18      502089.798      64 2091.15
    73.7 2090.42    82.5 2092.69      87 2093.16   103.4    2093   113.7 2093.68
   124.4 2092.24   130.3 2092.07   135.9 2092.38   144.8 2089.69   148.3 2089.41
   153.7 2089.59   173.6 2091.06   181.2 2092.56   189.3 2093.58   207.1 2094.02
   238.3 2097.07   255.8 2099.42     265 2100.31   278.3 2100.86   288.4 2101.69
#Mann= 3 ,-1,0
       0      .1       0      50    .045       0    67.6      .1       0
#XS Ineff= 2 , 0
                          106.37         2103.82
Permanent Ineff=
       F       F
Bank Sta=32.4,50
XS Rating Curve= 0 ,0
Exp/Cntr(USF)=0,0
Exp/Cntr=0.3,0.1

Type RM Length L Ch R = 1 ,30551   ,145.7,155.2,163.4
XS GIS Cut Line= 3
2162441.71802363616644.3780076252162581.71700192616619.878186424
2162718.21600575616495.045764115
#Sta/Elev= 30
       0 2115.47     6.6 2113.14      36  2104.9    55.3 2100.94    71.5 2098.61
    87.8 2095.44   124.3 2091.79   136.9  2091.1   145.8 2091.53   150.9 2091.14
   157.1 2089.91   165.6 2087.07   168.4 2087.05     178 2088.21   181.7 2087.81
   187.6 2085.93   193.5 2084.78   210.5 2084.77   223.2 2084.35   233.5  2084.9
   253.4 2087.06   270.4  2089.5   273.2 2090.27   282.4 2093.86   291.8 2096.29
   302.7 2102.04   313.5 2104.88   318.5 2107.42   324.3 2110.94   327.1  2111.9
#Mann= 3 ,-1,0
       0      .1       0   210.5    .045       0   233.5      .1       0
#XS Ineff= 2 , 0
          181.01 2094.37
Permanent Ineff=
       F       F
Bank Sta=210.5,233.5
XS Rating Curve= 0 ,0
Exp/Cntr(USF)=0,0
Exp/Cntr=0.3,0.1

Type RM Length L Ch R = 1 ,30396   ,159.1,159.9,160.9
XS GIS Cut Line= 3
 2162507.9122947616720.940019081 2162611.9353124616727.341435556
2162747.96541248 616700.13541554
#Sta/Elev= 30
       0 2102.93     4.3  2102.4    17.1 2099.75    40.3 2096.16    60.4 2093.94
    68.4 2092.91    84.4 2091.55   108.5 2088.97   112.6 2088.09   120.8 2085.72
   124.9 2084.86   128.9 2084.68   137.1 2084.94   149.3 2084.88   153.4 2084.43
   157.5 2083.13   161.6 2081.56   165.12080.587   169.7 2079.98   177.9 2079.81
     182 2080.45   194.2  2084.7   206.4  2088.3   210.5 2089.81   214.6 2091.74
   218.4 2093.82   224.1  2097.5   226.8 2099.31   235.4 2105.84   242.9 2110.63
#Mann= 3 ,-1,0
       0      .1       0   165.1    .045       0     182      .1       0
#XS Ineff= 2 , 0
          153.94 2092.44
Permanent Ineff=
       F       F
Bank Sta=165.1,182
XS Rating Curve= 0 ,0
Exp/Cntr(USF)=0,0
Exp/Cntr=0.3,0.1

Type RM Length L Ch R = 1 ,30236   ,159.3,159.9,159.7
XS GIS Cut Line= 2
2162542.17110296 616892.261163392162762.23766469616863.645697158
#Sta/Elev= 30
       0 2095.51    18.2 2092.53    33.1 2089.37    38.3 2088.95    43.8  2088.7
    50.4 2088.74    62.5  2089.8    86.6 2091.03    90.8 2090.97    98.8 2090.11
   106.9 2088.21   110.9 2086.99     123 2082.66   127.1 2081.74   135.1 2081.39
   139.2 2080.14   143.2  2078.5   147.2 2077.65   150.52077.516   163.4 2077.12
   167.62077.582   171.4 2078.16   175.5 2080.24     183 2085.56   191.6 2092.26
   195.6 2095.13   199.7 2097.68   203.7 2099.54   215.8 2102.19   221.9 2103.93
#Mann= 1 ,-1,0
       0   -9999       0
Bank Sta=150.5,167.6
XS Rating Curve= 0 ,0
Exp/Cntr(USF)=0,0
Exp/Cntr=0.3,0.1

Type RM Length L Ch R = 1 ,30076   ,168,177.5,165.8
XS GIS Cut Line= 3
 2162591.9949641617022.1529260022162657.19948824617037.272815657
2162808.39838479617017.427960485
#Sta/Elev= 30
       0 2085.64     4.3 2086.28     8.4 2086.54      16 2086.14    28.9 2086.19
    61.8 2087.52    69.9 2088.01      82 2087.45    86.1 2086.92    90.1 2085.47
    98.2  2080.4   102.2 2079.24   110.3 2079.03   114.3 2079.44   118.3 2079.09
   122.4 2076.82   126.4 2075.08   130.6 2074.75   138.5 2074.64   143.52074.845
   150.6  2075.9   162.7 2077.07   166.8 2078.38   170.8 2081.16   174.8 2084.18
   186.9 2091.74     191  2094.1   195.7 2096.48   207.1 2103.75   219.4 2110.79
#Mann= 3 ,-1,0
       0      .1       0   126.4    .045       0   143.5      .1       0
Bank Sta=126.4,143.5
XS Rating Curve= 0 ,0
Exp/Cntr(USF)=0,0
Exp/Cntr=0.3,0.1

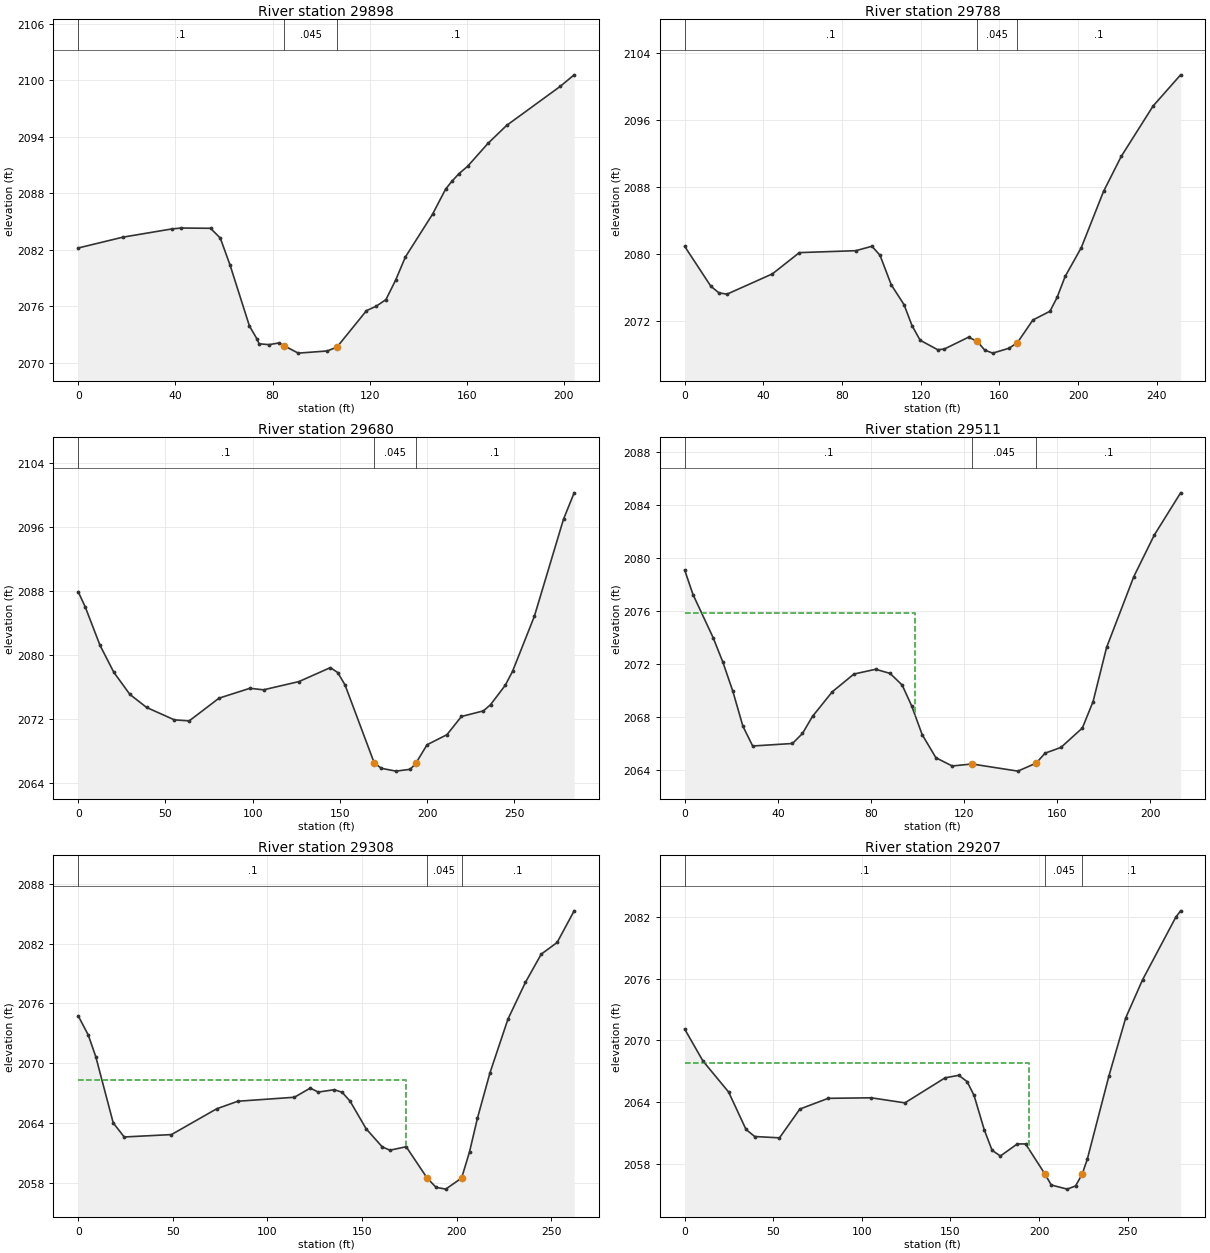
Type RM Length L Ch R = 1 ,29898   ,107.3,110.2,111.3
XS GIS Cut Line= 3
2162577.82006755617128.9371466932162723.34900548617139.332070831
2162775.32362617617165.791877727
#Sta/Elev= 30
       0 2082.19    18.4 2083.34    38.5 2084.21    42.5 2084.31    54.5 2084.28
    58.5 2083.24    62.5 2080.39    70.5 2073.91    73.5 2072.58    74.5 2072.02
    78.6 2071.93    82.6 2072.11    84.8 2071.81    90.6 2071.03   102.6 2071.26
   106.6 2071.69   118.7 2075.54   122.7 2076.01   126.7 2076.71   130.7 2078.78
   134.7 2081.23   145.9 2085.78   151.3 2088.45   153.8 2089.25   156.8 2090.09
   160.3 2090.85   168.7 2093.29   176.4  2095.2   198.5 2099.35   204.2 2100.57
#Mann= 3 ,-1,0
       0      .1       0    84.8    .045       0   106.6      .1       0
Bank Sta=84.8,106.6
XS Rating Curve= 0 ,0
Exp/Cntr(USF)=0,0
Exp/Cntr=0.3,0.1

Type RM Length L Ch R = 1 ,29788   ,105.5,107.9,107.8
XS GIS Cut Line= 3
2162507.19500353617209.1379580252162704.59356292617252.187643849
2162753.94320277617260.587582547
#Sta/Elev= 30
       0 2080.91    13.3 2076.14    17.4 2075.35    21.5 2075.19    44.6 2077.62
    58.3 2080.16      87 2080.39    95.2 2080.92    99.3 2079.84     105 2076.31
   111.5 2073.94   115.6 2071.41   119.7 2069.68   128.6 2068.55   131.9 2068.62
   144.3 2070.05   148.7 2069.55   152.5 2068.51   156.6 2068.14   164.8 2068.72
   169.1 2069.38     177  2072.1   185.7 2073.15   189.3  2074.8   193.4 2077.31
   201.6 2080.75   212.9 2087.47   221.9 2091.66   238.1 2097.69   252.1 2101.42
#Mann= 3 ,-1,0
       0      .1       0   148.7    .045       0   169.1      .1       0
Bank Sta=148.7,169.1
XS Rating Curve= 0 ,0
Exp/Cntr(USF)=0,0
Exp/Cntr=0.3,0.1

Type RM Length L Ch R = 1 ,29680   ,166.8,169.4,173.5
XS GIS Cut Line= 3
2162448.41666402617278.7156649512162583.23049496 617327.97456472
2162718.04432591617368.159456637
#Sta/Elev= 30
       0 2087.91       4 2086.03    12.5 2081.22    20.4 2077.86    29.6  2075.1
    39.2 2073.47    55.1 2071.92    63.6 2071.79    80.7 2074.63    98.4 2075.86
   106.2 2075.67   126.5  2076.7   144.5 2078.44   148.7 2077.83   152.9 2076.28
   169.6 2066.56   173.7 2065.87   182.1 2065.52   190.3 2065.75   193.5 2066.51
   199.9 2068.81   211.3 2070.07   219.6 2072.34   232.2 2073.04   236.3 2073.82
   244.7 2076.23   248.9 2077.98   261.4 2084.85   278.1 2096.97   284.2 2100.26
#Mann= 3 ,-1,0
       0      .1       0   169.6    .045       0   193.5      .1       0
Bank Sta=169.6,193.5
XS Rating Curve= 0 ,0
Exp/Cntr(USF)=0,0
Exp/Cntr=0.3,0.1

Type RM Length L Ch R = 1 ,29511   ,201.6,202.5,195.3
XS GIS Cut Line= 5
2162388.78746956617410.9369222252162461.37953238617438.158945782
2162514.88271923617458.9675864452162520.00825489617465.191451179
2162580.78246347617499.971871752
#Sta/Elev= 30
       0 2079.11     3.6 2077.25    12.2 2074.01    16.4 2072.15    20.7 2069.94
      25 2067.31    29.2 2065.81    46.3    2066    50.6 2066.76    54.9 2068.05
    63.4 2069.91    72.7 2071.25      82 2071.61    88.2  2071.3    93.4 2070.42
    97.5 2068.84     102 2066.67   107.9 2064.92   114.9  2064.3   123.4 2064.45
   143.1 2063.91     151 2064.52   154.8 2065.27   161.6  2065.7   170.8 2067.17
   175.4 2069.17   181.2 2073.26   192.9 2078.62   201.7 2081.76     213 2084.95
#Mann= 3 ,-1,0
       0      .1       0   123.4    .045       0     151      .1       0
#XS Ineff= 2 , 0
           99.01 2075.83
Permanent Ineff=
       F       F
Bank Sta=123.4,151
XS Rating Curve= 0 ,0
Exp/Cntr(USF)=0,0
Exp/Cntr=0.3,0.1

Type RM Length L Ch R = 1 ,29308   ,97,101.4,104.1
XS GIS Cut Line= 3
2162312.78731615617522.0125279762162403.10975698617590.137080804
2162544.71697353617636.829190046
#Sta/Elev= 30
       0 2074.76     5.3 2072.84     9.3 2070.65    18.5 2064.01    24.3 2062.59
    49.3 2062.83    73.2 2065.42    84.4 2066.18   114.3 2066.58   122.7  2067.5
   126.9  2067.1   135.4 2067.34   139.5 2067.08   143.7  2066.2   152.2 2063.42
   160.7  2061.6   164.8 2061.26   173.4 2061.61   184.52058.455   189.2 2057.53
   194.3 2057.35   202.7 2058.46   206.9 2061.11   211.1  2064.5   217.7 2069.04
   227.2 2074.43   236.4 2078.11   244.8 2080.96   253.2 2082.13   262.2 2085.31
#Mann= 3 ,-1,0
       0      .1       0   184.5    .045       0   202.7      .1       0
#XS Ineff= 2 , 0
          173.07 2068.28
Permanent Ineff=
       F       F
Bank Sta=184.5,202.7
XS Rating Curve= 0 ,0
Exp/Cntr(USF)=0,0
Exp/Cntr=0.3,0.1

Type RM Length L Ch R = 1 ,29207   ,142.3,170.4,179.9
XS GIS Cut Line= 3
2162259.67568082617587.2357499912162349.82802289617649.321796888
2162494.41196772617739.474138959
#Sta/Elev= 30
       0  2071.1    10.3 2068.01    24.8    2065    34.6 2061.38    39.5 2060.69
    53.5 2060.56      65 2063.35      81 2064.39   105.3 2064.44   124.3 2063.95
     147 2066.38   154.7 2066.62   159.4 2066.01   163.3 2064.68   169.1 2061.33
   173.5 2059.35   178.2  2058.8   187.7 2059.97   192.4 2059.97   203.3 2057.06
   206.9 2055.99   215.9 2055.59   220.6  2055.9   224.3 2057.03   227.2 2058.47
   239.5  2066.6   248.9 2072.18   258.4 2075.87   277.2 2081.95   279.9 2082.56
#Mann= 3 ,-1,0
       0      .1       0   203.3    .045       0   224.3      .1       0
#XS Ineff= 2 , 0
          194.54 2067.85
Permanent Ineff=
       F       F
Bank Sta=203.3,224.3
XS Rating Curve= 0 ,0
Exp/Cntr(USF)=0,0
Exp/Cntr=0.3,0.1

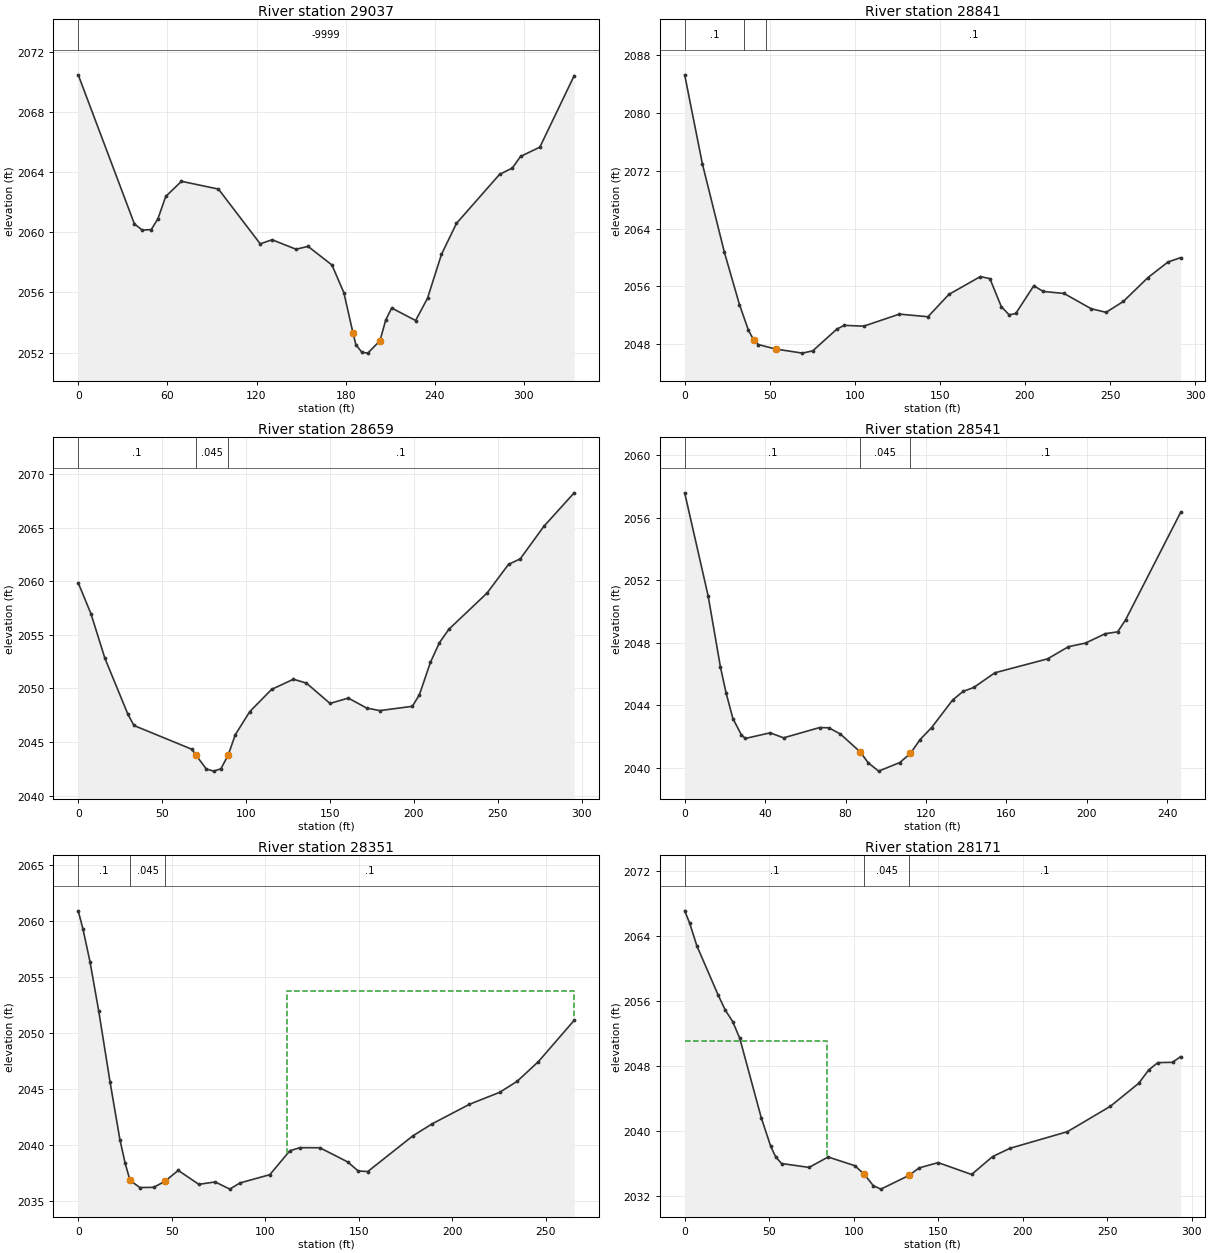
Type RM Length L Ch R = 1 ,29037   ,202.6,195.4,185.8
XS GIS Cut Line= 4
2162259.44058566617592.6049553522162315.24074482617640.433663197
2162297.45827652617810.9000834642162358.77713273617875.284882486
#Sta/Elev= 30
       0 2070.47    37.8 2060.56    43.1 2060.14    49.2 2060.18    53.7 2060.91
    58.9 2062.38    69.5 2063.39    94.4 2062.87   122.5 2059.23   130.5  2059.5
   146.6 2058.87   154.7 2059.06   170.8 2057.82   178.8 2055.98   184.92053.318
   186.9 2052.52   190.9 2052.02   194.9 2051.96   203.12052.789     207 2054.17
     211 2054.96   227.1 2054.13   235.1 2055.61   244.5 2058.53   254.6 2060.59
   283.6 2063.85   292.2 2064.27   297.7 2065.04   310.7 2065.66   333.8 2070.41
#Mann= 1 ,-1,0
       0   -9999       0
Bank Sta=184.9,203.1
XS Rating Curve= 0 ,0
Exp/Cntr(USF)=0,0
Exp/Cntr=0.3,0.1

Type RM Length L Ch R = 1 ,28841   ,186,182,178
XS GIS Cut Line= 2
2162095.23368397617681.2466792852162284.68297511617902.824482641
#Sta/Elev= 30
       0 2085.28    10.4 2072.96    23.3 2060.75    32.2 2053.47    37.5  2049.9
    40.52048.619    43.2 2047.94    53.42047.321    69.2 2046.75    75.3 2047.07
    89.4 2050.07    93.8  2050.6   105.2 2050.48   126.2 2052.15     143 2051.79
   155.3 2054.88   173.8 2057.35   179.4 2057.06   186.1 2053.19   190.7 2052.05
   194.6 2052.24   205.2 2056.08   210.7 2055.29     223 2055.01   238.9  2052.9
   247.7  2052.4   257.8  2053.9   272.3 2057.21   284.1 2059.37   291.5 2059.97
#Mann= 3 ,-1,0
       0      .1       0    35.1    .045       0    47.9      .1       0
Bank Sta=40.5,53.4
XS Rating Curve= 0 ,0
Exp/Cntr(USF)=0,0
Exp/Cntr=0.3,0.1

Type RM Length L Ch R = 1 ,28659   ,110.7,117.9,125.8
XS GIS Cut Line= 3
2162021.42136427617850.0572338462162139.84756904617898.067857402
2162263.07483617618011.692999819
#Sta/Elev= 30
       0 2059.86     7.6 2056.97    15.9 2052.81    29.6 2047.59    33.2 2046.54
    67.7 2044.32    70.32043.741    76.3 2042.48    80.7 2042.28      85  2042.5
    89.3 2043.77    93.6 2045.69   102.2 2047.84   115.2 2049.91   128.2 2050.86
   135.9  2050.5     150  2048.6   160.9  2049.1   171.8 2048.17   179.6 2047.93
     199 2048.33   203.2  2049.4   209.8 2052.44   215.1 2054.26   220.8 2055.53
   243.5  2058.9   256.3 2061.58   263.3  2062.1   277.4 2065.14   295.4 2068.26
#Mann= 3 ,-1,0
       0      .1       0    70.3    .045       0    89.3      .1       0
Bank Sta=70.3,89.3
XS Rating Curve= 0 ,0
Exp/Cntr(USF)=0,0
Exp/Cntr=0.3,0.1

Type RM Length L Ch R = 1 ,28541   ,189.3,190.6,192.3
XS GIS Cut Line= 2
2161968.60967836617899.668211521 2162128.4167997618087.550249141
#Sta/Elev= 30
       0 2057.59    11.7 2050.98    17.8 2046.44    20.6 2044.79      24 2043.15
    28.2 2042.11    30.2 2041.88    42.5 2042.24    49.2 2041.92    67.2 2042.58
    71.7 2042.56    77.4 2042.17    87.4 2041.01    91.3 2040.32    96.5 2039.79
     107 2040.34   112.3 2040.92   117.1 2041.81   122.8 2042.57   133.3 2044.34
   138.5 2044.89   143.8 2045.14   154.3 2046.08   180.5 2046.97   190.9 2047.75
   199.4 2047.98   209.2 2048.58   215.4  2048.7   219.3 2049.46   246.7 2056.34
#Mann= 3 ,-1,0
       0      .1       0    87.4    .045       0   112.3      .1       0
Bank Sta=87.4,112.3
XS Rating Curve= 0 ,0
Exp/Cntr(USF)=0,0
Exp/Cntr=0.3,0.1

Type RM Length L Ch R = 1 ,28351   ,177,179.6,175.3
XS GIS Cut Line= 2
2161821.37709945617968.4834386182161997.41605249618166.927349318
#Sta/Elev= 30
       0 2060.91     2.5 2059.32     6.3 2056.37      11 2051.95      17 2045.67
    22.3  2040.5    25.1  2038.4    27.7 2036.86      33 2036.22    40.4 2036.24
    46.4 2036.78    53.5 2037.75    64.5 2036.51    73.3 2036.72    81.1 2036.08
    86.5 2036.63   102.5 2037.37   113.2  2039.5   118.6 2039.78   129.3 2039.77
   144.1 2038.51   149.8  2037.7   154.9 2037.65     179 2040.83   189.5 2041.92
   209.3 2043.65   225.5 2044.72   234.8  2045.7   246.2 2047.46   265.3 2051.14
#Mann= 3 ,-1,0
       0      .1       0    27.7    .045       0    46.4      .1       0
#XS Ineff= 2 , 0
                          111.72         2053.77
Permanent Ineff=
       F       F
Bank Sta=27.7,46.4
XS Rating Curve= 0 ,0
Exp/Cntr(USF)=0,0
Exp/Cntr=0.3,0.1

Type RM Length L Ch R = 1 ,28171   ,301.9,302.5,305.1
XS GIS Cut Line= 3
2161692.87970764618018.3554869742161706.41880729618057.582158775
2161876.95503093618243.053847131
#Sta/Elev= 30
       0 2067.07       3 2065.53     7.2 2062.77    19.9 2056.68    24.1 2054.84
    28.4 2053.46    32.6  2051.4    45.3 2041.65    50.9 2038.13    53.8 2036.85
    57.3 2036.01    73.6 2035.53    84.9 2036.81   100.7 2035.74   106.42034.663
   111.6 2033.29   116.1 2032.86   132.7 2034.54   138.8 2035.47     150 2036.12
   169.8 2034.66   182.2 2036.86   192.5 2037.88   226.5 2039.92   251.9 2043.04
   268.7 2045.87   274.6 2047.51     280 2048.41   288.7 2048.45   293.5 2049.15
#Mann= 3 ,-1,0
       0      .1       0   106.4    .045       0   132.7      .1       0
#XS Ineff= 2 , 0
           84.17 2051.01
Permanent Ineff=
       F       F
Bank Sta=106.4,132.7
XS Rating Curve= 0 ,0
Exp/Cntr(USF)=0,0
Exp/Cntr=0.3,0.1

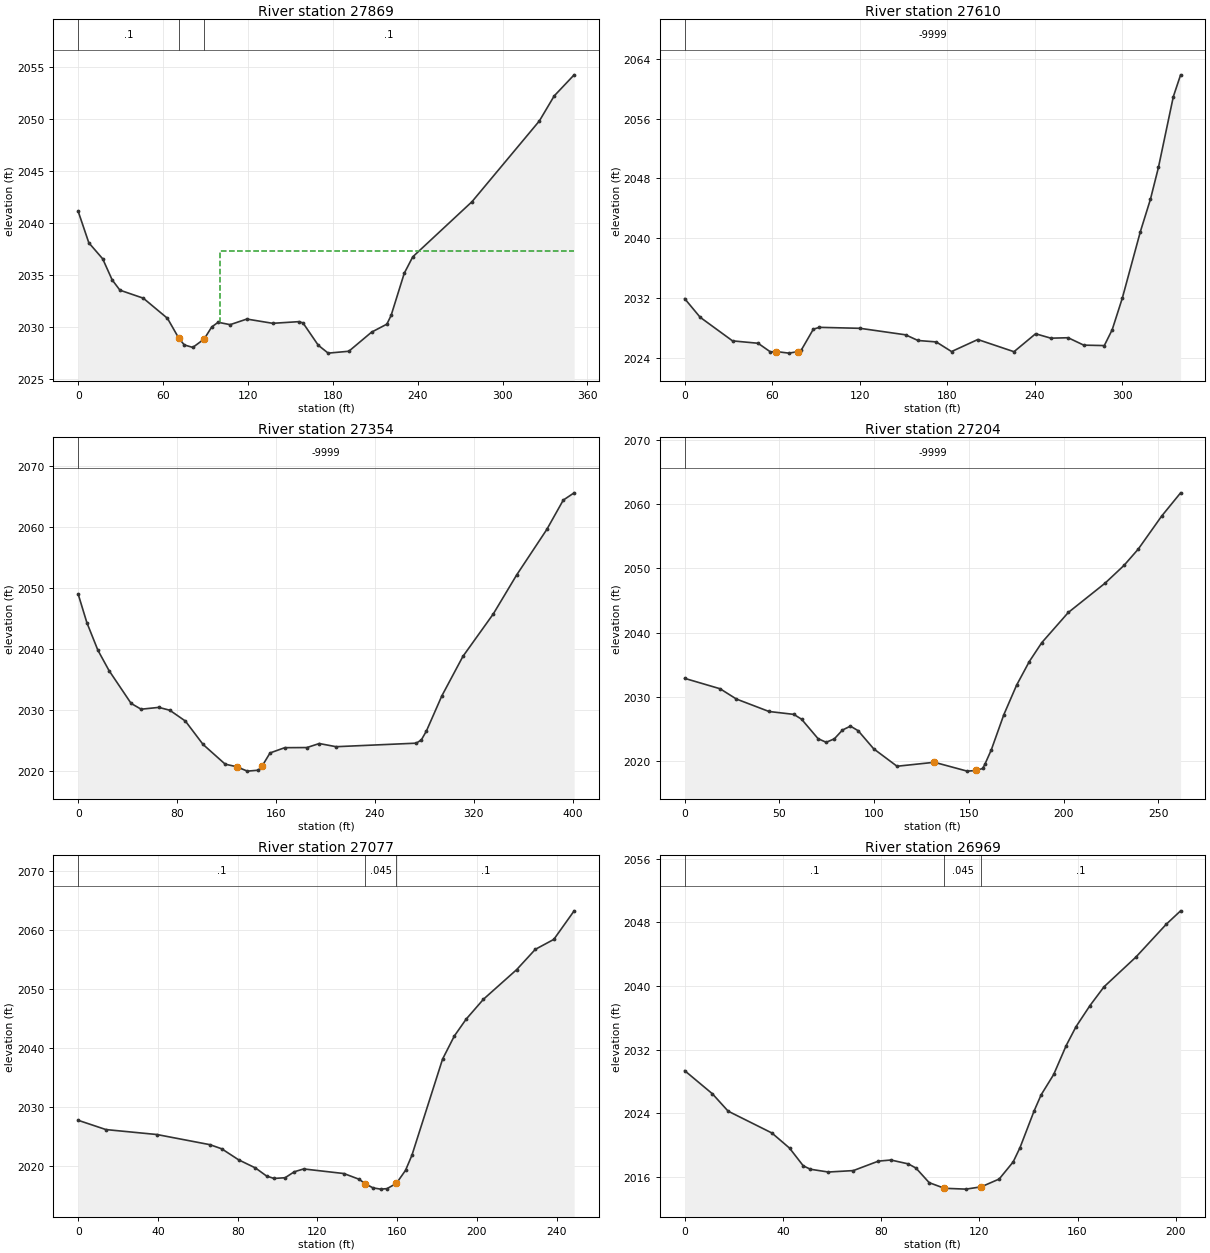
Type RM Length L Ch R = 1 ,27869   ,242.7,258.6,256.3
XS GIS Cut Line= 3
2161437.18324038618175.7493383172161467.45855018618207.740391357
2161672.48652314618435.622441769
#Sta/Elev= 30
       0 2041.14     7.5 2038.12    17.3 2036.58      24 2034.55    29.5 2033.56
      46 2032.79    63.1 2030.85    71.1 2028.94      75 2028.29      81 2028.05
      89 2028.85    94.4 2030.02    98.9 2030.47   107.4 2030.24   119.2 2030.78
   137.5 2030.37     156 2030.53   158.9 2030.41   169.7 2028.26   176.7  2027.5
   191.3 2027.68   207.4 2029.52   218.2 2030.29   221.2 2031.13   230.5 2035.19
   236.5 2036.77   278.4 2042.08     326 2049.85   336.5 2052.26   350.6 2054.29
#Mann= 3 ,-1,0
       0      .1       0    71.1    .045       0      89      .1       0
#XS Ineff= 2 , 0
                          100.06         2037.32
Permanent Ineff=
       F       F
Bank Sta=71.1,89
XS Rating Curve= 0 ,0
Exp/Cntr(USF)=0,0
Exp/Cntr=0.3,0.1

Type RM Length L Ch R = 1 ,27610   ,264.1,255.6,244.8
XS GIS Cut Line= 3
2161366.63751781618285.3338433572161400.36288873618388.349521792
2161549.98089788 618564.94782768
#Sta/Elev= 30
       0  2031.9    10.6 2029.41    32.8 2026.25    50.3 2025.93    58.8 2024.77
    62.52024.823    71.4 2024.61      78 2024.82    79.8 2024.98    88.2 2027.82
    92.4 2028.06   120.2 2027.93   151.4 2027.06   159.9  2026.3   172.4 2026.11
   182.9 2024.82   200.9 2026.43   225.7  2024.8   240.5  2027.2     251 2026.61
   262.8 2026.67   273.5 2025.68   287.6 2025.62     293 2027.74   299.9 2031.94
   312.3 2040.86   319.2 2045.19   324.7 2049.46   334.9 2058.93   339.9 2061.85
#Mann= 1 ,-1,0
       0   -9999       0
Bank Sta=62.5,78
XS Rating Curve= 0 ,0
Exp/Cntr(USF)=0,0
Exp/Cntr=0.3,0.1

Type RM Length L Ch R = 1 ,27354   ,156.5,150.7,146.4
XS GIS Cut Line= 4
2161137.94089483618491.0926719772161320.38341763618582.692444836
2161399.87082383618565.2809177632161489.19952794618638.712140633
#Sta/Elev= 30
       0    2049       7 2044.35    15.9 2039.84    24.9 2036.51    42.8 2031.12
    50.9 2030.17    65.2 2030.47    74.1    2030    86.7 2028.23     101  2024.4
   118.9 2021.17   128.12020.755   136.8 2020.03   145.7 2020.18   148.92020.904
   155.2 2023.01   167.1 2023.87     185 2023.89     195 2024.55   208.6 2024.03
   273.5 2024.61   277.6 2025.15   281.7 2026.61   294.2 2032.37   311.2 2038.82
   335.8 2045.78   354.6 2052.13   379.1 2059.62   392.4 2064.42   401.2 2065.61
#Mann= 1 ,-1,0
       0   -9999       0
Bank Sta=128.1,148.9
XS Rating Curve= 0 ,0
Exp/Cntr(USF)=0,0
Exp/Cntr=0.3,0.1

Type RM Length L Ch R = 1 ,27204   ,122.7,126.4,130.7
XS GIS Cut Line= 3
2161138.77925659618647.8311100812161218.79484524618679.569136868
2161390.00138411618719.353423966
#Sta/Elev= 30
       0 2032.88    18.7 2031.26    27.3 2029.66    44.5 2027.72    57.6 2027.27
    61.7 2026.52    70.4 2023.49    74.7 2022.92      79 2023.46    83.3 2024.83
    87.5 2025.44    91.6 2024.72    99.8  2021.9   112.1 2019.19   131.82019.809
   149.1 2018.43     1542018.528   157.3 2018.85   158.5 2019.51   161.9 2021.78
   168.5 2027.24   175.2 2031.81   181.9 2035.49   188.5 2038.44   202.5 2043.14
   221.9  2047.7   231.9 2050.47   239.4    2053   251.8 2058.16   261.8 2061.78
#Mann= 1 ,-1,0
       0   -9999       0
Bank Sta=131.8,154
XS Rating Curve= 0 ,0
Exp/Cntr(USF)=0,0
Exp/Cntr=0.3,0.1

Type RM Length L Ch R = 1 ,27077   ,106.6,108.3,110.1
XS GIS Cut Line= 3
2161118.44615457 618711.776873052161150.13316611618762.188027784
2161312.88917997618858.689381133
#Sta/Elev= 30
       0 2027.79    13.9 2026.22    39.5 2025.38    66.1 2023.66      72 2022.96
    80.5 2021.09    88.9 2019.72    94.5 2018.35    98.2 2017.94   103.8 2018.06
   108.4 2019.07   113.1 2019.55   133.3 2018.77     141 2017.79   143.8 2017.08
   147.9 2016.34   151.7 2016.13   154.9 2016.21   159.6 2017.09   159.6  2017.1
   164.2 2019.31   167.4 2021.86   182.8 2038.17   188.7 2042.08   194.6 2044.92
   203.3  2048.3     220 2053.33   229.3 2056.75   238.6 2058.44   248.8 2063.28
#Mann= 3 ,-1,0
       0      .1       0   143.8    .045       0   159.6      .1       0
Bank Sta=143.8,159.6
XS Rating Curve= 0 ,0
Exp/Cntr(USF)=0,0
Exp/Cntr=0.3,0.1

Type RM Length L Ch R = 1 ,26969   ,113.1,110.5,108.3
XS GIS Cut Line= 2
2161062.27372501618811.1588638122161220.70878274618936.466591294
#Sta/Elev= 30
       0 2029.34    11.3 2026.43    17.7 2024.25    35.5 2021.51    42.7 2019.61
    48.3 2017.38    51.2 2016.95    58.5  2016.6    68.7 2016.78    78.9 2017.97
      84 2018.11    91.1 2017.62    94.2  2017.1    99.6 2015.26   105.82014.556
   114.6 2014.45   120.82014.741   128.1 2015.72   133.8 2017.87   136.6 2019.68
   142.3 2024.26   145.2 2026.31   150.3 2028.86   155.4  2032.5   159.4 2034.87
   165.1 2037.53   170.8 2039.88   183.8 2043.62   196.2 2047.76     202 2049.43
#Mann= 3 ,-1,0
       0      .1       0   105.8    .045       0   120.8      .1       0
Bank Sta=105.8,120.8
XS Rating Curve= 0 ,0
Exp/Cntr(USF)=0,0
Exp/Cntr=0.3,0.1

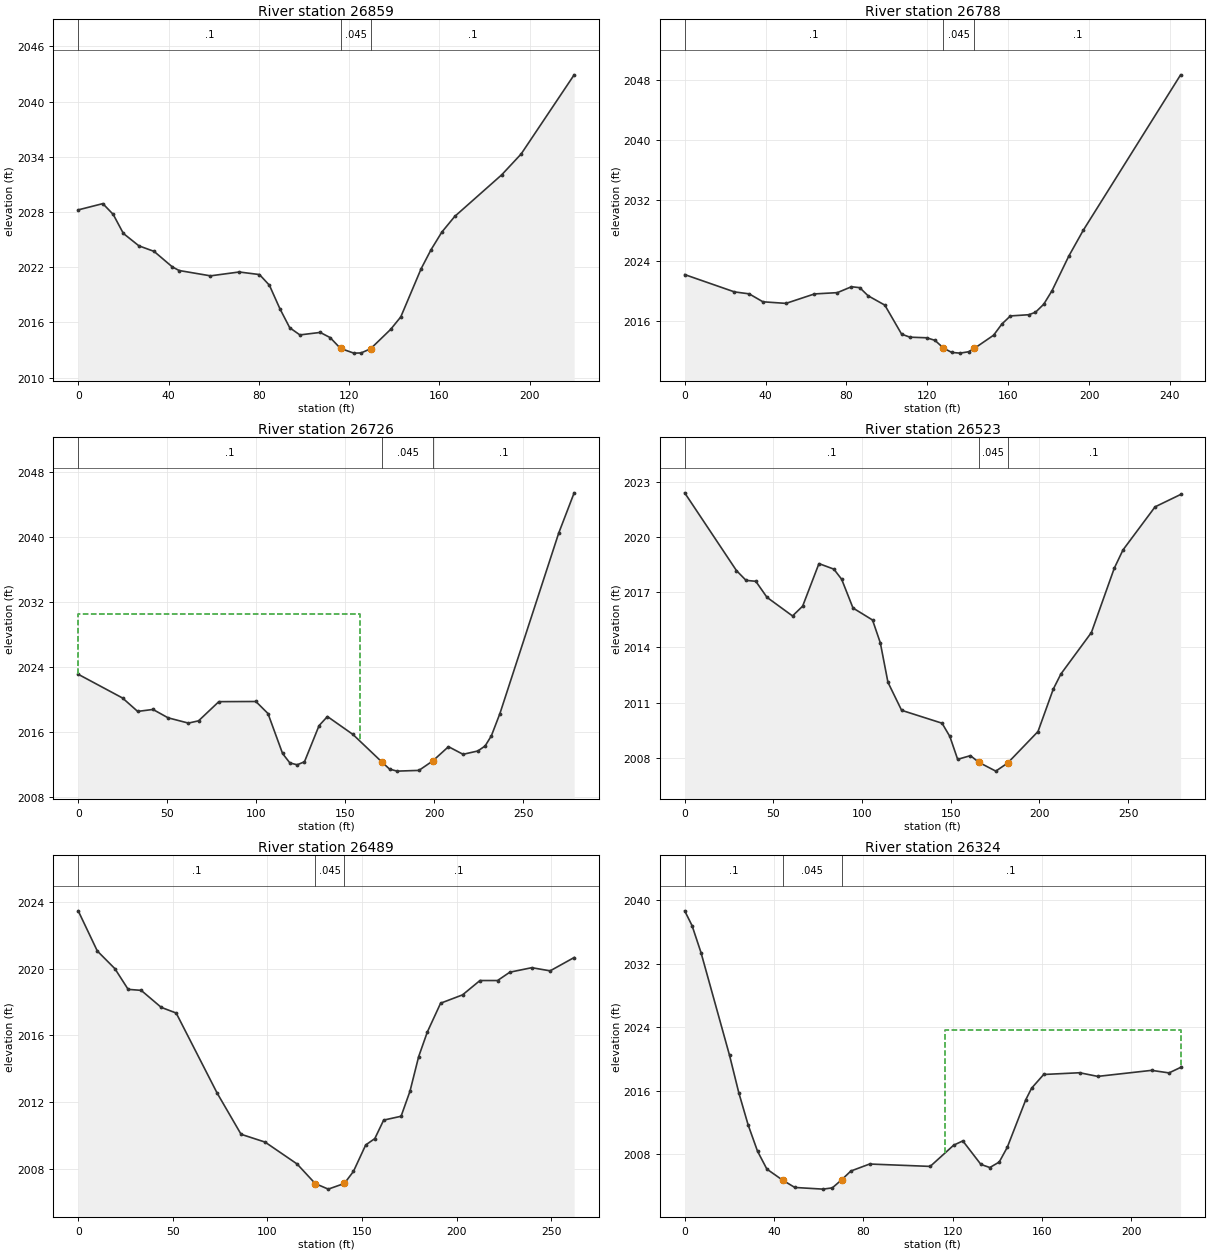
Type RM Length L Ch R = 1 ,26859   ,72.7,70,67.7
XS GIS Cut Line= 3
2160997.45938321618887.4957552672161024.82543863618939.347228708
 2161168.8573093619011.363164042
#Sta/Elev= 30
       0 2028.22    10.9  2028.9    15.5 2027.73      20 2025.66    26.9 2024.31
    33.6 2023.71    41.7 2022.02    44.7 2021.63    58.6 2021.05    71.3 2021.47
    80.3 2021.19    84.7 2020.03    89.3  2017.5    93.7 2015.41    98.2 2014.63
   107.2  2014.9   111.6 2014.34   116.2 2013.16   122.1 2012.65   125.3 2012.67
   129.5 2013.12   138.4 2015.23   142.9 2016.59   151.9 2021.82   156.3 2023.89
   161.1 2025.81   166.8 2027.51   187.6 2032.03   196.2 2034.29   219.7  2042.9
#Mann= 3 ,-1,0
       0      .1       0   116.2    .045       0   129.5      .1       0
Bank Sta=116.2,129.5
XS Rating Curve= 0 ,0
Exp/Cntr(USF)=0,0
Exp/Cntr=0.3,0.1

Type RM Length L Ch R = 1 ,26788   ,62.3,62.3,63.5
XS GIS Cut Line= 3
2160945.60790976618960.9520093082161003.22065803619018.564757576
2161161.65571577 619060.33400007
#Sta/Elev= 30
       0  2022.2    24.6 2019.91    31.9 2019.65    38.7  2018.6    50.1 2018.39
    64.2 2019.64    75.5 2019.81    82.5 2020.59    86.6 2020.47    90.7  2019.4
      99 2018.16   107.3 2014.32   111.4 2013.92   119.7 2013.84   123.8  2013.5
     128 2012.48   132.1  2011.9   136.2 2011.81   140.4 2011.99   143.3 2012.44
   152.8 2014.18   156.9 2015.66   161.1 2016.73   170.2 2016.89   173.5 2017.21
   177.6 2018.28   181.7 2020.07     190 2024.65   197.1 2028.04   245.3 2048.62
#Mann= 3 ,-1,0
       0      .1       0     128    .045       0   143.3      .1       0
Bank Sta=128,143.3
XS Rating Curve= 0 ,0
Exp/Cntr(USF)=0,0
Exp/Cntr=0.3,0.1

Type RM Length L Ch R = 1 ,26726   ,170.3,203.4,233.4
XS GIS Cut Line= 4
2160935.87864735618962.6074267492160993.71222528619037.450880543
 2161003.9181508619083.3775453722161136.59518253619117.397297096
#Sta/Elev= 30
       0 2023.06    24.9 2020.14    33.4 2018.49      42 2018.73    50.5  2017.7
    61.9 2017.05    67.6 2017.33      79 2019.69    99.8 2019.71   106.6 2018.23
   114.8 2013.31   118.9 2012.15     123 2011.92   127.1 2012.29   135.3 2016.74
     140 2017.86   154.3 2015.66   170.8 2012.22   174.9 2011.39   179.1 2011.14
   191.4 2011.23   199.2  2012.4     208 2014.15   216.2 2013.21   224.5 2013.62
   228.6 2014.24   232.1 2015.49   236.9 2018.23   269.9 2040.42   278.6 2045.39
#Mann= 3 ,-1,0
       0      .1       0   170.8    .045       0   199.2      .1       0
#XS Ineff= 2 , 0
          158.37  2030.5
Permanent Ineff=
       F       F
Bank Sta=170.8,199.2
XS Rating Curve= 0 ,0
Exp/Cntr(USF)=0,0
Exp/Cntr=0.3,0.1

Type RM Length L Ch R = 1 ,26523   ,31.2,33.6,35.7
XS GIS Cut Line= 5
2160931.95781685618976.5871669552160979.46638005619042.662295094
2160947.79400458619115.8364039412160934.68819404619136.587270629
2160900.28544138619223.959340894
#Sta/Elev= 30
       0 2022.39    29.2 2018.17    34.6 2017.64    40.1 2017.59    46.4 2016.72
    60.8 2015.71    66.5 2016.24    75.7 2018.55    84.1 2018.25    88.5  2017.7
    94.9 2016.14   105.9 2015.49   110.3 2014.25   114.6 2012.11   122.3 2010.59
   145.1 2009.89   149.5 2009.17   153.9 2007.93   161.1 2008.13   165.92007.765
   175.4 2007.29   182.1 2007.73   199.2 2009.44   207.8 2011.74   212.1 2012.56
   229.3 2014.81   242.2  2018.3   247.1 2019.29   265.2 2021.63   279.6  2022.3
#Mann= 3 ,-1,0
       0      .1       0   165.9    .045       0   182.1      .1       0
Bank Sta=165.9,182.1
XS Rating Curve= 0 ,0
Exp/Cntr(USF)=0,0
Exp/Cntr=0.3,0.1

Type RM Length L Ch R = 1 ,26489   ,176.7,164.9,142.9
XS GIS Cut Line= 5
2160912.84517648618992.4233546912160941.78717475619042.116219654
 2160921.5823835619101.0923670832160901.37759225 619122.93538465
2160844.58574658 619220.13681282
#Sta/Elev= 30
       0 2023.47    10.1 2021.06    19.4    2020    26.4 2018.76    33.3  2018.7
    43.9 2017.68    51.8 2017.34    73.4 2012.55    86.1 2010.07    98.8  2009.6
   115.7 2008.29   125.32007.114   132.2 2006.78   140.7 2007.12   145.5 2007.84
     152 2009.43   156.8 2009.81   161.5 2010.92   170.7 2011.15   175.4 2012.65
     180 2014.73   184.6 2016.21   191.6 2017.93   203.2 2018.43   212.4 2019.29
   221.7 2019.29   228.2 2019.79   239.8 2020.06   249.5 2019.87   262.2 2020.67
#Mann= 3 ,-1,0
       0      .1       0   125.3    .045       0   140.7      .1       0
Bank Sta=125.3,140.7
XS Rating Curve= 0 ,0
Exp/Cntr(USF)=0,0
Exp/Cntr=0.3,0.1

Type RM Length L Ch R = 1 ,26324   ,112.5,110.3,97.2
XS GIS Cut Line= 3
2160774.28482666619005.9826101982160810.00556597619123.350753648
2160821.06198528619222.008033649
#Sta/Elev= 30
       0 2038.63     3.3 2036.77     7.3 2033.38    20.1 2020.42    24.2 2015.76
    28.4 2011.69    32.6 2008.38    36.8 2006.12    43.82004.739    49.3 2003.81
    61.9  2003.6    66.1 2003.76    70.2 2004.76    74.4 2005.88    82.8 2006.76
   109.9 2006.46   120.4 2009.13   124.5 2009.67   132.6 2006.71   136.6 2006.32
   140.8 2007.01   144.4 2008.86   152.7 2014.86   155.3 2016.31   160.7 2018.03
   176.8 2018.25   184.9 2017.79     209 2018.55   216.8 2018.23     222 2018.92
#Mann= 3 ,-1,0
       0      .1       0    43.8    .045       0    70.2      .1       0
#XS Ineff= 2 , 0
                          116.62         2023.67
Permanent Ineff=
       F       F
Bank Sta=43.8,70.2
XS Rating Curve= 0 ,0
Exp/Cntr(USF)=0,0
Exp/Cntr=0.3,0.1

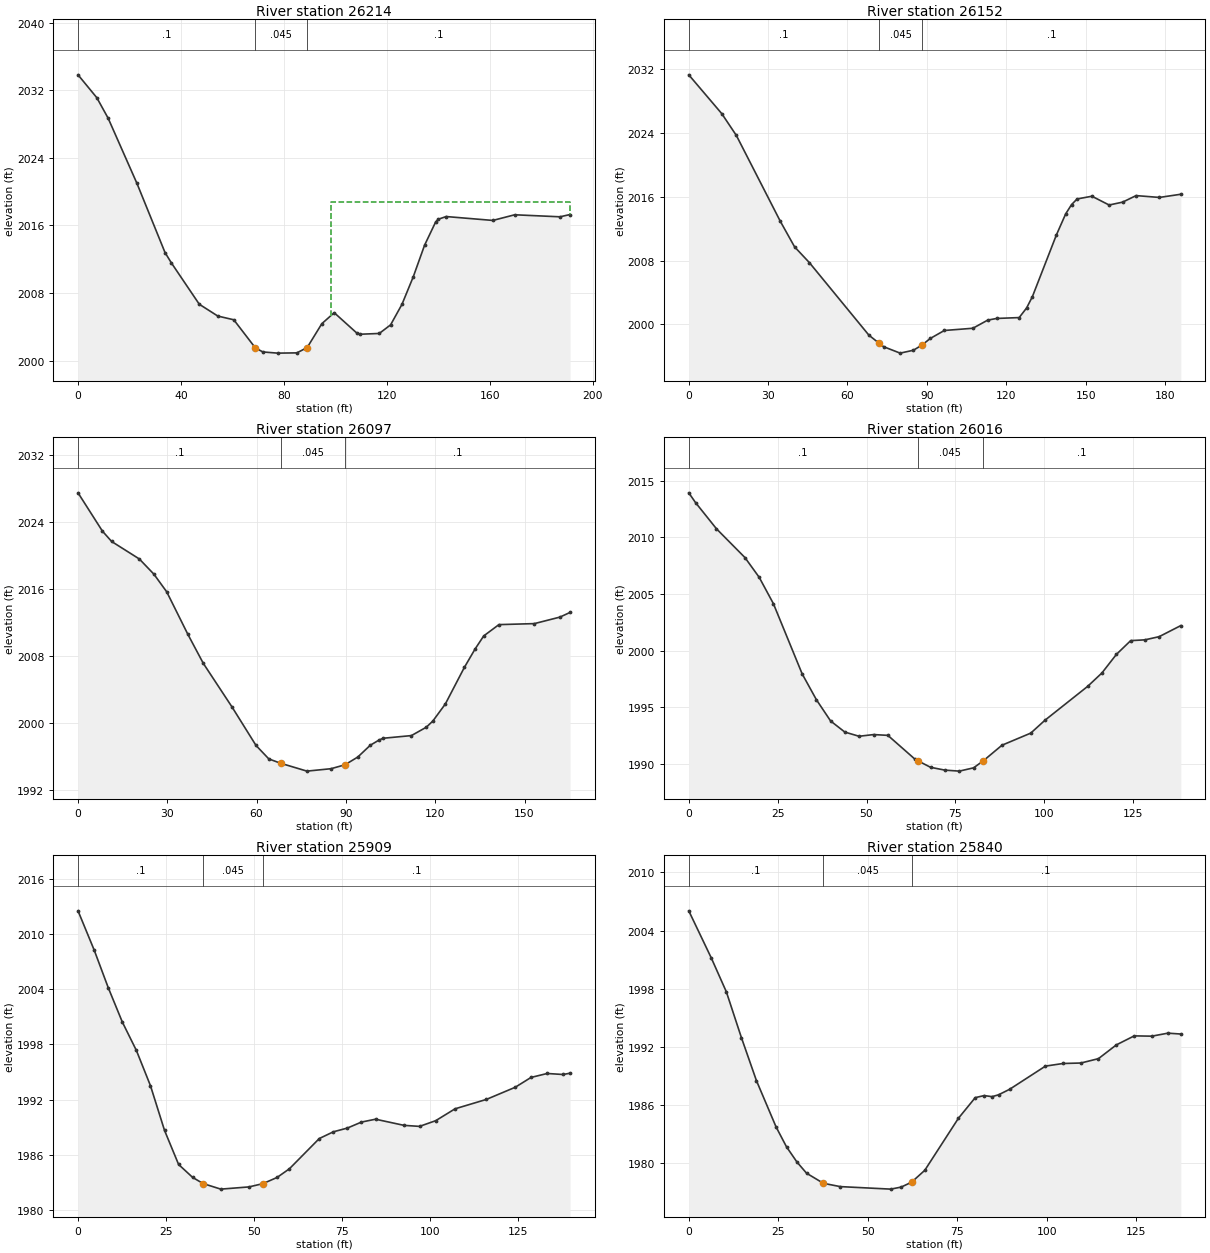
Type RM Length L Ch R = 1 ,26214   ,63.4,61.5,58.7
XS GIS Cut Line= 4
2160694.33841011619070.620138475 2160719.8532239619124.201247441
2160741.96606252619155.6695177862160780.23828321619240.718897098
#Sta/Elev= 30
       0 2033.85     7.3 2031.14    11.7 2028.71    22.9 2020.98    33.8 2012.79
    36.3 2011.55    47.1 2006.67    54.3 2005.27    60.5 2004.83    68.9 2001.49
    71.8 2001.02    77.5 2000.88      85 2000.91      89 2001.54    94.7 2004.37
    99.5 2005.67   108.2 2003.28   109.7 2003.12     117 2003.21   121.4 2004.23
   125.8 2006.65   130.2 2009.92   134.6 2013.67   138.9 2016.42   139.9 2016.74
     143 2017.06   161.1  2016.6   169.6 2017.27   187.2 2017.03   191.1  2017.3
#Mann= 3 ,-1,0
       0      .1       0    68.9    .045       0      89      .1       0
#XS Ineff= 2 , 0
                           98.25         2018.73
Permanent Ineff=
       F       F
Bank Sta=68.9,89
XS Rating Curve= 0 ,0
Exp/Cntr(USF)=0,0
Exp/Cntr=0.3,0.1

Type RM Length L Ch R = 1 ,26152   ,49.2,55.2,63.1
XS GIS Cut Line= 4
2160627.14940045619121.6497660622160666.27211494619159.071492959
2160736.01260597619227.961490201 2160757.2749508619254.326797788
#Sta/Elev= 30
       0  2031.3    12.5 2026.42      18 2023.69    34.6 2012.93      40 2009.72
    45.6 2007.74    68.1 1998.64      721997.618    73.7 1997.19    79.9 1996.39
    84.9 1996.75    88.1 1997.39    91.3 1998.23    96.6 1999.23   107.4 1999.51
     113 2000.53   116.4 2000.74   124.9 2000.85   127.7 2002.05   129.9 2003.48
     139 2011.24   142.5 2013.87   144.7 2015.02   146.8 2015.73   152.4 2016.07
   158.9 2014.97     164 2015.33   169.1 2016.15   177.9 2015.92     186 2016.32
#Mann= 3 ,-1,0
       0      .1       0      72    .045       0    88.1      .1       0
Bank Sta=72,88.1
XS Rating Curve= 0 ,0
Exp/Cntr(USF)=0,0
Exp/Cntr=0.3,0.1

Type RM Length L Ch R = 1 ,26097   ,75.7,81.4,82.2
XS GIS Cut Line= 4
 2160621.1959439619145.4635922692160639.05631356619190.539763304
2160661.16915218619250.0743288222160702.84334804619283.243586754
#Sta/Elev= 30
       0 2027.49     8.2 2022.91    11.3 2021.67    20.6 2019.58    25.5 2017.76
    29.8 2015.65    36.9 2010.57    42.1 2007.09    51.7  2001.9    59.8 1997.28
    64.1 1995.67    68.11995.148    76.9 1994.21      85  1994.5    89.7 1994.97
      94  1995.9    98.2 1997.31   101.2 1997.94   102.5 1998.14     112 1998.46
     117 1999.46   119.2  2000.2   123.4 2002.24   129.8 2006.62   133.4 2008.82
   136.3 2010.38   141.4 2011.73   153.3 2011.85   161.9 2012.63   165.3 2013.19
#Mann= 3 ,-1,0
       0      .1       0    68.1    .045       0    89.7      .1       0
Bank Sta=68.1,89.7
XS Rating Curve= 0 ,0
Exp/Cntr(USF)=0,0
Exp/Cntr=0.3,0.1

Type RM Length L Ch R = 1 ,26016   ,102.9,106.5,105
XS GIS Cut Line= 2
2160577.82076045619185.4368005452160590.57816735 619323.21679503
#Sta/Elev= 30
       0 2013.94     1.9 2013.08     7.8 2010.76    15.8 2008.22    19.8 2006.48
    23.8 2004.15    31.9 1997.94    35.9 1995.66    39.9 1993.78    43.9  1992.8
    47.9 1992.43      52 1992.58      56 1992.51    63.5 1990.44    64.4 1990.27
      68 1989.69      72 1989.44    76.1 1989.35    80.1 1989.64    82.8 1990.25
    88.1 1991.64    96.2 1992.71   100.2 1993.85   112.2 1996.84   116.2 1998.02
   120.3 1999.67   124.3 2000.88   128.3 2000.95   132.3 2001.23   138.4 2002.21
#Mann= 3 ,-1,0
       0      .1       0    64.4    .045       0    82.8      .1       0
Bank Sta=64.4,82.8
XS Rating Curve= 0 ,0
Exp/Cntr(USF)=0,0
Exp/Cntr=0.3,0.1

Type RM Length L Ch R = 1 ,25909   ,75,69.5,60.3
XS GIS Cut Line= 3
 2160485.9674308619184.5863067522160488.51891217619277.290130202
 2160510.6317508619318.964326065
#Sta/Elev= 30
       0 2012.52     4.6 2008.25     8.6 2004.16    12.6 2000.43    16.6 1997.34
    20.6 1993.51    24.6 1988.65    28.6 1984.95    32.6 1983.54    35.6 1982.87
    40.6 1982.27    48.6 1982.51    52.6 1982.87    56.6 1983.54    60.1 1984.48
    68.6 1987.77    72.6  1988.5    76.6 1988.91    80.6 1989.56    84.6 1989.87
    92.7  1989.2    97.1 1989.09   101.7 1989.71   107.2    1991   116.1 1992.02
   124.3 1993.34   128.8 1994.41   133.4 1994.84   137.9 1994.73   139.9 1994.87
#Mann= 3 ,-1,0
       0      .1       0    35.6    .045       0    52.6      .1       0
Bank Sta=35.6,52.6
XS Rating Curve= 0 ,0
Exp/Cntr(USF)=0,0
Exp/Cntr=0.3,0.1

Type RM Length L Ch R = 1 ,25840   ,113.6,107.7,103.1
XS GIS Cut Line= 4
2160406.90097945619215.183453317  2160412.854436619233.894316766
2160447.72468151619290.0269071122160478.34245807619331.701102974
#Sta/Elev= 30
       0 2006.04     6.3 2001.17    10.5 1997.68    14.7 1992.96    18.9 1988.52
    24.4 1983.73    27.3 1981.69    30.2 1980.13    32.9 1978.97    37.6 1977.93
    42.3 1977.59    56.4 1977.33    59.3 1977.54    62.2 1978.04    65.9 1979.27
    75.3 1984.64      80 1986.77    82.5 1986.98    84.7 1986.87    86.5 1987.06
    89.6 1987.63    99.6 1990.02   104.5 1990.29   109.5 1990.34   114.4 1990.79
   119.4 1992.21   124.4 1993.14   129.3 1993.11   133.8 1993.42   137.4 1993.33
#Mann= 3 ,-1,0
       0      .1       0    37.6    .045       0    62.2      .1       0
Bank Sta=37.6,62.2
XS Rating Curve= 0 ,0
Exp/Cntr(USF)=0,0
Exp/Cntr=0.3,0.1