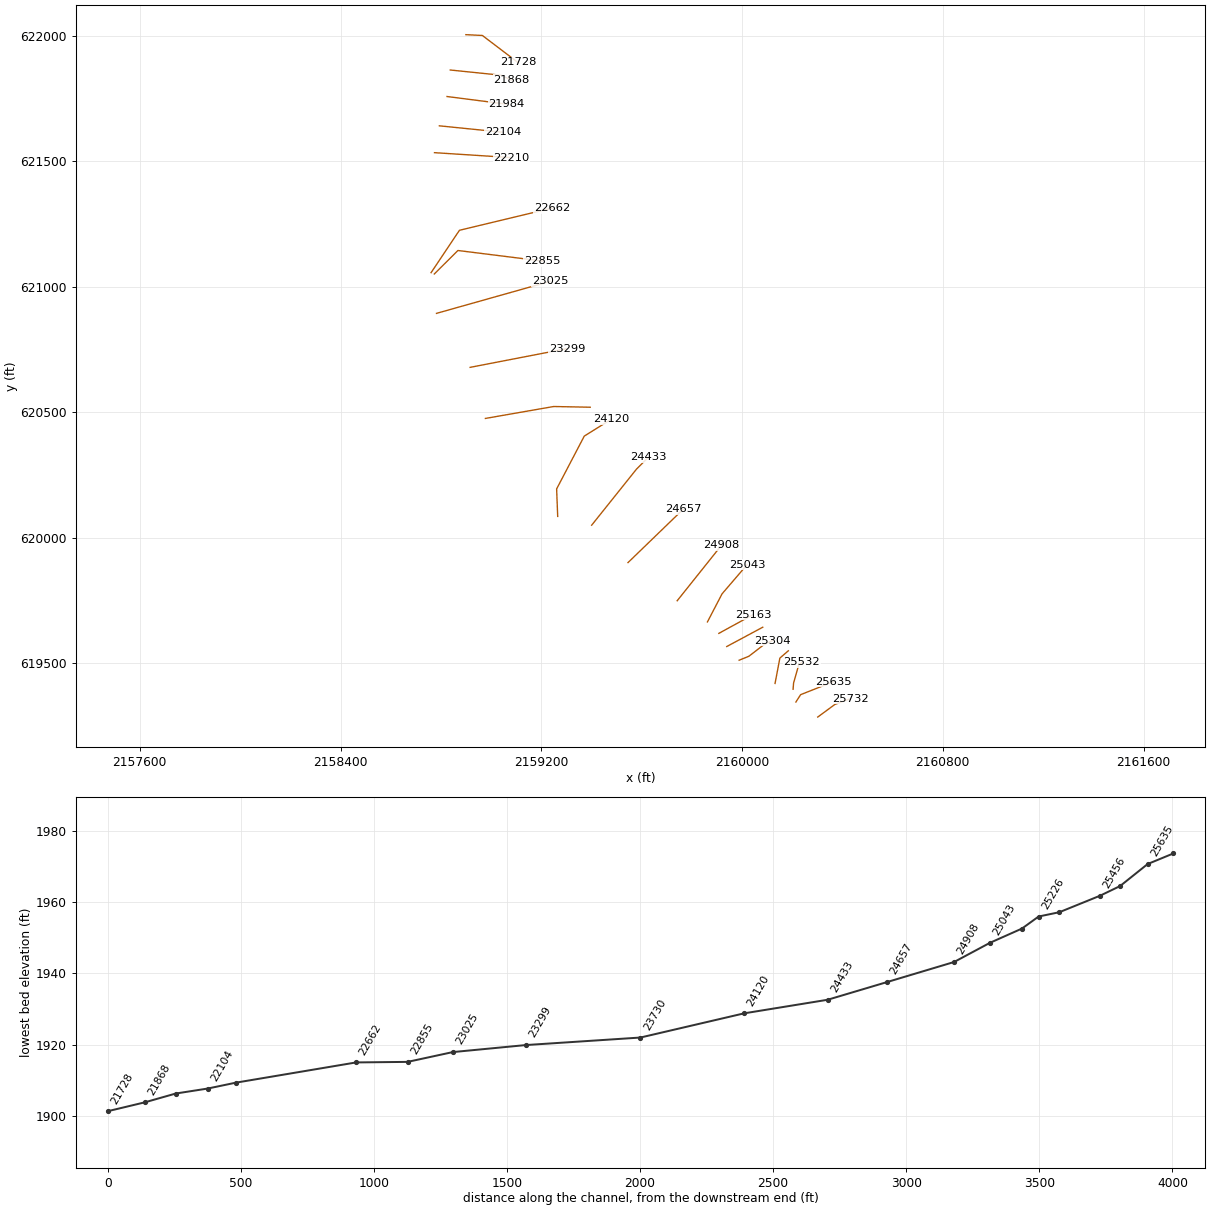
HEC-RAS study LFRFLIKANA.prj: LFRFLIKANA

--- LFRFLIKANA.g01 (geometry) --- (continued)

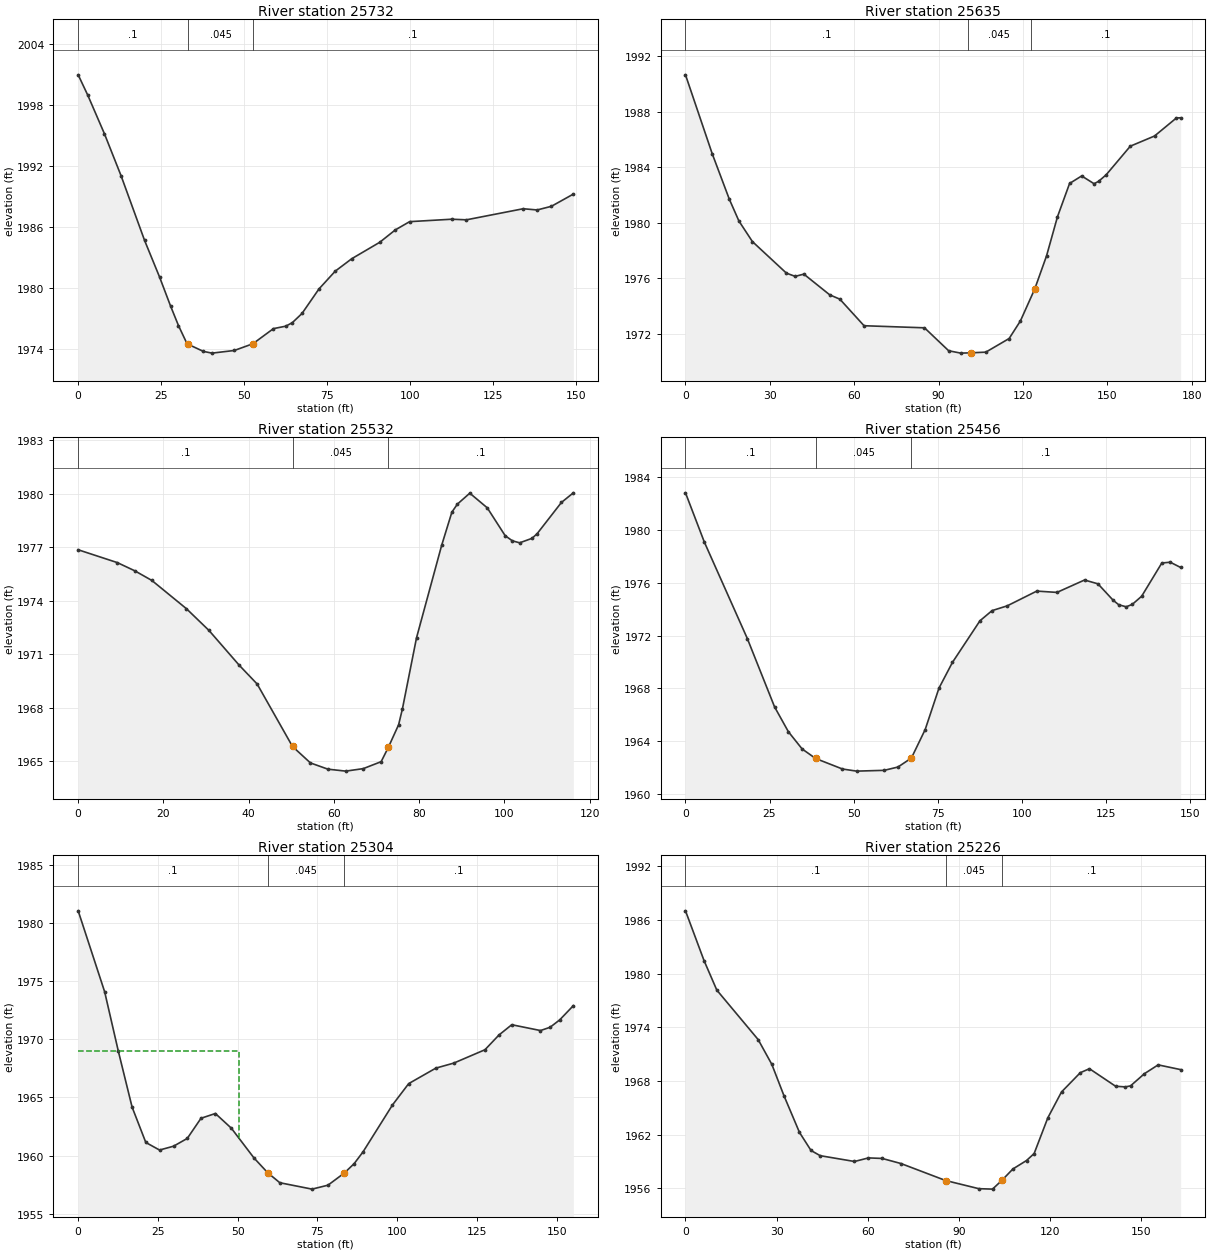
Type RM Length L Ch R = 1 ,25732   ,101.5,96.9,94.2
XS GIS Cut Line= 3
2160301.81774634619285.3019415942160369.85724979619335.386576078
2160430.33680841619358.066410561
#Sta/Elev= 30
       0 2000.98     2.9 1998.97     7.9 1995.19    12.9 1991.07      20 1984.69
    24.5  1981.1    27.8 1978.26    30.2 1976.32    32.7 1974.59    33.1 1974.48
    37.7 1973.78    40.3 1973.61      47 1973.87    52.6 1974.53    58.8 1976.02
    62.5 1976.26    64.5 1976.61    67.4 1977.51    72.5 1979.92    77.4 1981.67
    82.4  1982.9    90.8 1984.51    95.5 1985.73    99.8 1986.54   112.5 1986.78
   116.9 1986.72     134 1987.81   138.2 1987.69   142.5 1988.05   149.1 1989.25
#Mann= 3 ,-1,0
       0      .1       0    33.1    .045       0    52.6      .1       0
Bank Sta=33.1,52.6
XS Rating Curve= 0 ,0
Exp/Cntr(USF)=0,0
Exp/Cntr=0.3,0.1

Type RM Length L Ch R = 1 ,25635   ,94.1,103.6,123.5
XS GIS Cut Line= 3
2160214.62971343619345.172616773 2160233.5295755 619374.46740298
2160364.88361688619426.442023671
#Sta/Elev= 30
       0 1990.64     9.5 1984.97    15.6 1981.69      19 1980.13    23.8 1978.65
    35.9 1976.38      39 1976.15    42.1 1976.31    51.3 1974.82    54.9 1974.51
    63.5  1972.6      85 1972.45    93.6  1970.8    97.9 1970.63   101.61970.653
   106.8  1970.7   115.1 1971.68   119.1 1972.94   124.21975.239   128.4 1977.62
   132.3 1980.44   136.6 1982.83   140.9 1983.37   145.3 1982.81   146.9 1982.98
   149.6 1983.45   158.2 1985.51   166.8 1986.24   174.6 1987.54   176.1 1987.55
#Mann= 3 ,-1,0
       0      .1       0   100.3    .045       0   122.9      .1       0
Bank Sta=101.6,124.2
XS Rating Curve= 0 ,0
Exp/Cntr(USF)=0,0
Exp/Cntr=0.3,0.1

Type RM Length L Ch R = 1 ,25532   ,74.3,75.7,77.1
XS GIS Cut Line= 4
2160203.52189992619395.9103524842160205.41188612619420.480173174
 2160226.2017344619494.1896352442160238.48664474619502.694573175
#Sta/Elev= 30
       0 1976.85     9.2 1976.13    13.3 1975.67    17.3 1975.13    25.4 1973.55
    30.7 1972.33    37.8 1970.38      42 1969.33    50.3 1965.83    54.5 1964.91
    58.6 1964.56    62.8 1964.45    66.9 1964.59    71.1 1964.98    72.8 1965.79
    75.2 1967.05    76.1 1967.95    79.4 1971.92    85.3  1977.1    87.7 1978.96
      89 1979.41    91.9 1980.02      96  1979.2   100.2 1977.64   101.9 1977.35
   103.6 1977.24   106.5 1977.49   107.7 1977.75   113.4  1979.5   116.2 1980.04
#Mann= 3 ,-1,0
       0      .1       0    50.3    .045       0    72.8      .1       0
Bank Sta=50.3,72.8
XS Rating Curve= 0 ,0
Exp/Cntr(USF)=0,0
Exp/Cntr=0.3,0.1

Type RM Length L Ch R = 1 ,25456   ,158,152.3,124.9
XS GIS Cut Line= 3
 2160131.6397901619419.1269922732160150.77590045619520.165654895
2160184.45545466619549.252542619
#Sta/Elev= 30
       0 1982.83     5.6  1979.1    18.4 1971.78    26.5  1966.6    30.6 1964.72
    34.7 1963.41    38.7 1962.69    46.7 1961.89    50.9 1961.73    59.1 1961.79
    63.2 1962.04    67.2 1962.72    71.3 1964.88    75.4 1968.02    79.4 1969.97
    87.6 1973.13    91.2  1973.9    95.7 1974.26   104.5 1975.38   110.5 1975.28
   118.7 1976.22   122.7 1975.93   127.2 1974.69   128.9 1974.34   131.1 1974.19
   132.9 1974.37   135.7 1974.99   141.7 1977.51   144.2 1977.57   147.3 1977.17
#Mann= 3 ,-1,0
       0      .1       0    38.7    .045       0    67.2      .1       0
Bank Sta=38.7,67.2
XS Rating Curve= 0 ,0
Exp/Cntr(USF)=0,0
Exp/Cntr=0.3,0.1

Type RM Length L Ch R = 1 ,25304   ,77.2,78,69.9
XS GIS Cut Line= 4
2159988.50168472619511.7457663432160027.22712874619527.456604405
2160087.34793001619573.7632409792160121.20236179619589.912194071
#Sta/Elev= 30
       0 1981.04     8.3 1974.08    12.6 1968.96    16.9 1964.17    21.2 1961.13
    25.5 1960.48    29.9 1960.81    34.2 1961.48    38.5 1963.21      43 1963.62
      48 1962.36    55.1  1959.8    59.4 1958.53    63.2 1957.67    73.3 1957.12
    78.3 1957.46    83.4  1958.5    86.5 1959.31    89.3 1960.33    98.5 1964.35
   103.6 1966.19   112.1 1967.52   117.7 1967.95   127.5  1969.1   131.9 1970.37
   135.9 1971.25   144.9 1970.75   147.9 1971.03   150.9 1971.66   155.2 1972.89
#Mann= 3 ,-1,0
       0      .1       0    59.4    .045       0    83.4      .1       0
#XS Ineff= 2 , 0
           50.48 1968.98
Permanent Ineff=
       F       F
Bank Sta=59.4,83.4
XS Rating Curve= 0 ,0
Exp/Cntr(USF)=0,0
Exp/Cntr=0.3,0.1

Type RM Length L Ch R = 1 ,25226   ,62.7,62.6,62.2
XS GIS Cut Line= 2
2159939.14221506619566.2767141322160082.64116781619643.276152192
#Sta/Elev= 30
       0 1987.02     6.1 1981.46    10.3 1978.16    23.9 1972.63    28.4 1969.86
    32.4 1966.35    37.5 1962.25    41.3 1960.23    44.3 1959.65    55.6    1959
    60.2  1959.4    64.7 1959.34    70.9 1958.77    85.6 1956.87    96.5 1955.96
     101 1955.91   104.11956.894   107.7 1958.16   112.2 1959.11   114.7 1959.89
   119.2 1963.88   123.7 1966.77   129.9 1968.93   132.9 1969.37   141.5 1967.41
   144.7 1967.34   146.4 1967.45     151 1968.82   155.5  1969.8   162.9 1969.27
#Mann= 3 ,-1,0
       0      .1       0    85.6    .045       0   104.1      .1       0
Bank Sta=85.6,104.1
XS Rating Curve= 0 ,0
Exp/Cntr(USF)=0,0
Exp/Cntr=0.3,0.1

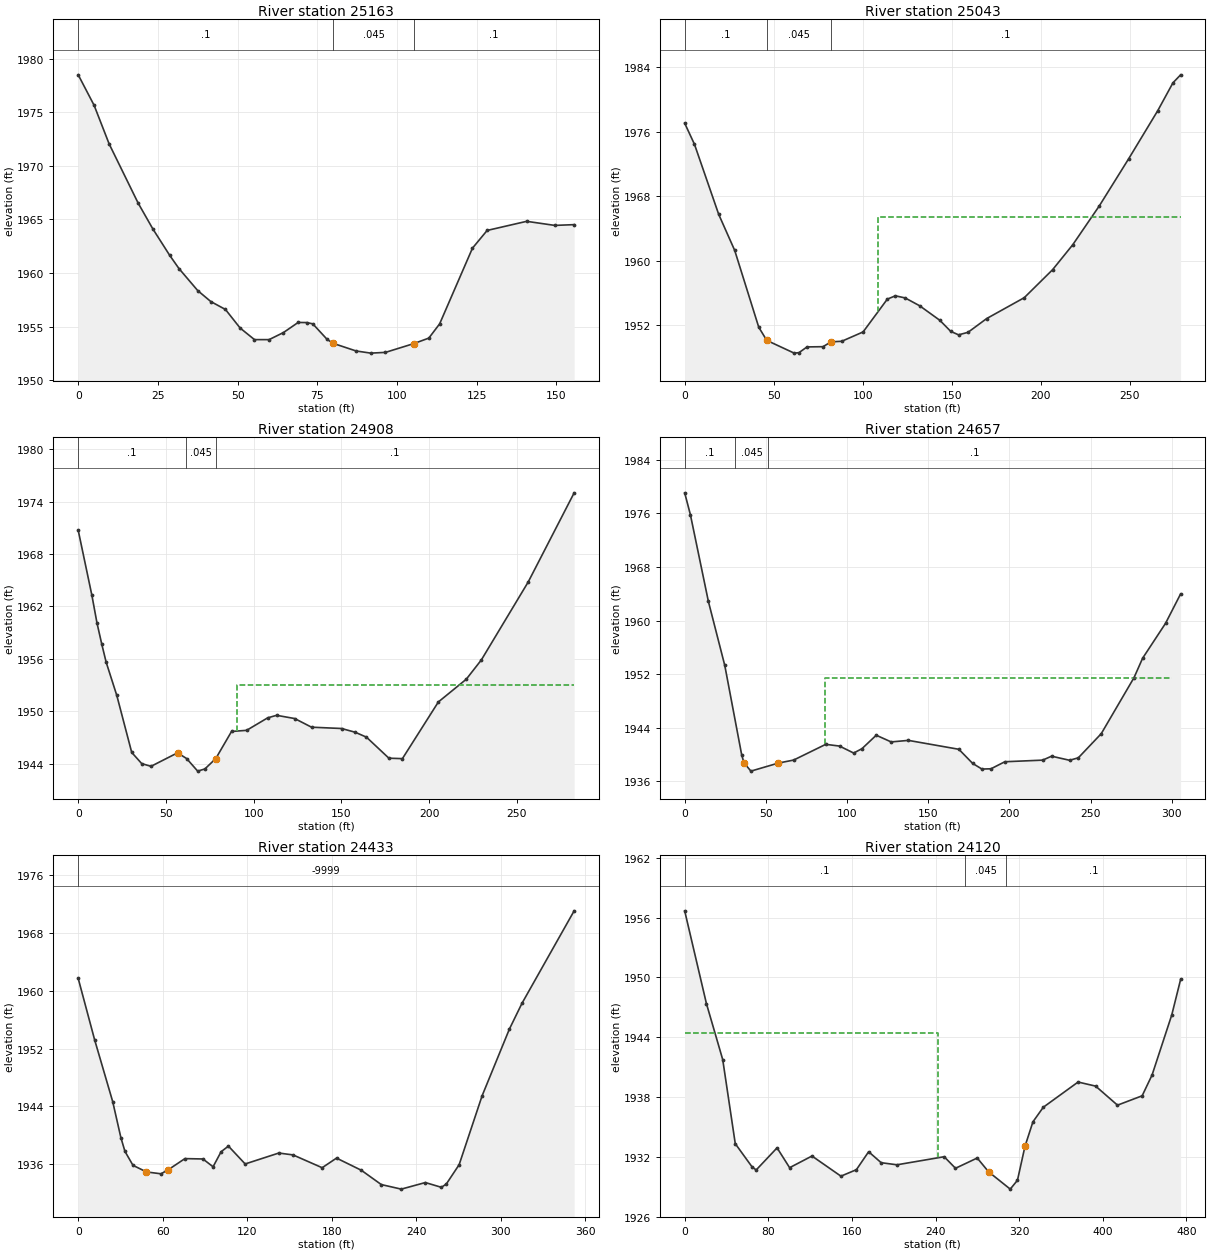
Type RM Length L Ch R = 1 ,25163   ,107.1,120.1,128.5
XS GIS Cut Line= 2
2159907.64244494619618.7763309912160044.14144878619693.442452746
#Sta/Elev= 30
       0 1978.48       5 1975.63     9.7 1972.04    18.8 1966.52    23.4 1964.12
    28.7 1961.65    31.6 1960.42    37.5 1958.36    41.6 1957.34    46.2  1956.6
    50.8 1954.87    55.3 1953.79    59.9 1953.79    64.4 1954.45      69 1955.39
    71.7 1955.38    73.6 1955.26    78.1 1953.81      80 1953.44    87.2 1952.73
    91.8 1952.53    96.4  1952.6   105.3 1953.42     110 1953.93   113.4 1955.26
   123.7 1962.32   128.3 1963.97   140.7 1964.82   149.5 1964.44   155.6 1964.51
#Mann= 3 ,-1,0
       0      .1       0      80    .045       0   105.3      .1       0
Bank Sta=80,105.3
XS Rating Curve= 0 ,0
Exp/Cntr(USF)=0,0
Exp/Cntr=0.3,0.1

Type RM Length L Ch R = 1 ,25043   ,139.8,135,132.5
XS GIS Cut Line= 3
  2159862.142777619664.2759989362159920.47568462619776.275181568
2160019.64162757619891.774338658
#Sta/Elev= 30
       0 1977.07     5.5 1974.45    19.1 1965.76    28.1 1961.28    41.6 1951.75
    46.1 1950.12    61.5 1948.54    64.2  1948.6    68.7 1949.31    77.7 1949.34
    82.2 1949.94    88.2 1950.01   100.2 1951.17   113.8 1955.24   118.3 1955.65
   123.8 1955.39     132 1954.41   143.3 1952.61   149.4 1951.24   153.8 1950.81
   159.1 1951.12   169.6 1952.83   190.7 1955.42   206.6 1958.89   217.9 1961.98
   232.9 1966.83   249.4 1972.68   265.7 1978.64   274.2 1982.08   278.5 1983.07
#Mann= 3 ,-1,0
       0      .1       0    46.1    .045       0    82.2      .1       0
#XS Ineff= 2 , 0
                          108.34         1965.45
Permanent Ineff=
       F       F
Bank Sta=46.1,82.2
XS Rating Curve= 0 ,0
Exp/Cntr(USF)=0,0
Exp/Cntr=0.3,0.1

Type RM Length L Ch R = 1 ,24908   ,251.8,251.5,246.3
XS GIS Cut Line= 2
2159741.67222719619748.7823133372159918.11193478619969.719263999
#Sta/Elev= 30
       0 1970.72     7.8 1963.27    10.7 1960.11    13.4 1957.71    15.9 1955.64
      22 1951.81    30.5 1945.29    36.2 1944.01    41.5  1943.7    56.61945.243
    61.8 1944.59    68.1 1943.15    72.2  1943.4    78.41944.584    87.4 1947.69
      96 1947.82     108 1949.25   113.1 1949.54   123.4 1949.17     133 1948.18
   150.1 1948.03   157.9  1947.6   164.3 1947.04   177.1 1944.63   184.8 1944.58
   205.3 1951.07   221.2 1953.67   229.8 1955.88   256.5  1964.8   282.7 1975.01
#Mann= 3 ,-1,0
       0      .1       0    61.3    .045       0    78.4      .1       0
#XS Ineff= 2 , 0
                           90.42         1953.02
Permanent Ineff=
       F       F
Bank Sta=56.6,78.4
XS Rating Curve= 0 ,0
Exp/Cntr(USF)=0,0
Exp/Cntr=0.3,0.1

Type RM Length L Ch R = 1 ,24657   ,220.1,223.6,221.9
XS GIS Cut Line= 2
2159545.66793223619900.7942638932159765.29227722 620113.08966731
#Sta/Elev= 30
       0 1979.08     3.5 1975.84    14.6 1962.87    24.7 1953.31    35.1 1939.98
    36.5 1938.78    40.8 1937.53    57.71938.733    67.1 1939.18    86.9 1941.53
    95.4 1941.27   104.1 1940.23   109.2 1940.88     118 1942.89   127.2 1941.89
   137.8 1942.12   168.9 1940.79   177.4 1938.68   183.1 1937.84   188.7 1937.88
   197.2 1938.93   220.5 1939.17     226 1939.76   237.1 1939.15   242.5 1939.52
   256.6 1943.12   276.8 1951.49   282.1 1954.39   296.2 1959.59   305.5 1963.99
#Mann= 3 ,-1,0
       0      .1       0      31    .045       0    51.3      .1       0
#XS Ineff= 1 ,-1
    86.7   299.9 1951.43
Permanent Ineff=
       F
Bank Sta=36.5,57.7
XS Rating Curve= 0 ,0
Exp/Cntr(USF)=0,0
Exp/Cntr=0.3,0.1

Type RM Length L Ch R = 1 ,24433   ,294.9,313.2,316.7
XS GIS Cut Line= 3
2159400.86340193 620049.862949332159579.17250391620272.873497485
2159626.35736376620320.058357339
#Sta/Elev= 30
       0 1961.69    11.7 1953.18    24.5 1944.66    30.3 1939.69    33.2 1937.78
    38.9 1935.85    48.51934.935    58.8 1934.68    63.8 1935.22    75.8 1936.78
    88.6 1936.73    95.8 1935.65   101.5 1937.73   106.7 1938.51   118.6 1936.04
   142.5 1937.55   152.6 1937.29   173.3 1935.52   183.5 1936.85   201.1 1935.17
   215.3 1933.19   229.5 1932.56   246.6 1933.47     258 1932.81   261.5 1933.27
   270.6 1935.94   286.9 1945.46   306.3 1954.69   315.2 1958.24   352.3 1971.04
#Mann= 1 ,-1,0
       0   -9999       0
Bank Sta=48.5,63.8
XS Rating Curve= 0 ,0
Exp/Cntr(USF)=0,0
Exp/Cntr=0.3,0.1

Type RM Length L Ch R = 1 ,24120   ,389.8,389.9,374.5
XS GIS Cut Line= 4
2159265.45028313620084.8214116832159261.18390172620194.315929192
 2159371.3879962620404.8298902372159479.38170777620472.276801538
#Sta/Elev= 30
       0 1956.67    20.8 1947.37    36.4 1941.75    48.4 1933.32    64.4    1931
    68.4 1930.68    88.4  1932.9   100.4 1930.91   121.8 1932.08   149.5 1930.06
   164.3 1930.71     176 1932.51     188 1931.41   203.1  1931.2   248.3 1932.01
   259.1 1930.85   279.9 1931.88   290.81930.494   311.5 1928.76   318.4 1929.65
   325.61933.057   333.2 1935.51   343.1 1936.97   376.4  1939.5   393.2 1939.09
   414.1 1937.18   437.7 1938.12   447.2 1940.21     466 1946.22   474.5 1949.79
#Mann= 3 ,-1,0
       0      .1       0   268.3    .045       0   307.4      .1       0
#XS Ineff= 2 , 0
           242.7 1944.42
Permanent Ineff=
       F       F
Bank Sta=290.8,325.6
XS Rating Curve= 0 ,0
Exp/Cntr(USF)=0,0
Exp/Cntr=0.3,0.1

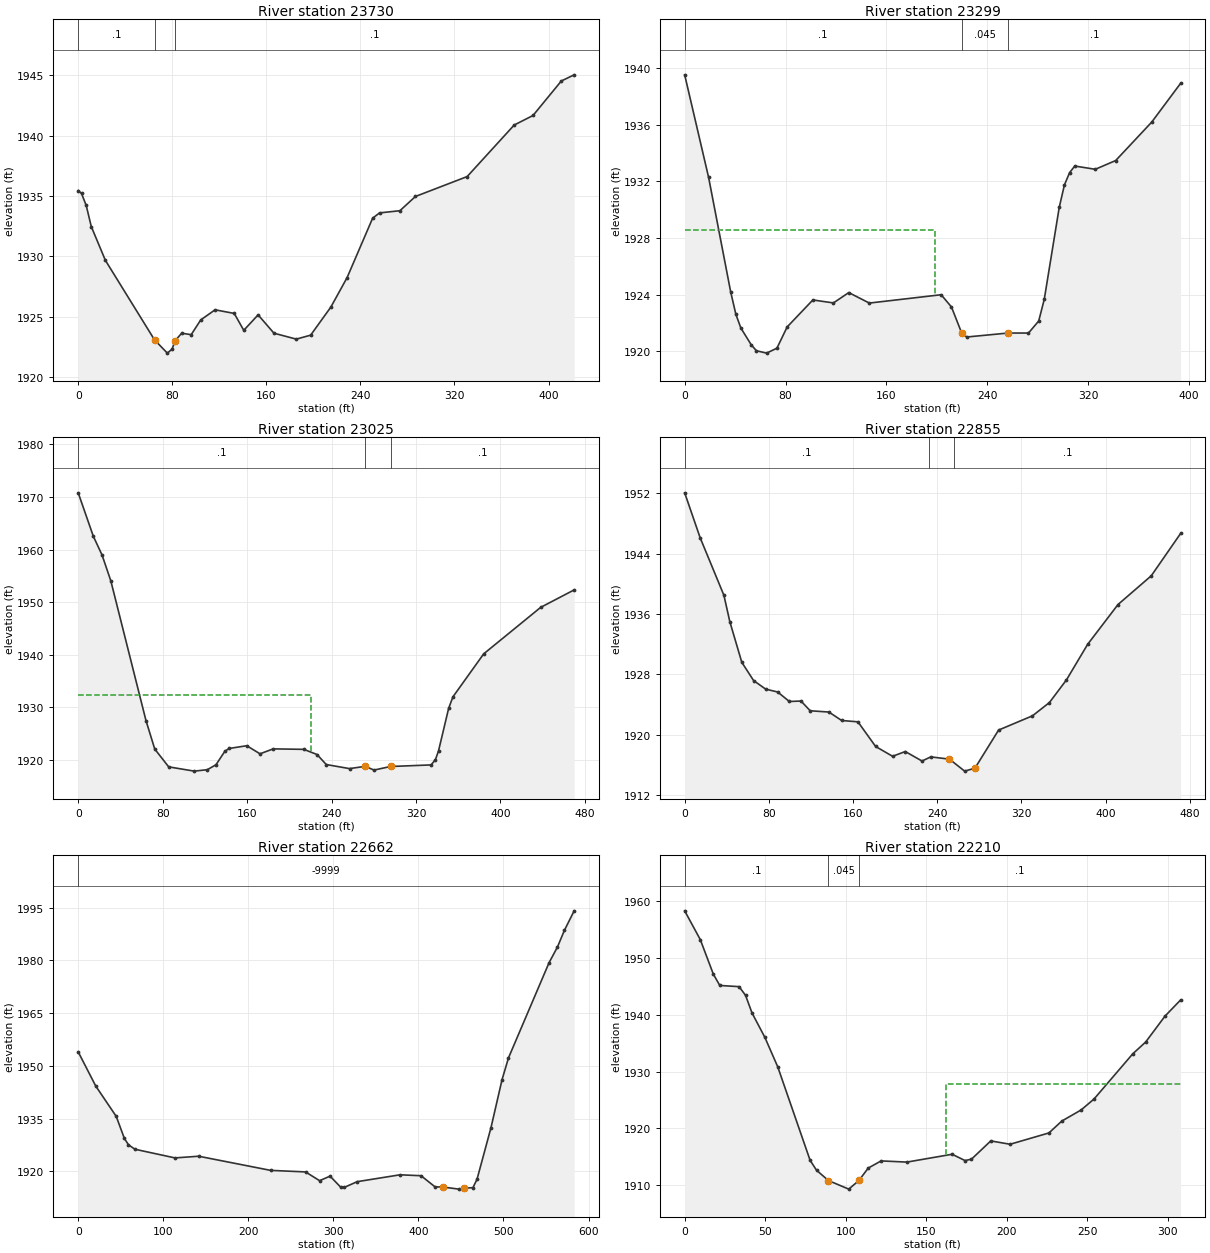
Type RM Length L Ch R = 1 ,23730   ,391.8,430.4,430.9
XS GIS Cut Line= 3
2158977.46539542620475.2690700822159249.68563098620522.799587403
2159395.15782036 620519.91894999
#Sta/Elev= 30
       0 1935.44     2.8  1935.2     6.8 1934.21    11.1 1932.46    23.1 1929.66
    64.9 1923.07    75.8 1921.97    79.9 1922.31    82.31922.983      88 1923.62
    96.1  1923.5   104.2 1924.72   116.4 1925.56   132.7 1925.26   140.8 1923.86
     153 1925.14   166.5 1923.62   185.5 1923.13   197.7 1923.46   214.9 1925.79
   228.7 1928.23   250.4 1933.15   256.3 1933.59   273.6 1933.77   286.8 1934.95
   330.8  1936.6   370.8 1940.87   386.8 1941.66   410.9 1944.52   421.8 1945.03
#Mann= 3 ,-1,0
       0      .1       0    64.9    .045       0    82.3      .1       0
Bank Sta=64.9,82.3
XS Rating Curve= 0 ,0
Exp/Cntr(USF)=0,0
Exp/Cntr=0.3,0.1

Type RM Length L Ch R = 1 ,23299   ,267.8,274.4,274
XS GIS Cut Line= 2
 2158916.3366739620678.8058678132159302.70474642620753.445154549
#Sta/Elev= 30
       0 1939.54      19 1932.28    36.5 1924.19    40.6 1922.61    44.6 1921.63
    52.8 1920.45    56.9 1920.03      65 1919.86    73.2 1920.21    81.3 1921.71
   101.7 1923.62     118 1923.41   130.2 1924.14   146.5  1923.4   203.5 1923.99
   211.7 1923.12   219.8 1921.28   223.8    1921   256.5 1921.28   272.8 1921.28
   280.9 1922.13   285.3 1923.66   297.2 1930.17   301.3 1931.75   305.4 1932.62
   309.5 1933.09   325.8 1932.86     342 1933.48   370.6  1936.2   393.5 1938.94
#Mann= 3 ,-1,0
       0      .1       0   219.8    .045       0   256.5      .1       0
#XS Ineff= 2 , 0
          198.54  1928.6
Permanent Ineff=
       F       F
Bank Sta=219.8,256.5
XS Rating Curve= 0 ,0
Exp/Cntr(USF)=0,0
Exp/Cntr=0.3,0.1

Type RM Length L Ch R = 1 ,23025   ,178.3,170,165.1
XS GIS Cut Line= 2
 2158782.4250124620893.942635464 2159234.6512791621021.268477544
#Sta/Elev= 30
       0 1970.79    14.3 1962.54    22.6 1958.96    30.9 1954.05    64.2  1927.5
    72.5 1922.09    85.7  1918.7   109.9 1917.89   122.3 1918.16   130.5  1919.1
     139 1921.69   143.1  1922.2   159.7 1922.72   172.2 1921.18   184.7 1922.12
   213.7 1922.03   226.2 1921.05     235 1919.14     257 1918.37   271.9  1918.8
   280.2 1918.09   295.9 1918.77   334.3 1919.07   338.4 1920.08   341.3 1921.72
   350.9 1929.82     355 1932.02   384.1 1940.18   438.1 1949.02   469.8 1952.34
#Mann= 3 ,-1,0
       0      .1       0   271.9    .045       0   295.9      .1       0
#XS Ineff= 2 , 0
          220.28 1932.34
Permanent Ineff=
       F       F
Bank Sta=271.9,295.9
XS Rating Curve= 0 ,0
Exp/Cntr(USF)=0,0
Exp/Cntr=0.3,0.1

Type RM Length L Ch R = 1 ,22855   ,184.6,193,197
XS GIS Cut Line= 3
2158773.74156532621050.8523532572158867.85445492621144.502058502
2159203.91745515621102.493583698
#Sta/Elev= 30
       0 1952.07    14.7 1946.11    37.3 1938.47    42.9 1934.98    54.3 1929.58
    65.5 1927.16      77 1926.02    88.4 1925.64    99.5 1924.38   110.6 1924.44
   119.3 1923.15   137.1 1922.98   149.2 1921.86   164.7 1921.68   181.5 1918.41
   197.6 1917.11   209.7 1917.74   225.6 1916.48   233.9 1917.03   251.7 1916.73
   266.1 1915.14   275.9 1915.53   298.4 1920.59   330.6 1922.48   346.7 1924.24
   362.9 1927.25     383 1931.96   411.9 1937.25   443.5 1941.06   471.4 1946.68
#Mann= 3 ,-1,0
       0      .1       0   231.8    .045       0   256.4      .1       0
Bank Sta=251.7,275.9
XS Rating Curve= 0 ,0
Exp/Cntr(USF)=0,0
Exp/Cntr=0.3,0.1

Type RM Length L Ch R = 1 ,22662   ,448.5,452.3,443.3
XS GIS Cut Line= 3
2158760.85753885621056.0639800262158873.95676253 621225.03149492
2159243.23254105621313.603176114
#Sta/Elev= 30
       0 1953.99    20.6 1944.29    44.7 1935.66    54.3 1929.38    59.1  1927.6
    66.6 1926.33   113.8 1923.86   141.6 1924.34   226.2 1920.32   267.3 1919.88
   283.8 1917.39   296.1 1918.68   308.4  1915.6   312.6 1915.46     328 1917.11
   378.4 1919.06   403.1  1918.8   419.5 1915.64   428.91915.589   447.5 1914.99
   453.71915.251   464.1 1915.41   468.9 1917.79   485.3 1932.44   498.3 1946.08
   505.9 1952.29   553.6 1979.34   563.5 1983.81   571.7 1988.56   583.1 1994.08
#Mann= 1 ,-1,0
       0   -9999       0
Bank Sta=428.9,453.7
XS Rating Curve= 0 ,0
Exp/Cntr(USF)=0,0
Exp/Cntr=0.3,0.1

Type RM Length L Ch R = 1 ,22210   ,105.8,105.7,104.9
XS GIS Cut Line= 2
2158774.45925178621534.3365521092159081.79749128621514.579093855
#Sta/Elev= 30
       0 1958.31     9.7 1953.24    17.8 1947.16    21.8 1945.17    33.8 1944.96
    37.8 1943.43    41.8 1940.34    49.8 1936.03    57.8 1930.84    77.9 1914.38
    81.9 1912.63    89.3 1910.82   101.9 1909.31   108.2 1910.83     114 1913.02
     122 1914.28     138 1914.07   166.1 1915.45   174.1 1914.34   178.1 1914.58
   190.1  1917.8   202.1 1917.21   226.2  1919.2   234.2 1921.29   246.2 1923.25
   254.2 1925.17   278.3 1933.14   286.3 1935.21   298.3 1939.77     308 1942.62
#Mann= 3 ,-1,0
       0      .1       0    89.3    .045       0   108.2      .1       0
#XS Ineff= 2 , 0
                          162.48         1927.89
Permanent Ineff=
       F       F
Bank Sta=89.3,108.2
XS Rating Curve= 0 ,0
Exp/Cntr(USF)=0,0
Exp/Cntr=0.3,0.1

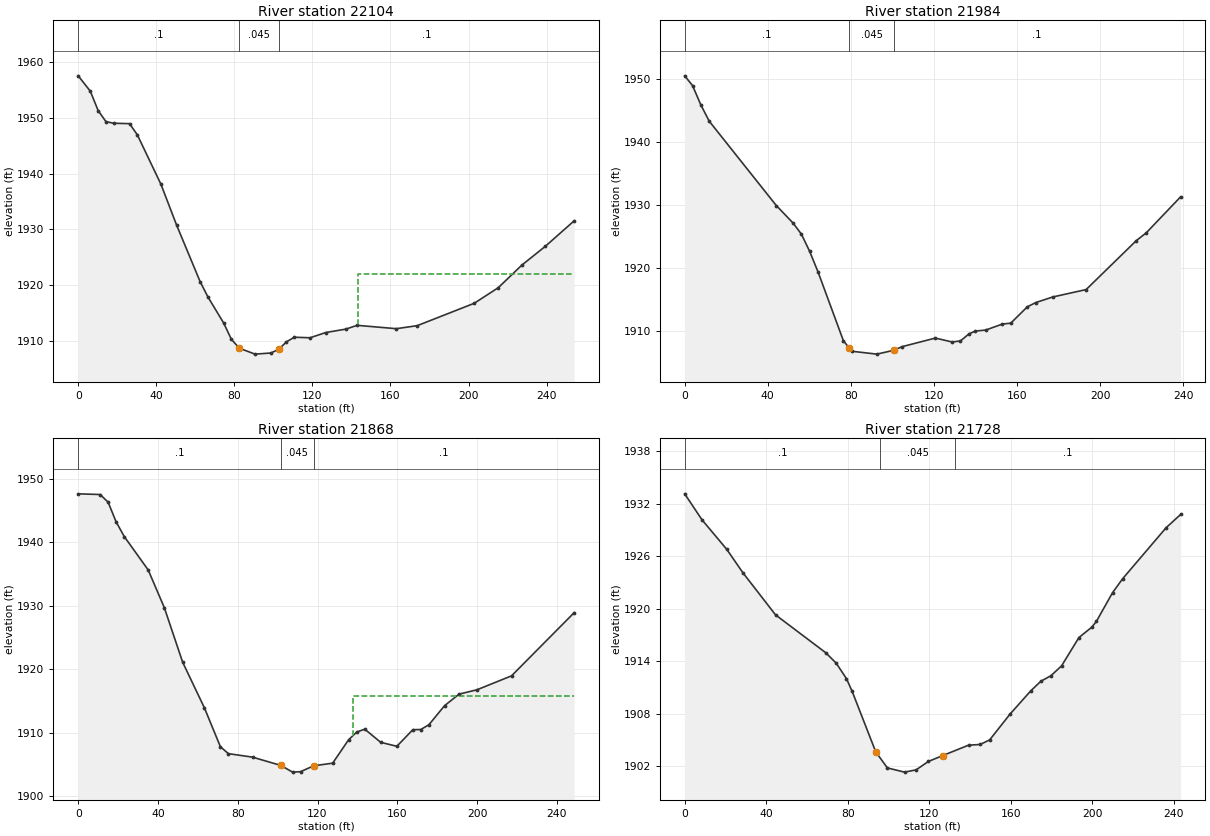
Type RM Length L Ch R = 1 ,22104   ,119.2,119.7,119.1
XS GIS Cut Line= 2
 2158794.0250858621641.2929475252159046.88103653621615.687281628
#Sta/Elev= 30
       0 1957.53     6.2 1954.78    10.2 1951.31    14.2 1949.33    18.2 1949.03
    26.3 1948.96    30.3 1946.95    42.4 1938.09    50.4 1930.79    62.5 1920.62
    66.5 1917.88    74.5 1913.25    78.5  1910.3    82.6 1908.71    90.6 1907.66
    98.7 1907.86   102.7 1908.51   106.7 1909.86   110.7 1910.69   118.8 1910.59
   126.8 1911.53   137.1 1912.14   142.9 1912.82     163 1912.22   173.7 1912.76
   202.9 1916.77   215.2 1919.56   227.3 1923.61   239.4    1927   254.1 1931.55
#Mann= 3 ,-1,0
       0      .1       0    82.6    .045       0   102.7      .1       0
#XS Ineff= 2 , 0
                          143.32         1922.09
Permanent Ineff=
       F       F
Bank Sta=82.6,102.7
XS Rating Curve= 0 ,0
Exp/Cntr(USF)=0,0
Exp/Cntr=0.3,0.1

Type RM Length L Ch R = 1 ,21984   ,115.8,116.2,115.3
XS GIS Cut Line= 2
2158824.43181405621758.118798179 2159061.2842236621727.712069926
#Sta/Elev= 30
       0  1950.5     3.8 1948.94     7.8 1945.87    11.8  1943.3    44.1 1929.89
    52.2  1927.1    56.2 1925.34    60.2 1922.59    64.3 1919.26    76.4 1908.42
    79.2 1907.24    80.4 1906.73    92.5 1906.27   100.7 1906.88   104.6 1907.45
   120.7 1908.82   128.8  1908.2   132.8 1908.37   136.9 1909.49     140 1909.94
   144.9 1910.09     153 1911.05     157 1911.19     165 1913.79   169.1 1914.47
   177.2 1915.35   193.3 1916.53   217.5 1924.32   222.2 1925.53   238.8 1931.27
#Mann= 3 ,-1,0
       0      .1       0    79.2    .045       0   100.7      .1       0
Bank Sta=79.2,100.7
XS Rating Curve= 0 ,0
Exp/Cntr(USF)=0,0
Exp/Cntr=0.3,0.1

Type RM Length L Ch R = 1 ,21868   ,147.2,139.8,129.1
XS GIS Cut Line= 3
  2158837.234647621863.7421700032159040.47962006621842.937566462
2159080.48847302621823.733317039
#Sta/Elev= 30
       0 1947.62      11 1947.51      15 1946.31      19 1943.21    23.1 1940.89
    35.1 1935.63    43.2 1929.68    52.4 1921.09    63.3 1913.91    71.3  1907.8
    75.3 1906.71    87.4 1906.16   101.61904.856   107.5  1903.8   111.5 1903.87
   118.1  1904.8   127.6 1905.21   135.6  1908.9   139.7 1910.12   143.7 1910.56
   151.7 1908.49   159.8 1907.87   167.8 1910.48   171.8 1910.51   175.9 1911.27
   183.7 1914.26     191 1916.08     200 1916.77   217.3 1918.96   248.7 1928.91
#Mann= 3 ,-1,0
       0      .1       0   101.6    .045       0   118.1      .1       0
#XS Ineff= 2 , 0
                          137.61         1915.83
Permanent Ineff=
       F       F
Bank Sta=101.6,118.1
XS Rating Curve= 0 ,0
Exp/Cntr(USF)=0,0
Exp/Cntr=0.3,0.1

Type RM Length L Ch R = 1 ,21728   ,132.1,133.5,133.7
XS GIS Cut Line= 3
2158899.64845763622004.5733324362158965.26297649622001.372624199
2159106.83967502621893.911031561
#Sta/Elev= 30
       0 1933.12     8.5 1930.15    20.6 1926.79    28.6 1924.09    44.6 1919.28
    69.3 1914.94    74.4 1913.75    79.4 1911.99    82.2 1910.53    93.81903.603
    99.5 1901.78   107.9  1901.3   113.6 1901.56   119.6 1902.52   126.61903.189
   139.3 1904.38     145 1904.46   149.7 1904.99   159.7 1907.94   169.8 1910.58
   174.8 1911.69   179.8 1912.33     185 1913.46   193.5 1916.69   199.9 1917.89
   202.1 1918.55     210 1921.82     215 1923.43   236.3 1929.25   243.4 1930.76
#Mann= 3 ,-1,0
       0      .1       0    96.1    .045       0   132.9      .1       0
Bank Sta=93.8,126.6
XS Rating Curve= 0 ,0
Exp/Cntr(USF)=0,0
Exp/Cntr=0.3,0.1