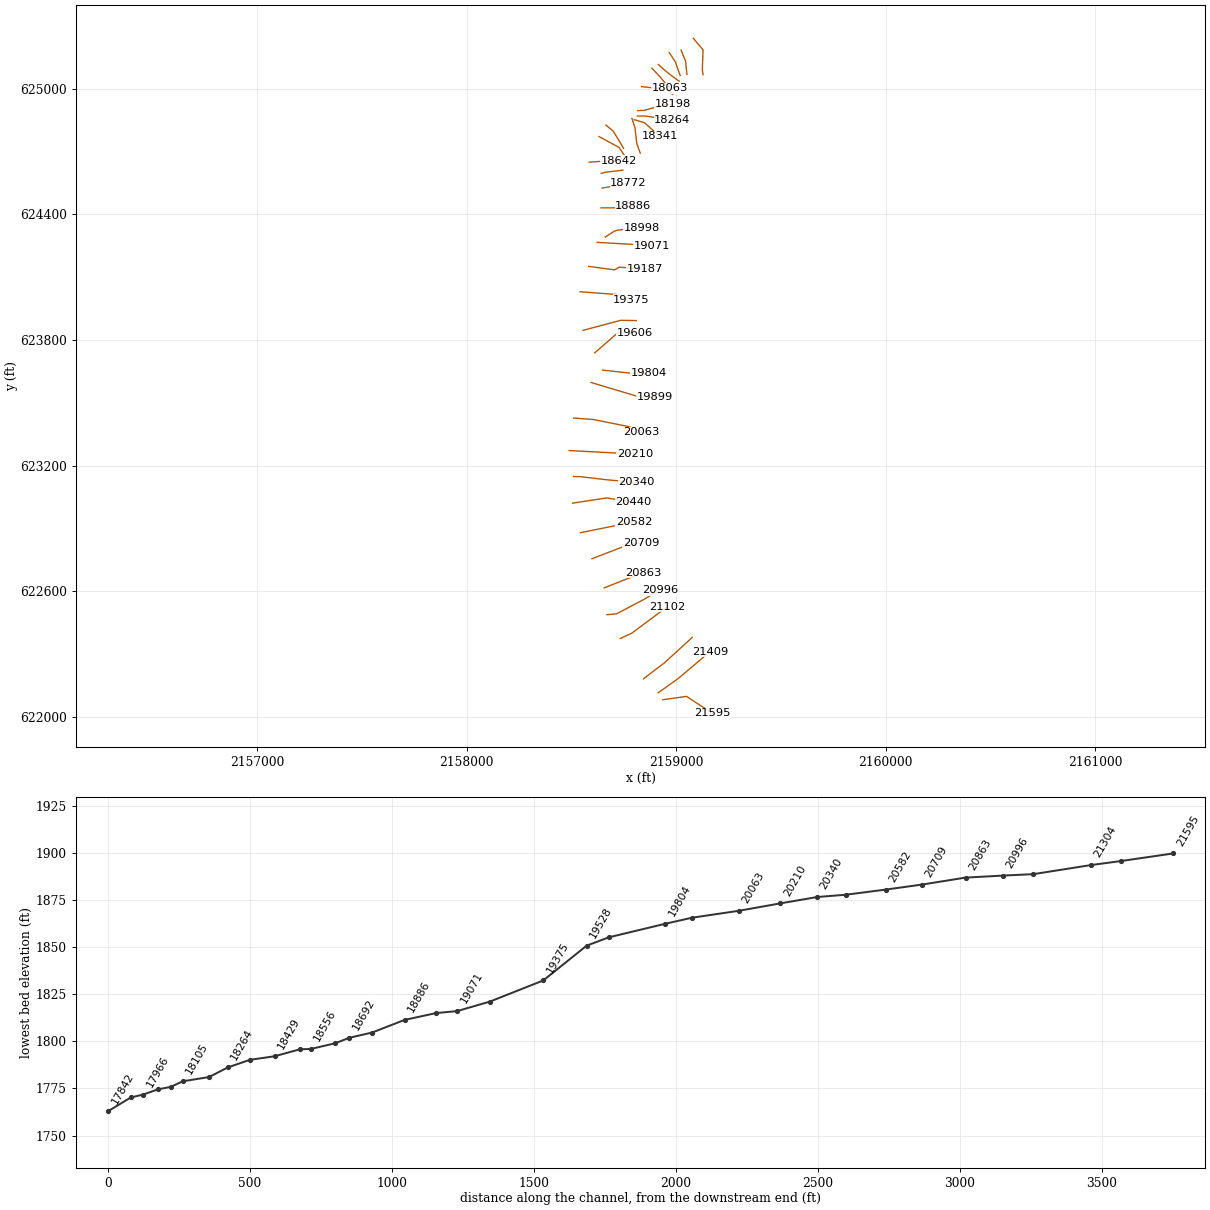
HEC-RAS study LFRFLIKANA.prj: LFRFLIKANA

--- LFRFLIKANA.g01 (geometry) --- (continued)

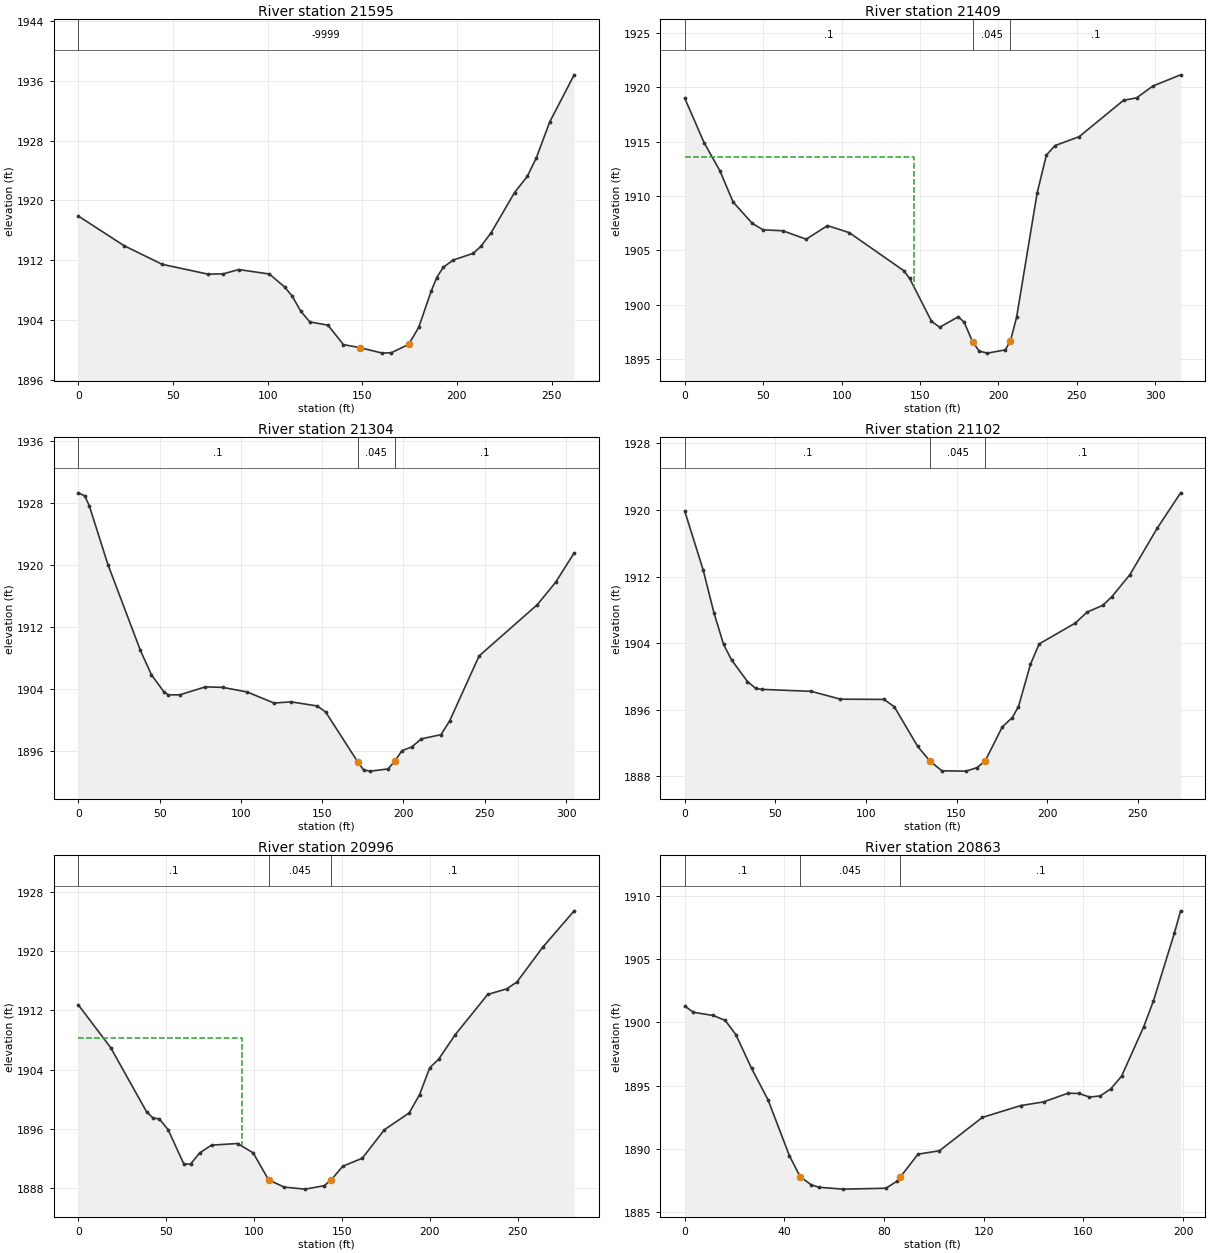
Type RM Length L Ch R = 1 ,21595   ,160.6,185.5,205.6
XS GIS Cut Line= 3
2158936.29918771622083.2797680052159049.63076421622099.211363423
2159172.73854698622018.105059478
#Sta/Elev= 30
       0 1917.92    24.1 1913.97    44.3 1911.47    68.5 1910.16    76.6  1910.2
    84.7 1910.77   100.9 1910.18   108.9 1908.46     113 1907.21   117.5  1905.2
   122.3 1903.78   131.9 1903.34     140 1900.75   148.81900.337   160.6 1899.61
   165.4 1899.67   174.51900.775   179.8 1903.06   186.4  1907.9   189.3  1909.7
   192.8 1911.09   198.1 1912.05   208.5 1912.93   212.7 1913.88   218.1 1915.72
   230.4 1921.05   237.2 1923.24   241.9 1925.68     249 1930.49   261.9 1936.78
#Mann= 1 ,-1,0
       0   -9999       0
Bank Sta=148.8,174.5
XS Rating Curve= 0 ,0
Exp/Cntr(USF)=0,0
Exp/Cntr=0.3,0.1

Type RM Length L Ch R = 1 ,21409   ,104.1,105.3,105.9
XS GIS Cut Line= 3
2158914.15739385622116.1850998762159009.41269868622184.224603326
2159161.65108765622312.649166086
#Sta/Elev= 30
       0 1918.99    12.3 1914.91    22.4 1912.32    30.8 1909.45      43 1907.49
    49.9 1906.89    62.4 1906.81    77.4 1906.03      91 1907.28   104.9 1906.63
   139.6 1903.14   143.4 1902.42   157.3 1898.49   162.5 1897.93   174.4 1898.89
   178.2 1898.39   183.5  1896.6   187.8 1895.73     193 1895.55   204.4 1895.85
   207.7 1896.69   211.6 1898.85   224.7 1910.28   230.6 1913.77   236.1 1914.64
   251.5 1915.46   279.8 1918.81   288.1 1919.03   298.5 1920.12   316.2 1921.15
#Mann= 3 ,-1,0
       0      .1       0   183.5    .045       0   207.7      .1       0
#XS Ineff= 2 , 0
          146.31 1913.62
Permanent Ineff=
       F       F
Bank Sta=183.5,207.7
XS Rating Curve= 0 ,0
Exp/Cntr(USF)=0,0
Exp/Cntr=0.3,0.1

Type RM Length L Ch R = 1 ,21304   ,203.9,202.3,200.7
XS GIS Cut Line= 3
2158844.41690282622183.3741095332158944.77517041622259.918550913
2159076.60170834622380.688669536
#Sta/Elev= 30
       0 1929.37       4 1928.97     6.8 1927.66    18.2 1920.11    38.2 1909.01
      45 1905.86    52.5 1903.71    55.3 1903.28    62.3 1903.28    78.2 1904.31
    88.7 1904.25   103.9 1903.65   120.4 1902.22   130.8 1902.38   147.1 1901.84
   152.2 1901.05     172 1894.58   175.5 1893.58   179.7 1893.43   190.5 1893.71
   194.6  1894.7   199.1 1896.08   205.1 1896.55     211  1897.6   223.1 1898.14
   228.5 1899.96   246.5  1908.3   282.4 1914.94   293.6 1917.82     305 1921.61
#Mann= 3 ,-1,0
       0      .1       0     172    .045       0   194.6      .1       0
Bank Sta=172,194.6
XS Rating Curve= 0 ,0
Exp/Cntr(USF)=0,0
Exp/Cntr=0.3,0.1

Type RM Length L Ch R = 1 ,21102   ,110,106.4,102.3
XS GIS Cut Line= 3
 2158732.8030835622375.1762113662158789.70456327622401.848780008
2158958.63083134 622528.09893825
#Sta/Elev= 30
       0 1919.85    10.1 1912.83    16.1 1907.64    21.4 1903.86    25.8 1901.99
    34.6 1899.39    39.1 1898.57    42.4 1898.45    69.8 1898.21    85.9 1897.27
   109.9 1897.24   115.6 1896.37   128.5 1891.61   135.2 1889.86   141.9 1888.66
   155.3 1888.62   161.3 1889.04   165.8 1889.84   175.3 1893.95   180.8 1895.06
   184.2 1896.38   190.8 1901.45   195.6 1903.91   215.6 1906.42   222.1 1907.74
   230.7 1908.54   235.7 1909.58   245.7 1912.23   260.7 1917.79   273.7 1922.07
#Mann= 3 ,-1,0
       0      .1       0   135.2    .045       0   165.8      .1       0
Bank Sta=135.2,165.8
XS Rating Curve= 0 ,0
Exp/Cntr(USF)=0,0
Exp/Cntr=0.3,0.1

Type RM Length L Ch R = 1 ,20996   ,135.1,132.6,129.4
XS GIS Cut Line= 4
2158669.87571112622489.2722864912158715.80237595622493.524755456
 2158845.0774325622561.5642589052158922.47236767622607.490923734
#Sta/Elev= 30
       0 1912.74    18.4 1906.97    38.8 1898.32    42.5 1897.47    46.1 1897.34
    51.1 1895.89    60.1 1891.23    63.9 1891.25    69.1 1892.76    75.8  1893.8
    90.6 1894.02    99.5 1892.76   108.3 1889.11   117.2 1888.13   129.1 1887.86
   139.9 1888.32   143.9 1889.11   150.5 1890.95   161.6 1892.03   174.2 1895.88
   188.3 1898.15   194.2 1900.62     200 1904.25   205.1 1905.41   214.4 1908.68
     233 1914.15   243.8  1914.9   249.7 1915.85   264.2 1920.49   282.2 1925.44
#Mann= 3 ,-1,0
       0      .1       0   108.3    .045       0   143.9      .1       0
#XS Ineff= 2 , 0
            93.3 1908.33
Permanent Ineff=
       F       F
Bank Sta=108.3,143.9
XS Rating Curve= 0 ,0
Exp/Cntr(USF)=0,0
Exp/Cntr=0.3,0.1

Type RM Length L Ch R = 1 ,20863   ,152.3,154.1,153.8
XS GIS Cut Line= 2
2158657.05659545622617.5527969322158842.27524373622690.317265898
#Sta/Elev= 30
       0  1901.3     3.4  1900.8    11.4 1900.55    16.2 1900.16    20.5 1899.03
    26.8 1896.36    33.4 1893.87      42 1889.43    46.3 1887.78    50.6 1887.15
    53.7 1886.94    63.5 1886.79    80.7 1886.86      85  1887.4    86.5 1887.75
    93.6 1889.56   102.2 1889.83   119.4 1892.47   134.8 1893.41     144  1893.7
   153.8 1894.39   158.1 1894.37   162.4 1894.09   166.7 1894.17     171 1894.74
   175.3 1895.74   184.2 1899.66   188.1 1901.71   196.5 1907.08     199 1908.84
#Mann= 3 ,-1,0
       0      .1       0    46.3    .045       0    86.5      .1       0
Bank Sta=46.3,86.5
XS Rating Curve= 0 ,0
Exp/Cntr(USF)=0,0
Exp/Cntr=0.3,0.1

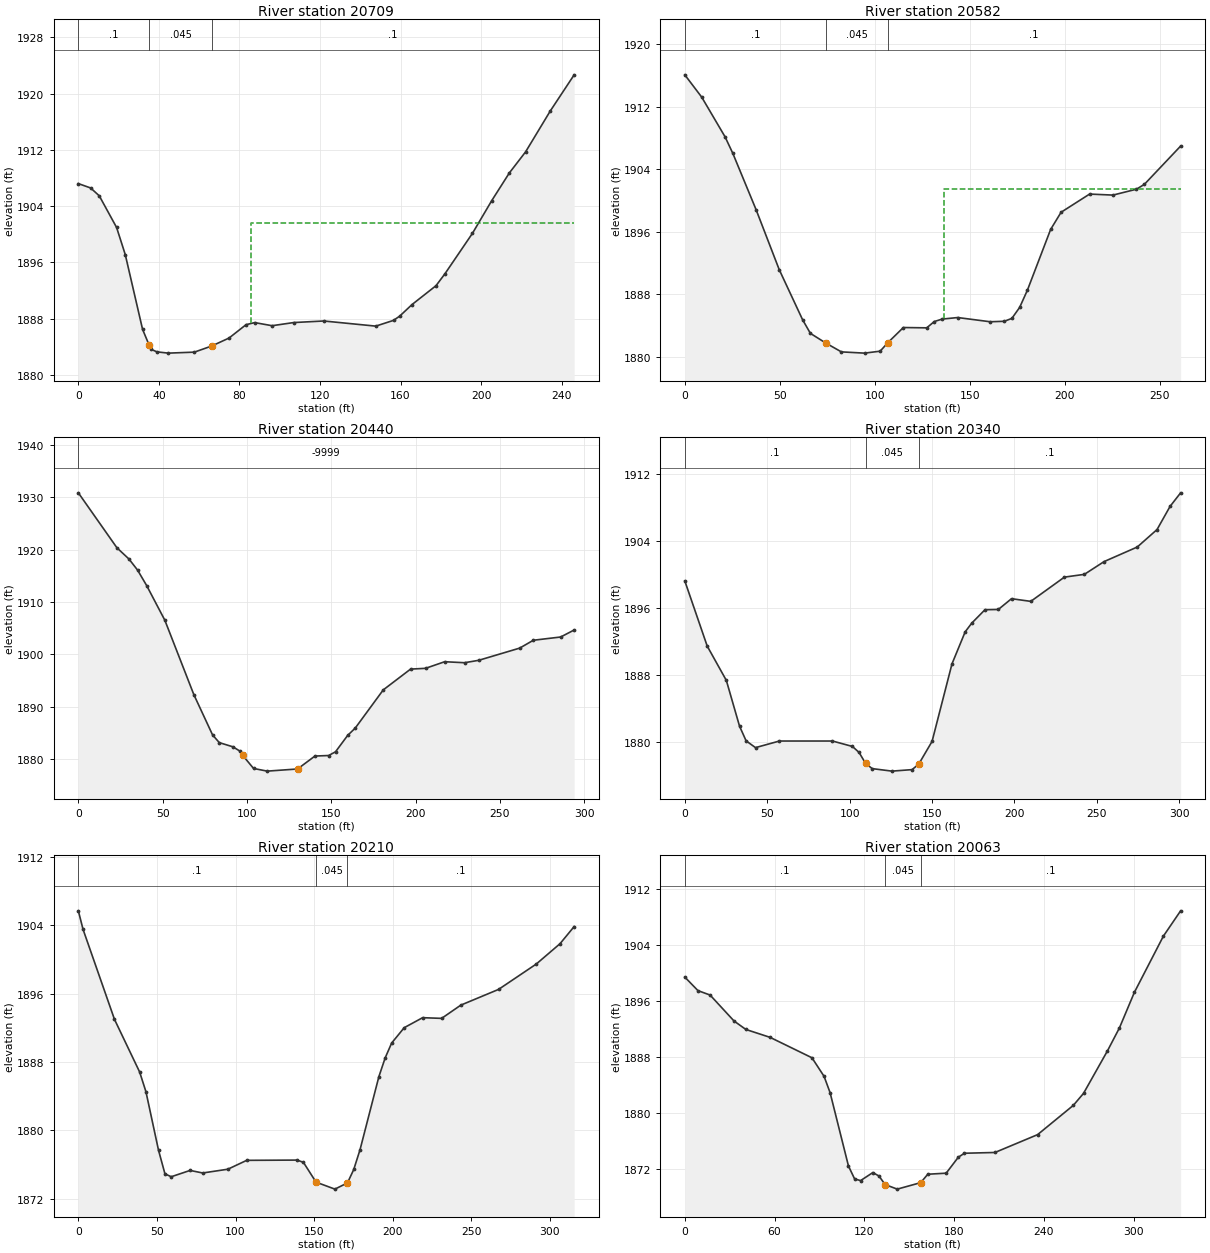
Type RM Length L Ch R = 1 ,20709   ,129.2,126.9,122.1
XS GIS Cut Line= 3
2158598.46702304622756.4667831412158761.95082994622819.781321073
 2158831.8803196622831.121238314
#Sta/Elev= 30
       0 1907.19     6.1 1906.57    10.4 1905.45      19 1900.95    23.3  1897.1
    31.9 1886.46    35.2 1884.19    36.1 1883.63      39 1883.26    44.7 1883.08
    57.6 1883.22    66.2 1884.09    74.8 1885.22    83.3 1887.13    87.6 1887.42
    96.2 1886.98     107 1887.43   121.9 1887.65   147.7 1886.92   156.5 1887.74
   159.6 1888.35   165.7 1889.99   177.6 1892.67     182 1894.35   195.7 1900.12
   205.3 1904.78     214  1908.7   222.1 1911.71   234.3  1917.5   246.2 1922.66
#Mann= 3 ,-1,0
       0      .1       0    35.2    .045       0    66.2      .1       0
#XS Ineff= 2 , 0
                           85.92         1901.61
Permanent Ineff=
       F       F
Bank Sta=35.2,66.2
XS Rating Curve= 0 ,0
Exp/Cntr(USF)=0,0
Exp/Cntr=0.3,0.1

Type RM Length L Ch R = 1 ,20582   ,142.1,141.5,140.2
XS GIS Cut Line= 3
2158543.41641447622880.7240989082158743.04458722622920.908990825
2158798.78492117622933.871859185
#Sta/Elev= 30
       0  1916.1     8.9 1913.24    21.2 1908.15    25.3 1906.02    37.5 1898.83
    49.7 1891.13      62 1884.71    66.1 1882.97    74.2 1881.73    82.4  1880.6
    94.6 1880.44   102.8 1880.69   106.81881.768     115 1883.72   127.3 1883.68
   131.3 1884.49   135.4  1884.8   143.6    1885   160.7 1884.46   168.1 1884.52
   172.1 1884.89   176.2  1886.3   180.3 1888.52   192.5 1896.29     198 1898.49
     213 1900.82   225.3 1900.69   237.6 1901.44   241.8 1902.06   260.9 1906.97
#Mann= 3 ,-1,0
       0      .1       0    74.2    .045       0   106.8      .1       0
#XS Ineff= 2 , 0
                          136.56         1901.51
Permanent Ineff=
       F       F
Bank Sta=74.2,106.8
XS Rating Curve= 0 ,0
Exp/Cntr(USF)=0,0
Exp/Cntr=0.3,0.1

Type RM Length L Ch R = 1 ,20440   ,106.7,100,95.4
XS GIS Cut Line= 3
2158505.50572234623021.6617094562158667.77197197623046.694519316
 2158796.0651225623027.025882998
#Sta/Elev= 30
       0 1930.84    22.9 1920.34      30 1918.21    35.1  1916.1    40.5 1913.14
    51.3 1906.51    68.5  1892.3    79.6 1884.61    83.6 1883.14    91.7 1882.34
    95.8 1881.52    97.41880.728   103.9 1878.21     112  1877.7     130 1878.11
   140.3 1880.58   148.4 1880.68   152.5 1881.39   159.7 1884.52   164.2 1885.92
   180.8 1893.21     197 1897.18   205.9 1897.33   217.2 1898.59     229  1898.4
   237.4 1898.86   261.7 1901.19   269.8 1902.69     286 1903.31     294 1904.65
#Mann= 1 ,-1,0
       0   -9999       0
Bank Sta=97.4,130
XS Rating Curve= 0 ,0
Exp/Cntr(USF)=0,0
Exp/Cntr=0.3,0.1

Type RM Length L Ch R = 1 ,20340   ,128.9,130.2,131
XS GIS Cut Line= 4
2158511.00924357623149.0554739662158540.58514088623148.321674513
2158673.46939882623132.9541072682158810.42154221623120.750450926
#Sta/Elev= 30
       0 1899.25    13.6 1891.45    25.2 1887.35    33.2 1881.88    37.2 1880.12
    42.9 1879.31    57.4  1880.1    89.6  1880.1   101.7 1879.45   105.7 1878.74
   109.7 1877.42   113.7  1876.8   125.7  1876.5   137.9 1876.68   141.9 1877.33
     150 1880.05   162.1 1889.33   170.1 1893.16   174.1  1894.2   182.1  1895.8
   190.2 1895.83   198.2 1897.12   209.9  1896.8   230.3  1899.7   242.4 1900.03
   254.4 1901.56   274.5  1903.3   286.5 1905.39   294.4 1908.16   300.8 1909.78
#Mann= 3 ,-1,0
       0      .1       0   109.7    .045       0   141.9      .1       0
Bank Sta=109.7,141.9
XS Rating Curve= 0 ,0
Exp/Cntr(USF)=0,0
Exp/Cntr=0.3,0.1

Type RM Length L Ch R = 1 ,20210   ,149.6,147.2,144.6
XS GIS Cut Line= 3
2158489.19908309623272.9667752212158710.86413205623261.300193697
2158804.19678424 623257.80021924
#Sta/Elev= 30
       0  1905.7       3 1903.53      23 1892.99      39 1886.83      43 1884.53
      51 1877.68    55.1 1874.91    59.1 1874.57    71.1 1875.31    79.1 1875.01
    95.1 1875.45   107.1 1876.49   139.2 1876.52   143.2 1876.25   151.2 1873.94
   163.2 1873.12   171.2 1873.85   175.2 1875.42   179.2 1877.74   191.2  1886.3
   195.2 1888.49   199.3 1890.22   207.3 1892.02     219 1893.19   231.1 1893.11
   243.3 1894.66   267.3  1896.5   291.3 1899.47   306.4 1901.85   315.4 1903.86
#Mann= 3 ,-1,0
       0      .1       0   151.2    .045       0   171.2      .1       0
Bank Sta=151.2,171.2
XS Rating Curve= 0 ,0
Exp/Cntr(USF)=0,0
Exp/Cntr=0.3,0.1

Type RM Length L Ch R = 1 ,20063   ,163.7,163.6,162.4
XS GIS Cut Line= 4
2158511.36558798623428.1323094942158604.69824018623421.132360579
2158773.86367228623387.2992741592158833.36323805623360.466136653
#Sta/Elev= 30
       0 1899.48     8.8 1897.54    16.9 1896.91    32.9  1893.2    40.8 1891.99
      57 1890.86      85 1887.94    93.1 1885.28    97.1 1882.96   109.4 1872.46
   113.5 1870.62   117.5 1870.38   125.7 1871.53   129.8 1871.03   133.9 1869.81
     142 1869.16   157.7 1870.09   162.4 1871.29   174.7 1871.44   182.8 1873.72
   186.9 1874.29   207.3  1874.4   235.8 1876.95   259.7 1881.14   266.5 1882.85
   282.5 1888.93   290.5 1892.21   300.5  1897.3   319.9 1905.34   331.4 1908.95
#Mann= 3 ,-1,0
       0      .1       0   133.9    .045       0   157.7      .1       0
Bank Sta=133.9,157.7
XS Rating Curve= 0 ,0
Exp/Cntr(USF)=0,0
Exp/Cntr=0.3,0.1

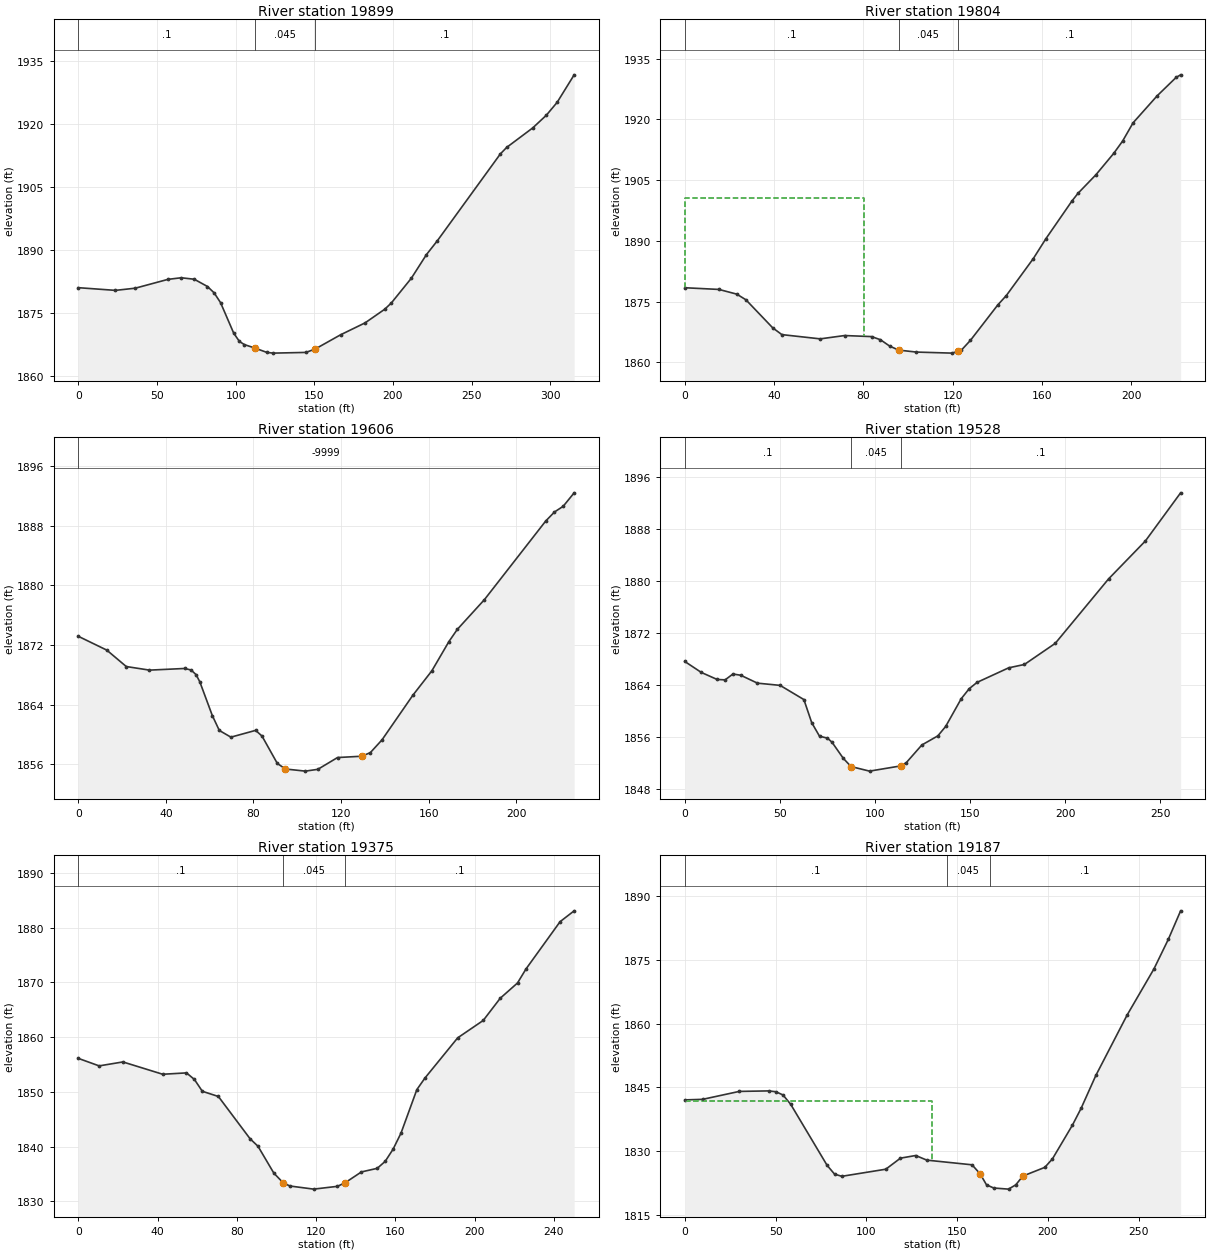
Type RM Length L Ch R = 1 ,19899   ,91,95.1,96.1
XS GIS Cut Line= 3
2158593.53483831  623598.00041982158810.92105183623532.937644627
2158898.94715942623526.814089316
#Sta/Elev= 30
       0  1881.1    23.6 1880.46    36.2 1880.98      57 1883.08    65.4 1883.46
    73.7 1883.11    82.1 1881.38    86.3 1879.88    90.4 1877.55    98.8 1870.26
   102.4 1868.31   105.6 1867.55     112 1866.77   119.7 1865.72   123.8 1865.53
   144.7  1865.7   150.6 1866.51   166.7 1869.89   182.3 1872.73   194.8 1875.98
     199 1877.47   211.7 1883.35   221.3 1888.97   228.2 1892.25   268.3 1912.93
   272.3 1914.47   288.9 1919.12   297.5 1922.12   304.4  1925.2   315.2 1931.74
#Mann= 3 ,-1,0
       0      .1       0     112    .045       0   150.6      .1       0
Bank Sta=112,150.6
XS Rating Curve= 0 ,0
Exp/Cntr(USF)=0,0
Exp/Cntr=0.3,0.1

Type RM Length L Ch R = 1 ,19804   ,180.3,198.6,216.3
XS GIS Cut Line= 3
2158648.98753149623657.0480673362158806.66908074623639.442845818
2158870.20096708623640.973734646
#Sta/Elev= 30
       0 1878.43    15.3 1878.01    23.3 1876.85    27.4 1875.45    39.4 1868.53
    43.5 1866.86    60.7 1865.81    71.6 1866.63    83.7 1866.37    87.7 1865.59
    91.8 1864.03    95.8 1863.04   103.8 1862.55   119.9 1862.29   122.51862.778
     124 1863.06     128 1865.44   140.3 1874.21   144.1 1876.51   156.2 1885.64
   161.8 1890.51   173.5 1899.84   176.2 1901.73   184.2 1906.29   192.2 1911.58
   196.2 1914.63   200.9 1919.14   211.7 1925.81   220.2 1930.35   222.2 1930.98
#Mann= 3 ,-1,0
       0      .1       0    95.8    .045       0   122.5      .1       0
#XS Ineff= 2 , 0
           80.28  1900.7
Permanent Ineff=
       F       F
Bank Sta=95.8,122.5
XS Rating Curve= 0 ,0
Exp/Cntr(USF)=0,0
Exp/Cntr=0.3,0.1

Type RM Length L Ch R = 1 ,19606   ,84,77.6,67.1
XS GIS Cut Line= 3
2158611.65504964 623739.358270192158724.70500702623837.924959013
2158801.14447999623834.304141873
#Sta/Elev= 30
       0 1873.17      13 1871.32    21.9 1869.12    32.5 1868.64    48.5 1868.86
    51.5 1868.66    53.8 1868.03    55.5 1867.07    61.2 1862.56    64.4 1860.56
    69.7 1859.66      81 1860.57    83.9 1859.81    90.9 1856.14    94.61855.395
   103.7 1855.11   109.4 1855.35   118.4 1856.93   129.51857.106   133.4 1857.59
   138.7 1859.29   152.8 1865.27   161.5 1868.55   169.3 1872.47   173.1 1874.09
   185.5 1878.08   213.5 1888.61   217.5 1889.82   221.5 1890.59   226.5 1892.39
#Mann= 1 ,-1,0
       0   -9999       0
Bank Sta=94.6,129.5
XS Rating Curve= 0 ,0
Exp/Cntr(USF)=0,0
Exp/Cntr=0.3,0.1

Type RM Length L Ch R = 1 ,19528   ,156.8,153,144
XS GIS Cut Line= 3
2158555.72247778623846.8680169682158735.38783325623894.701001218
2158810.05395501623893.534343065
#Sta/Elev= 30
       0  1867.6     8.7 1865.91      17 1864.83    21.2 1864.77    25.3 1865.67
    29.4 1865.48    38.2 1864.26    50.1 1863.92    62.6 1861.73    66.7 1858.18
    70.8 1856.09      75 1855.79    77.4 1855.15    83.3 1852.68    87.4 1851.41
    97.1 1850.71   113.4 1851.51   116.4 1852.01   124.6 1854.74     133 1856.14
   137.1 1857.59   145.3 1861.87   149.5 1863.41   153.6 1864.38   170.2 1866.62
   178.5 1867.14   194.7 1870.39   222.7 1880.31   242.1 1886.17   260.6 1893.58
#Mann= 3 ,-1,0
       0      .1       0    87.4    .045       0   113.4      .1       0
Bank Sta=87.4,113.4
XS Rating Curve= 0 ,0
Exp/Cntr(USF)=0,0
Exp/Cntr=0.3,0.1

Type RM Length L Ch R = 1 ,19375   ,178.9,188.4,172.5
XS GIS Cut Line= 3
2158541.72257995624031.2000050522158726.05456803624017.200107222
2158786.72079196623992.700286021
#Sta/Elev= 30
       0 1856.13    10.5 1854.76    22.5 1855.48    42.6 1853.23    54.6 1853.48
    58.6 1852.28    62.6 1850.12    70.7 1849.17    86.7 1841.45    90.7 1840.08
    98.7 1835.17   103.41833.409   106.8 1832.82   118.8 1832.25   130.8 1832.76
   134.7 1833.42   142.9 1835.39   150.9 1836.05   154.9 1837.32   158.9 1839.55
   162.9 1842.49   170.9 1850.43     175 1852.55   191.5 1859.88   204.4 1863.06
     213 1867.12   221.7  1869.9     226 1872.47   243.2  1881.1   250.3 1883.08
#Mann= 3 ,-1,0
       0      .1       0   103.4    .045       0   134.7      .1       0
Bank Sta=103.4,134.7
XS Rating Curve= 0 ,0
Exp/Cntr(USF)=0,0
Exp/Cntr=0.3,0.1

Type RM Length L Ch R = 1 ,19187   ,115.9,115.4,116.4
XS GIS Cut Line= 4
2158582.44361839624152.2908962642158705.89788024624135.533648967
2158728.38315468 624148.242717132158850.79661545 624140.60990007
#Sta/Elev= 30
       0 1842.05     9.8 1842.18      30 1844.05    46.2 1844.17    50.2 1843.97
    54.1 1843.21    58.3 1841.03    78.4 1826.62    82.5 1824.56    86.5 1824.05
   110.7 1825.72   118.8 1828.33   127.2 1828.95   133.3 1827.86   158.2 1826.76
   162.61824.671   166.2 1822.03   170.2 1821.29   178.3 1821.03   182.3 1822.04
   186.21824.106   198.3 1826.16   202.5 1828.16   213.5  1836.1   218.3 1840.08
   226.4 1847.81   243.6 1862.02   258.4  1872.9   266.3 1879.85   273.1 1886.59
#Mann= 3 ,-1,0
       0      .1       0   144.4    .045       0   167.9      .1       0
#XS Ineff= 2 , 0
          136.06 1841.88
Permanent Ineff=
       F       F
Bank Sta=162.6,186.2
XS Rating Curve= 0 ,0
Exp/Cntr(USF)=0,0
Exp/Cntr=0.3,0.1

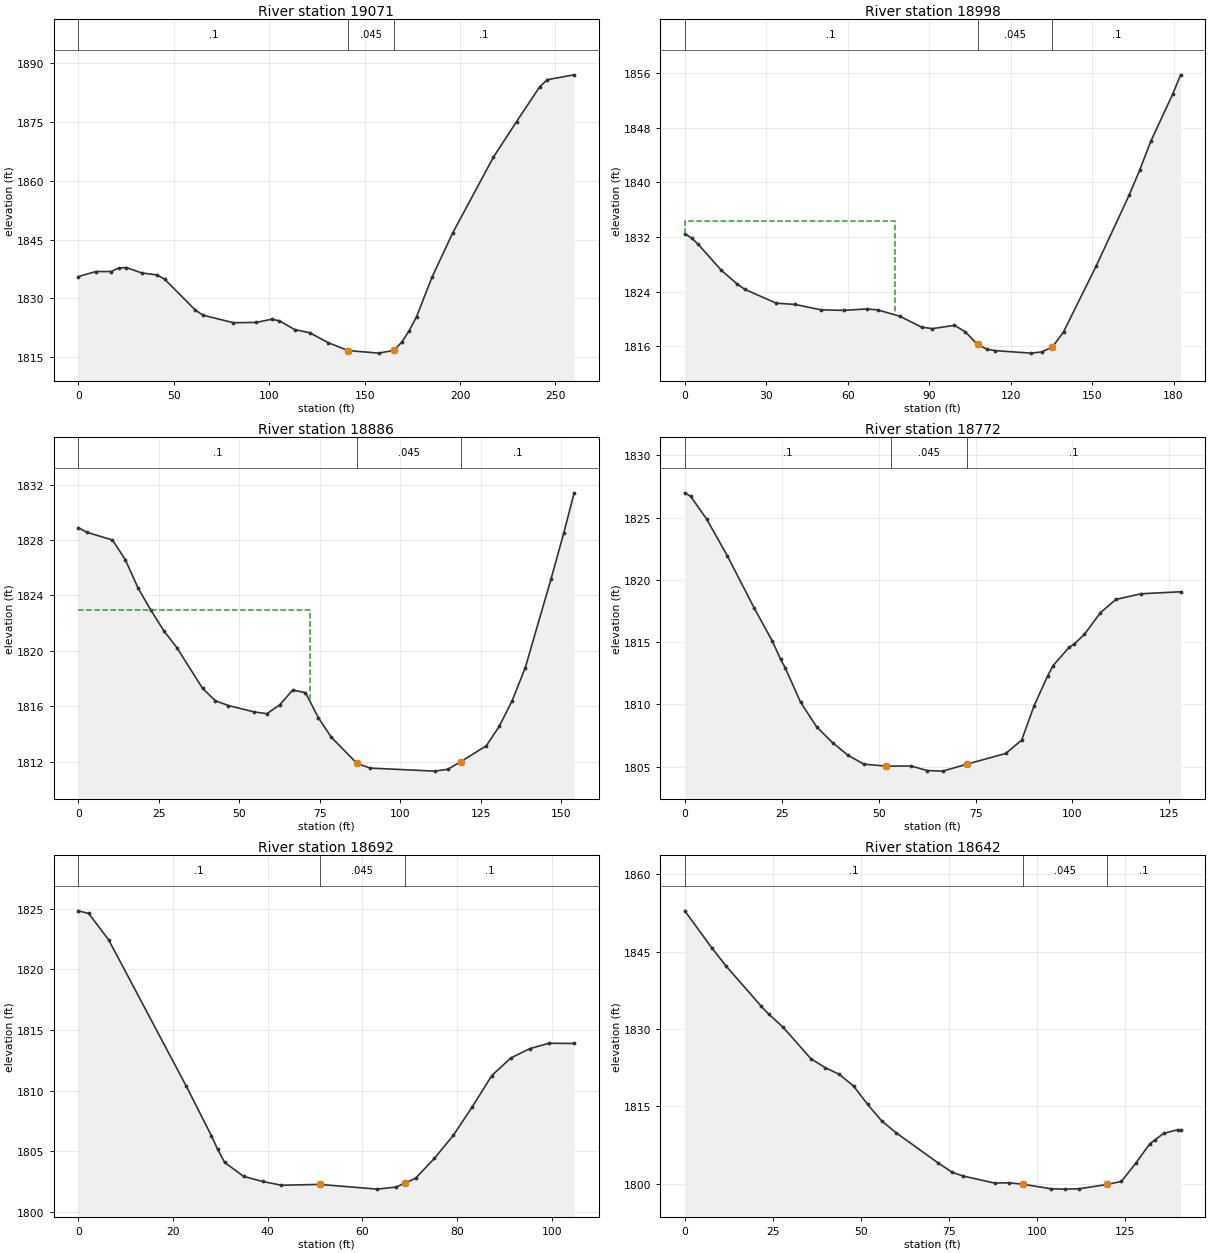
Type RM Length L Ch R = 1 ,19071   ,70.2,73.7,75.9
XS GIS Cut Line= 3
2158623.01924987624266.8125360632158831.72143047624255.145954539
2158882.27661707624249.960807195
#Sta/Elev= 30
       0 1835.55     9.2 1836.84    17.2 1836.84    21.2 1837.73    25.2 1837.85
    33.2 1836.48    41.2 1835.97    45.2  1834.9    61.3 1827.01    65.3  1825.7
    81.3 1823.77    93.3 1823.85   101.3 1824.66   105.3 1824.27   113.3 1822.04
   121.3  1821.2     131 1818.66   141.4 1816.66   157.4 1816.01   165.4 1816.72
   169.6 1818.88   173.4 1821.78   177.2  1825.3   185.4 1835.48   196.1 1846.63
   217.5 1866.04   229.6  1875.1   241.7 1883.96   245.7 1885.81   259.8 1887.05
#Mann= 3 ,-1,0
       0      .1       0   141.4    .045       0   165.4      .1       0
Bank Sta=141.4,165.4
XS Rating Curve= 0 ,0
Exp/Cntr(USF)=0,0
Exp/Cntr=0.3,0.1

Type RM Length L Ch R = 1 ,18998   ,110.1,111.1,108.9
XS GIS Cut Line= 4
2158662.08416558624292.6484536362158704.24484389624319.928892544
2158720.36510325 624325.508982322158835.06694866624337.289171849
#Sta/Elev= 30
       0 1832.48     2.5 1831.85     4.8 1830.98    13.5  1827.1    19.3  1825.1
    22.1 1824.32    33.7 1822.29    40.6 1822.11    50.1 1821.32    58.6 1821.24
    67.1 1821.45    71.1  1821.3    79.1 1820.39    87.2 1818.78    91.2 1818.56
    99.3 1819.05   103.3 1818.09   107.8 1816.24   111.3 1815.54   114.2 1815.34
   127.4 1814.97   131.4 1815.14   135.4 1815.87   139.5 1818.09   151.5 1827.74
   163.6  1838.1   167.6 1841.87   171.6 1846.02   179.7 1852.95   182.6 1855.77
#Mann= 3 ,-1,0
       0      .1       0   107.8    .045       0   135.4      .1       0
#XS Ineff= 2 , 0
           77.41 1834.37
Permanent Ineff=
       F       F
Bank Sta=107.8,135.4
XS Rating Curve= 0 ,0
Exp/Cntr(USF)=0,0
Exp/Cntr=0.3,0.1

Type RM Length L Ch R = 1 ,18886   ,110.2,114.2,116.4
XS GIS Cut Line= 3
 2158641.6238364624431.5306880772158708.58491372624431.530688077
2158795.38631025624439.590817754
#Sta/Elev= 30
       0 1828.89     2.6 1828.56    10.6    1828    14.6 1826.58    18.6 1824.52
    22.6 1822.92    26.6 1821.45    30.6 1820.25    38.6 1817.31    42.6 1816.41
    46.6 1816.07    54.6 1815.61    58.6 1815.48    62.6 1816.12    66.6 1817.18
    70.6    1817    74.6 1815.19    78.6 1813.79    86.6  1811.9    90.7 1811.56
   110.7 1811.34   114.8 1811.47   118.8 1812.01   126.8 1813.17   130.8 1814.56
   134.8  1816.4   138.9 1818.79   146.9 1825.18   150.9 1828.53   154.1  1831.4
#Mann= 3 ,-1,0
       0      .1       0    86.6    .045       0   118.8      .1       0
#XS Ineff= 2 , 0
           71.93 1822.94
Permanent Ineff=
       F       F
Bank Sta=86.6,118.8
XS Rating Curve= 0 ,0
Exp/Cntr(USF)=0,0
Exp/Cntr=0.3,0.1

Type RM Length L Ch R = 1 ,18772   ,75.8,80,74.2
XS GIS Cut Line= 2
2158646.70307013624525.9091344242158772.59580121624548.667883445
#Sta/Elev= 30
       0 1826.98     1.5  1826.7     5.6 1824.89      11 1821.91    17.9 1817.74
    22.6 1815.07    24.7 1813.63    25.9 1812.94    29.9 1810.16      34 1808.21
    38.1 1806.94    42.1 1805.92    46.2 1805.21    51.91805.052    58.4 1805.06
    62.5  1804.7    66.5 1804.65    72.9 1805.22    82.8 1806.07    86.9 1807.14
    90.1 1809.89    93.6 1812.29      95 1813.12    99.1 1814.57   100.5 1814.86
   103.1 1815.63   107.2 1817.36   111.2 1818.43   117.7 1818.88   127.9 1819.04
#Mann= 3 ,-1,0
       0      .1       0    53.2    .045       0    72.8      .1       0
Bank Sta=51.9,72.9
XS Rating Curve= 0 ,0
Exp/Cntr(USF)=0,0
Exp/Cntr=0.3,0.1

Type RM Length L Ch R = 1 ,18692   ,51.4,50,48
XS GIS Cut Line= 3
2158642.00394759 624596.538314312158662.09227079624601.560395109
2158745.45881205624611.604556707
#Sta/Elev= 23
       0 1824.82     2.2  1824.6     6.4 1822.43    22.8 1810.37    28.1 1806.29
    29.4 1805.18    30.9 1804.09    34.9 1802.94    38.9 1802.52    42.9 1802.21
      51 1802.28    63.1 1801.89    67.1 1802.06    68.91802.376    71.2 1802.78
    75.2 1804.43    79.2 1806.33    83.2 1808.68    87.3 1811.24    91.3 1812.69
    95.3 1813.46    99.4 1813.91   104.7 1813.89
#Mann= 3 ,-1,0
       0      .1       0      51    .045       0    68.9      .1       0
Bank Sta=51,68.9
XS Rating Curve= 0 ,0
Exp/Cntr(USF)=0,0
Exp/Cntr=0.3,0.1

Type RM Length L Ch R = 1 ,18642   ,93.2,86.2,74.2
XS GIS Cut Line= 3
2158584.44775963624649.6373700332158633.26238499624653.253268208
2158725.01580119 624655.96519184
#Sta/Elev= 30
       0 1852.92     7.7  1845.7    11.8 1842.15    21.7 1834.41    23.8  1832.9
    27.8 1830.42    35.8 1824.23    39.8 1822.53    43.8 1821.23    47.9 1818.94
    51.9 1815.38    55.9 1812.17    59.9 1809.92    71.9 1804.03    75.9 1802.22
    78.9 1801.51    87.9 1800.14    91.9 1800.18    95.9 1799.92   103.9 1799.03
   107.9 1798.96   111.9 1799.03   119.9 1799.87   123.9 1800.46   127.9 1803.93
   131.9 1807.69   133.3 1808.45   135.9 1809.77   139.9 1810.48   140.7 1810.46
#Mann= 3 ,-1,0
       0      .1       0    95.9    .045       0   119.9      .1       0
Bank Sta=95.9,119.9
XS Rating Curve= 0 ,0
Exp/Cntr(USF)=0,0
Exp/Cntr=0.3,0.1

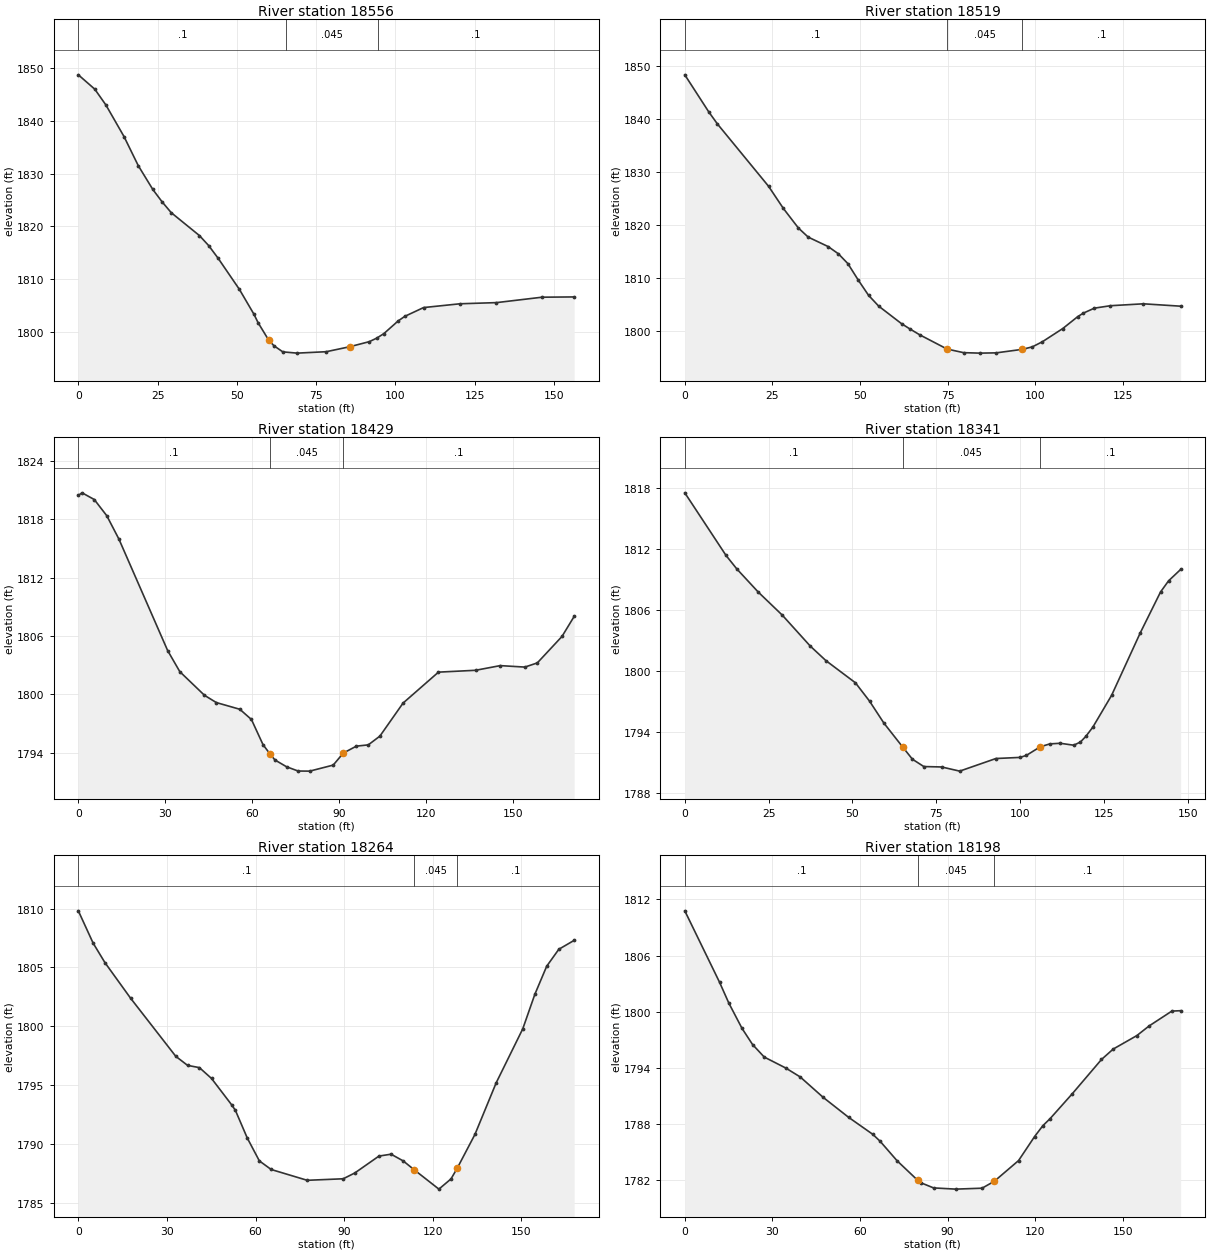
Type RM Length L Ch R = 1 ,18556   ,45.7,37.3,28.1
XS GIS Cut Line= 3
2158631.57873692624772.3544961412158727.14985412624720.185922098
2158753.87555804624680.845685934
#Sta/Elev= 30
       0 1848.78     5.2 1846.05     8.7 1843.05    14.4 1837.07    18.9 1831.54
    23.5 1827.01    26.4 1824.68    29.3 1822.61    38.2 1818.26    41.1 1816.37
    44.1 1813.95    50.8 1808.05    55.4 1803.32    56.7 1801.72      601798.454
    61.7 1797.34    64.5 1796.18      69 1795.94    78.2 1796.21    85.61797.154
    91.8 1798.12    94.2 1798.81    96.4 1799.66   100.9 1802.06     103 1802.93
   108.9 1804.59   120.4 1805.31   131.9 1805.53   146.3 1806.56   156.4 1806.61
#Mann= 3 ,-1,0
       0      .1       0    65.6    .045       0    94.4      .1       0
Bank Sta=60,85.6
XS Rating Curve= 0 ,0
Exp/Cntr(USF)=0,0
Exp/Cntr=0.3,0.1

Type RM Length L Ch R = 1 ,18519   ,96.5,89.7,82.6
XS GIS Cut Line= 3
2158664.50385958624827.1248253262158700.30125152624797.429261561
2158749.11587689624716.071552617
#Sta/Elev= 30
       0 1848.38     6.8 1841.41     9.3  1839.1    23.9 1827.31    28.1 1823.14
    32.4 1819.43    35.2 1817.71    40.9 1815.92    43.8 1814.56    46.5 1812.71
    49.5 1809.56    52.4 1806.72    55.3 1804.67    61.8 1801.36    64.1  1800.4
      67 1799.25    74.8 1796.56    79.5 1795.88    84.1 1795.79    88.8 1795.84
    96.2  1796.5    99.1 1796.97     102 1797.95   107.8 1800.44   112.1 1802.71
   113.7 1803.36   116.8 1804.29   121.4 1804.75   130.8 1805.11   141.4 1804.66
#Mann= 3 ,-1,0
       0      .1       0    74.8    .045       0    96.2      .1       0
Bank Sta=74.8,96.2
XS Rating Curve= 0 ,0
Exp/Cntr(USF)=0,0
Exp/Cntr=0.3,0.1

Type RM Length L Ch R = 1 ,18429   ,62.9,87.8,96.1
XS GIS Cut Line= 4
2158788.98115427624858.4475432692158803.62554188624814.107591895
2158812.16810132624738.4449225772158828.84643165624693.291394113
#Sta/Elev= 30
       0 1820.45     1.3 1820.71     5.5 1820.02     9.8 1818.36      14 1815.95
    30.8 1804.49      35 1802.32    43.5 1799.89    47.6 1799.14    55.7 1798.45
    59.7  1797.4    63.7 1794.81    66.1 1793.86    67.8 1793.24    71.8 1792.54
    75.8  1792.1    79.8 1792.09    87.9 1792.71    91.4 1793.95    95.9 1794.66
     100 1794.79     104 1795.69     112 1799.09   124.2 1802.27     137 1802.46
   145.5 1802.94     154 1802.79   158.3 1803.22   166.8 1805.94     171    1808
#Mann= 3 ,-1,0
       0      .1       0    66.1    .045       0    91.4      .1       0
Bank Sta=66.1,91.4
XS Rating Curve= 0 ,0
Exp/Cntr(USF)=0,0
Exp/Cntr=0.3,0.1

Type RM Length L Ch R = 1 ,18341   ,75,77.5,83.3
XS GIS Cut Line= 3
2158800.29911468 624852.559796162158848.65989274624838.299566731
2158921.20105984624773.198519337
#Sta/Elev= 30
       0 1817.54    12.3 1811.38    15.5 1810.06    21.9 1807.78    29.1  1805.5
    37.4 1802.47    42.1 1801.03    50.9 1798.85    55.1 1797.05    59.4 1794.88
      65 1792.53    67.9 1791.33    71.3 1790.61    76.6 1790.57      82 1790.16
    92.8  1791.4     100 1791.51   101.9 1791.71     106 1792.55   108.9 1792.84
     112  1792.9     116 1792.71     118 1793.02   119.6 1793.57   121.7 1794.48
   127.3 1797.61   135.9 1803.79   141.9 1807.78   144.3 1808.88   147.9    1810
#Mann= 3 ,-1,0
       0      .1       0      65    .045       0     106      .1       0
Bank Sta=65,106
XS Rating Curve= 0 ,0
Exp/Cntr(USF)=0,0
Exp/Cntr=0.3,0.1

Type RM Length L Ch R = 1 ,18264   ,62.6,65.9,70.7
XS GIS Cut Line= 4
2158815.17935408624869.9200754662158855.48000247624869.920075466
2158951.58154862624853.7998161112158981.34202743624848.839736309
#Sta/Elev= 30
       0 1809.81       5 1807.07       9 1805.41    17.7 1802.38      33 1797.44
      37 1796.67      41 1796.48    45.1 1795.56      52 1793.29    53.2 1792.84
    57.2  1790.5    61.3 1788.55    65.3 1787.82    77.5  1786.9    89.7 1787.03
    93.6 1787.52   101.8 1788.96   105.9 1789.12     110 1788.55   113.81787.782
   122.1 1786.15   126.2 1787.02   128.31787.927   134.3  1790.8   141.5 1795.19
   150.5 1799.78   154.6 1802.72   158.6  1805.1   162.7 1806.54   167.9  1807.3
#Mann= 3 ,-1,0
       0      .1       0   113.8    .045       0   128.3      .1       0
Bank Sta=113.8,128.3
XS Rating Curve= 0 ,0
Exp/Cntr(USF)=0,0
Exp/Cntr=0.3,0.1

Type RM Length L Ch R = 1 ,18198   ,98.2,92.4,86.8
XS GIS Cut Line= 4
2158817.03938401624895.9604944232158848.65989274624897.200514374
2158938.56133915624922.6209233562158983.20205736624925.720973232
#Sta/Elev= 30
       0 1810.78    11.9 1803.15    15.1 1800.91    19.6 1798.22    23.2  1796.5
    27.2 1795.16    34.5    1794    39.5 1793.04    47.4 1790.85    56.1 1788.72
    64.4  1786.9    66.9 1786.16    72.7 1784.08    79.8 1781.98      81 1781.71
    85.2 1781.18    92.8 1781.05   101.8 1781.15     106 1781.89   114.3  1784.1
   119.8 1786.67   122.6 1787.82   125.1 1788.58   132.7 1791.24   142.7  1794.9
   146.7 1796.01   154.8 1797.45     159 1798.48   166.8 1800.07   169.8 1800.11
#Mann= 3 ,-1,0
       0      .1       0    79.8    .045       0     106      .1       0
Bank Sta=79.8,106
XS Rating Curve= 0 ,0
Exp/Cntr(USF)=0,0
Exp/Cntr=0.3,0.1

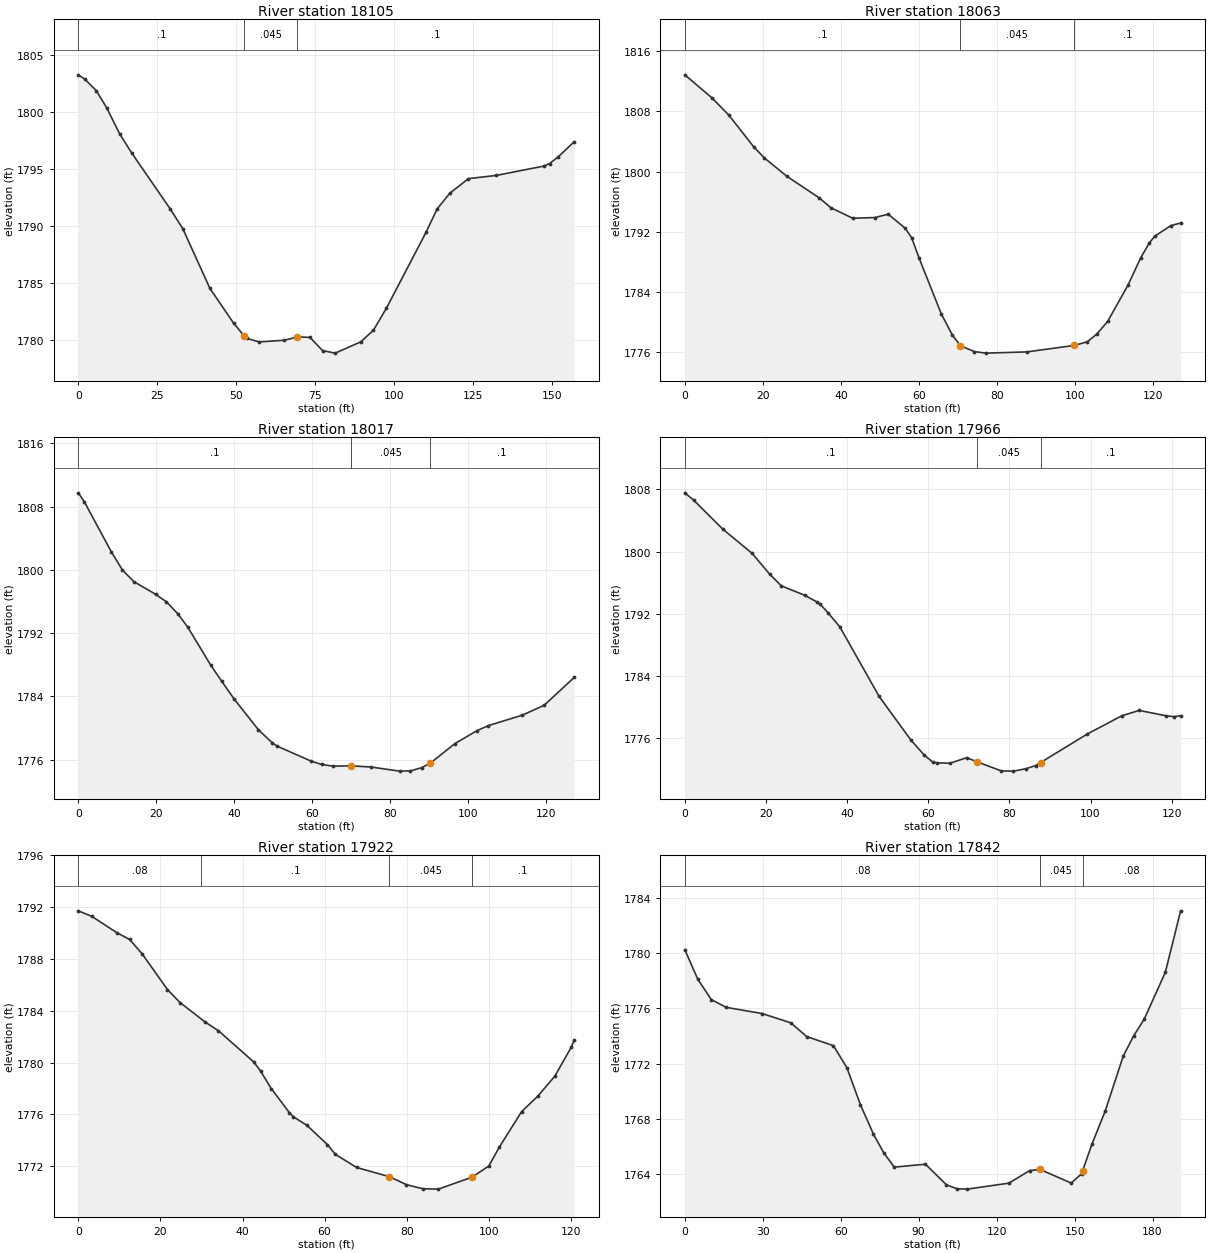
Type RM Length L Ch R = 1 ,18105   ,77.9,42.8,57.9
XS GIS Cut Line= 3
2158835.28540745625010.6136107382158954.14131969624996.663386296
2158983.71579551624973.785018212
#Sta/Elev= 30
       0 1803.22     2.1 1802.83     5.7 1801.83       9 1800.32    13.1 1798.04
      17 1796.33    29.1 1791.47    33.1 1789.73    41.7 1784.49    49.2 1781.45
    52.6 1780.31    53.3 1780.12    57.3  1779.8    65.3 1779.95    69.4 1780.24
    73.4  1780.2    77.4 1779.04    81.4 1778.82    89.5 1779.81    93.5 1780.83
    97.6 1782.75   110.2 1789.43   113.7 1791.47   117.7 1792.84   123.6 1794.12
   132.4  1794.4   147.5 1795.22   149.3 1795.44   152.1 1796.04   157.1 1797.35
#Mann= 3 ,-1,0
       0      .1       0    52.6    .045       0    69.4      .1       0
Bank Sta=52.6,69.4
XS Rating Curve= 0 ,0
Exp/Cntr(USF)=0,0
Exp/Cntr=0.3,0.1

Type RM Length L Ch R = 1 ,18063   ,42.4,45.5,49.3
XS GIS Cut Line= 4
2158884.39019749625098.2210202312158922.89281694625057.486364862
2158959.72140947625012.8456466492158968.64955311625003.359494028
#Sta/Elev= 30
       0 1812.87     6.9 1809.83    11.3  1807.5    17.6 1803.32    20.4  1801.8
    26.1 1799.39    34.5 1796.47    37.4 1795.19      43 1793.79    48.7 1793.88
    52.1 1794.33    56.4 1792.48    58.1  1791.2      60  1788.5    65.7 1781.06
    68.5 1778.28    70.6 1776.82    74.2 1776.04    77.1 1775.84    87.6    1776
    99.8 1776.87   103.1 1777.35   105.5 1778.36   108.3 1780.05   113.5 1784.87
   116.8 1788.54     119 1790.52   120.4 1791.41   124.5 1792.81     127 1793.15
#Mann= 3 ,-1,0
       0      .1       0    70.6    .045       0    99.8      .1       0
Bank Sta=70.6,99.8
XS Rating Curve= 0 ,0
Exp/Cntr(USF)=0,0
Exp/Cntr=0.3,0.1

Type RM Length L Ch R = 1 ,18017   ,57.6,50.6,42.9
XS GIS Cut Line= 4
2158915.08069126625116.0773075172158946.32919401625087.618849656
2158992.08593017625051.9062750852159014.40628928625036.840032688
#Sta/Elev= 30
       0 1809.74     1.5 1808.64     8.5 1802.24    11.3 1799.99    14.2 1798.52
    19.8 1796.91    22.6 1795.95    25.5 1794.45    28.1 1792.73      34 1787.91
    36.8 1785.89    39.9  1783.7    46.2 1779.76    49.7 1778.13      51 1777.69
    59.8 1775.78    62.4 1775.38    65.3 1775.16      70  1775.2    75.1 1775.05
    82.4 1774.53    85.2 1774.56    88.1 1774.97    90.3 1775.54    96.6 1778.01
   102.3 1779.66   105.2 1780.29   113.9 1781.61   119.5 1782.86   127.2 1786.38
#Mann= 3 ,-1,0
       0      .1       0      70    .045       0    90.3      .1       0
Bank Sta=70,90.3
XS Rating Curve= 0 ,0
Exp/Cntr(USF)=0,0
Exp/Cntr=0.3,0.1

Type RM Length L Ch R = 1 ,17966   ,46.9,44.1,41.6
XS GIS Cut Line= 4
2158966.97552618625172.9942232392158995.99199302625129.469522981
2159011.05823542625085.9448227232159019.42837008625063.624463616
#Sta/Elev= 30
       0 1807.55     2.2  1806.6     9.4 1802.87    16.6 1799.77    20.9 1797.11
    23.8  1795.6    29.6 1794.38    32.5 1793.55    33.4 1793.22    35.3 1792.14
    38.2 1790.34    47.9 1781.39    55.8 1775.74      59 1773.88    61.1 1772.96
    62.1 1772.87    65.3 1772.81    69.5 1773.53    71.9 1773.02      78 1771.83
      81  1771.8    84.1 1772.11    86.5 1772.52    87.71772.907    99.2 1776.57
   107.7 1778.91     112  1779.6   118.5 1778.92   120.5  1778.8   122.2 1778.91
#Mann= 3 ,-1,0
       0      .1       0    71.9    .045       0    87.7      .1       0
Bank Sta=71.9,87.7
XS Rating Curve= 0 ,0
Exp/Cntr(USF)=0,0
Exp/Cntr=0.3,0.1

Type RM Length L Ch R = 1 ,17922   ,81.7,80.4,77.8
XS GIS Cut Line= 3
2159023.46054499625184.7631045172159044.61354932625132.694170793
2159051.52895458625068.421580727
#Sta/Elev= 30
       0 1791.71     3.3 1791.28     9.4 1790.02    12.5  1789.5    15.6 1788.37
    21.7 1785.64    24.8 1784.63    30.9 1783.13    34.1 1782.47    42.7 1780.06
    44.4 1779.35      47    1778    51.4 1776.15    52.4 1775.82    55.7 1775.16
    60.7 1773.67    62.6 1772.93    67.8 1771.91    75.8  1771.2    79.9 1770.59
    83.9 1770.27    87.7 1770.24    95.9 1771.16     100 1772.02   102.6  1773.5
     108 1776.22     112 1777.43   116.1 1778.96   120.1 1781.19   120.8 1781.73
#Mann= 4 ,-1,0
       0     .08       0      30      .1       0    75.8    .045       0
    95.9      .1       0
Bank Sta=75.8,95.9
XS Rating Curve= 0 ,0
Exp/Cntr(USF)=0,0
Exp/Cntr=0.3,0.1

Type RM Length L Ch R = 1 ,17842   ,123.3,135.1,140.2
XS GIS Cut Line= 4
2159081.96444985625240.9846592092159128.22607031625185.826573276
2159125.06481805625090.2696591852159128.46679322 625067.30632677
#Sta/Elev= 30
       0 1780.24       5  1778.1    10.2 1776.63    15.9 1776.07    29.8 1775.62
    40.8 1774.95    46.9 1773.96    57.2  1773.3    62.4  1771.7    67.6 1769.03
    72.6 1766.91    76.6 1765.55    80.6 1764.53    92.6 1764.74   100.7 1763.25
   104.7 1762.97   108.7 1762.94   124.7 1763.37   132.7 1764.28   136.7 1764.36
   148.7 1763.38   152.7 1764.05   153.11764.281   156.7  1766.2   161.8 1768.59
   168.7 1772.54   172.7    1774   176.8 1775.22   184.9 1778.59   190.8 1783.04
#Mann= 3 ,-1,0
       0     .08       0   136.7    .045       0   153.1     .08       0
Bank Sta=136.7,153.1
XS Rating Curve= 0 ,0
Exp/Cntr(USF)=0,0
Exp/Cntr=0.3,0.1