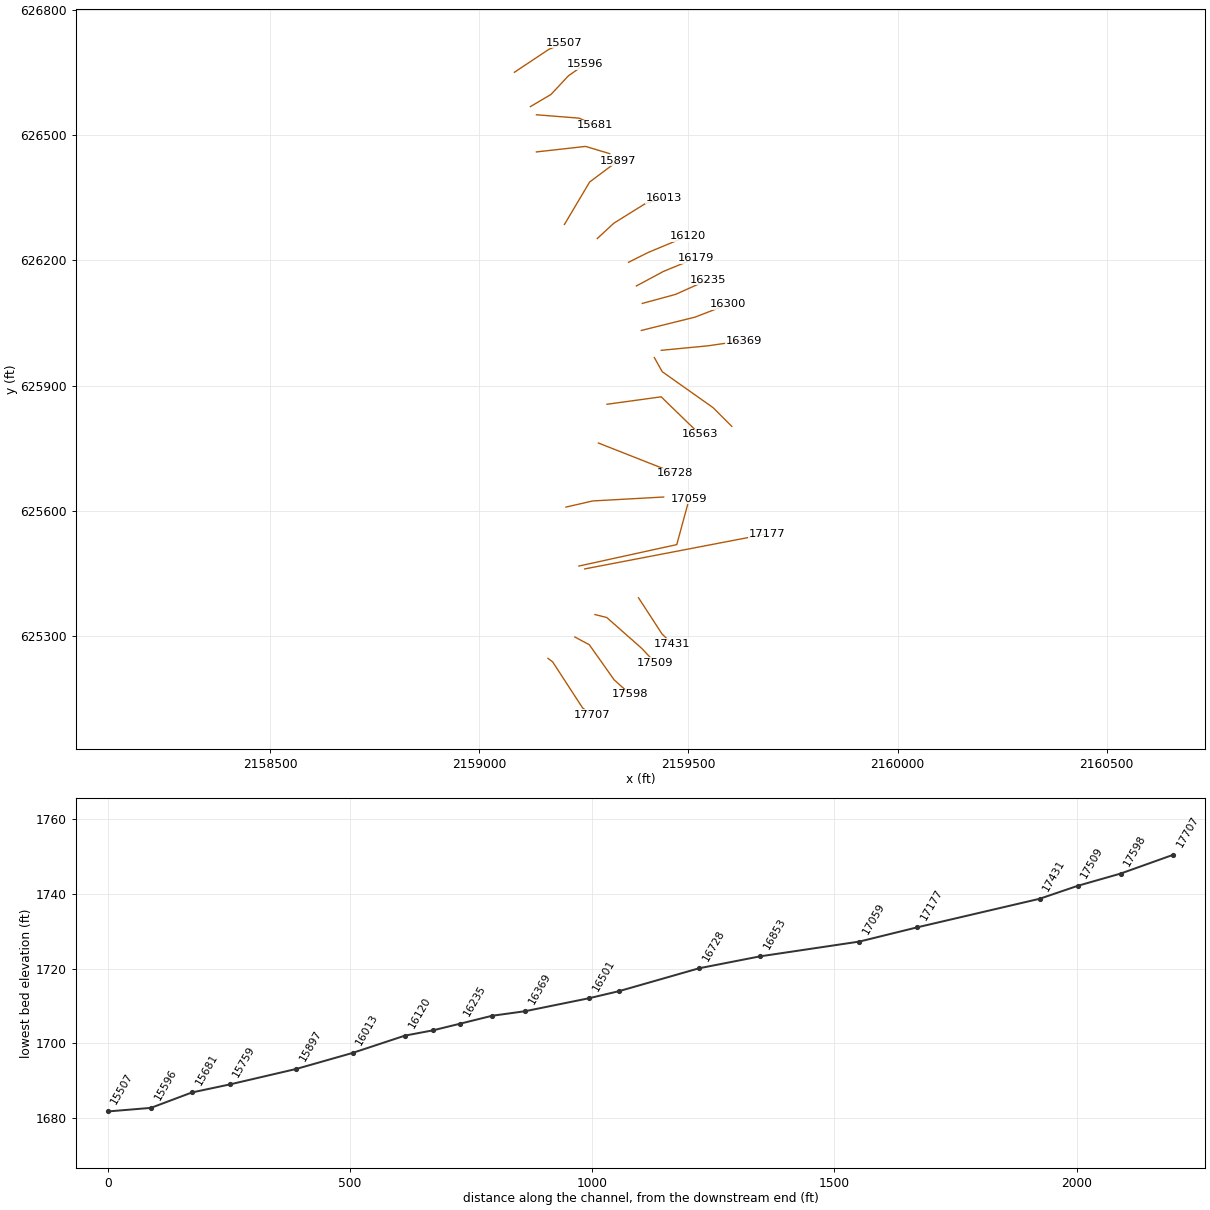
HEC-RAS study LFRFLIKANA.prj: LFRFLIKANA

--- LFRFLIKANA.g01 (geometry) --- (continued)

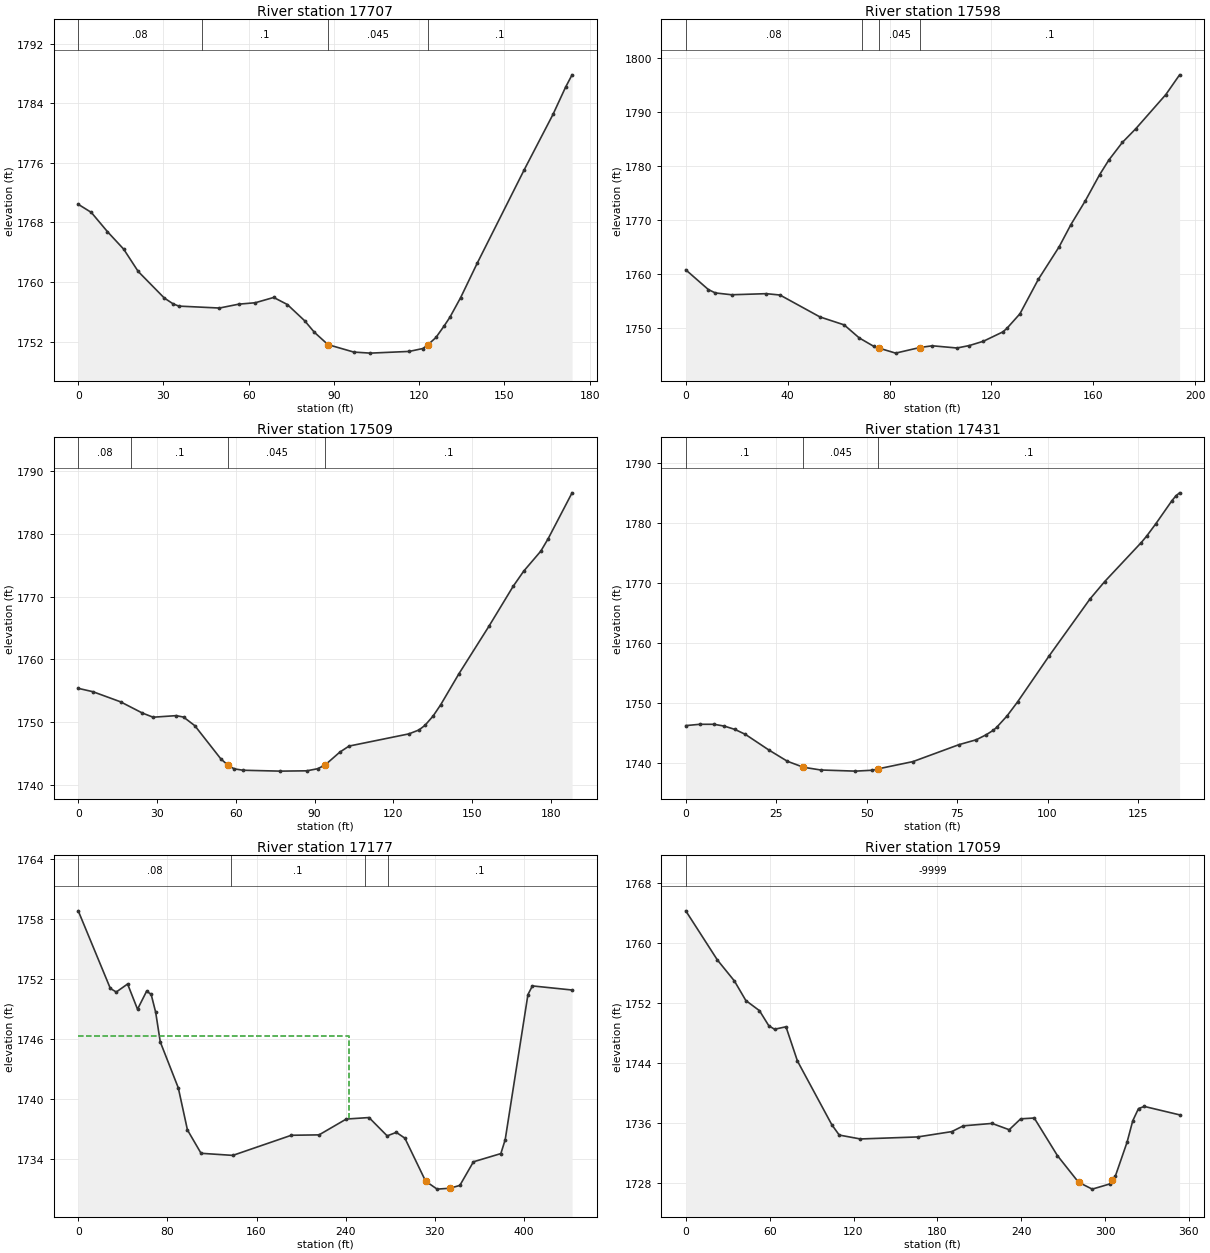
Type RM Length L Ch R = 1 ,17707   ,102,109.2,111.5
XS GIS Cut Line= 4
 2159164.0612918625247.4411545792159175.10986956625239.405825301
2159246.92562498625128.9200477232159269.52498858625111.844973007
#Sta/Elev= 30
       0 1770.44     4.6 1769.35    10.3 1766.76      16 1764.42    21.1 1761.43
    30.3 1757.86    33.4 1757.08    35.4 1756.78    49.7 1756.52    56.5 1757.04
    62.3 1757.23    68.8 1757.94    73.6 1756.99    79.7 1754.81    83.1 1753.27
    87.9 1751.61      97 1750.61   102.8 1750.47   116.5  1750.7   121.3 1751.09
     123 1751.57   125.9 1752.57   128.8 1754.13   130.8 1755.28   134.6 1757.93
   140.4 1762.52     157  1775.1   167.1 1782.51   171.5 1786.14   173.8 1787.81
#Mann= 4 ,-1,0
       0     .08       0   43.66      .1       0    87.9    .045       0
     123      .1       0
Bank Sta=87.9,123
XS Rating Curve= 0 ,0
Exp/Cntr(USF)=0,0
Exp/Cntr=0.3,0.1

Type RM Length L Ch R = 1 ,17598   ,86.4,88.4,89.9
XS GIS Cut Line= 4
2159228.34392603625298.6663787292159262.99628354625280.084679773
2159322.25683697 625196.215930432159360.92685912625161.563572917
#Sta/Elev= 30
       0 1760.85     8.9 1757.18    11.6 1756.57      18 1756.23    31.6 1756.43
      37 1756.18    52.7 1752.12    62.2 1750.65    68.1 1748.24    73.8 1746.68
      76 1746.33    82.4 1745.42    91.9 1746.46    96.8 1746.78   106.5 1746.37
   111.4 1746.83   116.9 1747.63   124.5 1749.35   126.1 1750.01   131.2  1752.7
   138.4 1759.06   146.6 1765.11   151.2 1769.21   156.9 1773.65   162.5 1778.47
   166.1 1781.17   171.4 1784.43   176.7 1786.98   188.5 1793.31   193.9 1796.96
#Mann= 4 ,-1,0
       0     .08       0   69.32      .1       0      76    .045       0
    91.9      .1       0
Bank Sta=76,91.9
XS Rating Curve= 0 ,0
Exp/Cntr(USF)=0,0
Exp/Cntr=0.3,0.1

Type RM Length L Ch R = 1 ,17509   ,84.2,78.5,71.2
XS GIS Cut Line= 4
2159276.51751834625352.3374390312159304.71533878625345.287983921
2159388.22426854625271.539838158 2159420.7602152625236.834828387
#Sta/Elev= 30
       0 1755.37     5.6 1754.83    16.1 1753.22    24.4 1751.43    28.5 1750.76
    37.3 1751.01    40.1 1750.78    44.4  1749.4    54.3  1744.1    57.1 1743.06
    59.4 1742.51    62.8 1742.29    76.9 1742.15      87  1742.2    91.1 1742.53
    93.9  1743.1    99.6 1745.19   103.1 1746.15   125.9  1748.1   129.7 1748.72
     132 1749.46   135.1 1750.95     138 1752.76   144.9 1757.68   156.3 1765.25
   165.6 1771.68   169.6 1774.09   176.1 1777.28   178.9 1779.27     188 1786.59
#Mann= 4 ,-1,0
       0     .08       0      20      .1       0    57.1    .045       0
    93.9      .1       0
Bank Sta=57.1,93.9
XS Rating Curve= 0 ,0
Exp/Cntr(USF)=0,0
Exp/Cntr=0.3,0.1

Type RM Length L Ch R = 1 ,17431   ,230.4,253.3,267.6
XS GIS Cut Line= 3
2159380.63254765625392.4651065782159437.02818853625305.702582151
2159460.88788275625282.927419489
#Sta/Elev= 30
       0 1746.28     3.9  1746.5     7.8  1746.5    10.7 1746.19    13.6 1745.64
    16.5 1744.81      23  1742.2    28.1 1740.33    32.5 1739.34    37.3 1738.88
    46.9 1738.69    51.6 1738.84    53.21739.073    62.8 1740.28    75.5  1743.1
    80.3 1743.92      83 1744.74      85  1745.5    85.9 1745.97    88.8 1747.89
    91.7 1750.22   100.4 1757.87   111.7 1767.37   115.8  1770.3   125.9  1776.8
   127.4 1777.88   129.9 1779.91   134.4  1783.8   135.5  1784.6   136.5 1785.09
#Mann= 3 ,-1,0
       0      .1       0    32.5    .045       0    53.2      .1       0
Bank Sta=32.5,53.2
XS Rating Curve= 0 ,0
Exp/Cntr(USF)=0,0
Exp/Cntr=0.3,0.1

Type RM Length L Ch R = 1 ,17177   ,97.6,118.8,132.9
XS GIS Cut Line= 2
2159251.94019471625461.5451174452159687.09793486   625545.090911
#Sta/Elev= 30
       0 1758.83    28.8 1751.08    34.1 1750.72    44.3 1751.52    53.2    1749
    61.3 1750.79    65.4  1750.5    69.5 1748.69    73.6 1745.74    89.8 1741.14
      98 1736.94   110.2 1734.61   138.7  1734.4   191.2 1736.41   216.1 1736.45
   240.5 1738.03   260.9 1738.18   277.2 1736.35   285.4  1736.7   293.1 1736.12
   311.71731.826     322 1731.03   333.41731.119   342.4  1731.4   354.6 1733.76
   379.2 1734.58   383.1 1735.97   403.5 1750.46   407.5 1751.33   443.1 1750.92
#Mann= 4 ,-1,0
       0     .08       0  136.92      .1       0   256.9    .045       0
   278.1      .1       0
#XS Ineff= 2 , 0
          243.13 1746.36
Permanent Ineff=
       F       F
Bank Sta=311.7,333.4
XS Rating Curve= 0 ,0
Exp/Cntr(USF)=0,0
Exp/Cntr=0.3,0.1

Type RM Length L Ch R = 1 ,17059   ,226.5,205.3,182.4
XS GIS Cut Line= 3
2159238.14254886625468.4149410392159472.13530417625519.738823688
2159501.93626828625629.560895163
#Sta/Elev= 30
       0  1764.3    22.6 1757.76    34.8 1754.96      43 1752.35    52.7 1751.01
    59.4    1749    63.5 1748.53    71.7 1748.86    79.9  1744.3   104.5 1735.81
   109.8 1734.44   124.9 1733.92   165.9 1734.19   190.3  1734.9   198.6 1735.67
   219.1 1735.99   231.4 1735.15   239.6  1736.6   249.3 1736.71   265.9  1731.7
     2811728.156   290.8 1727.24   303.2 1727.92     3051728.397   307.4 1729.01
   315.7 1733.48   319.8 1736.35   323.9 1737.97   328.1 1738.25   353.3 1737.13
#Mann= 1 ,-1,0
       0   -9999       0
Bank Sta=281,305
XS Rating Curve= 0 ,0
Exp/Cntr(USF)=0,0
Exp/Cntr=0.3,0.1

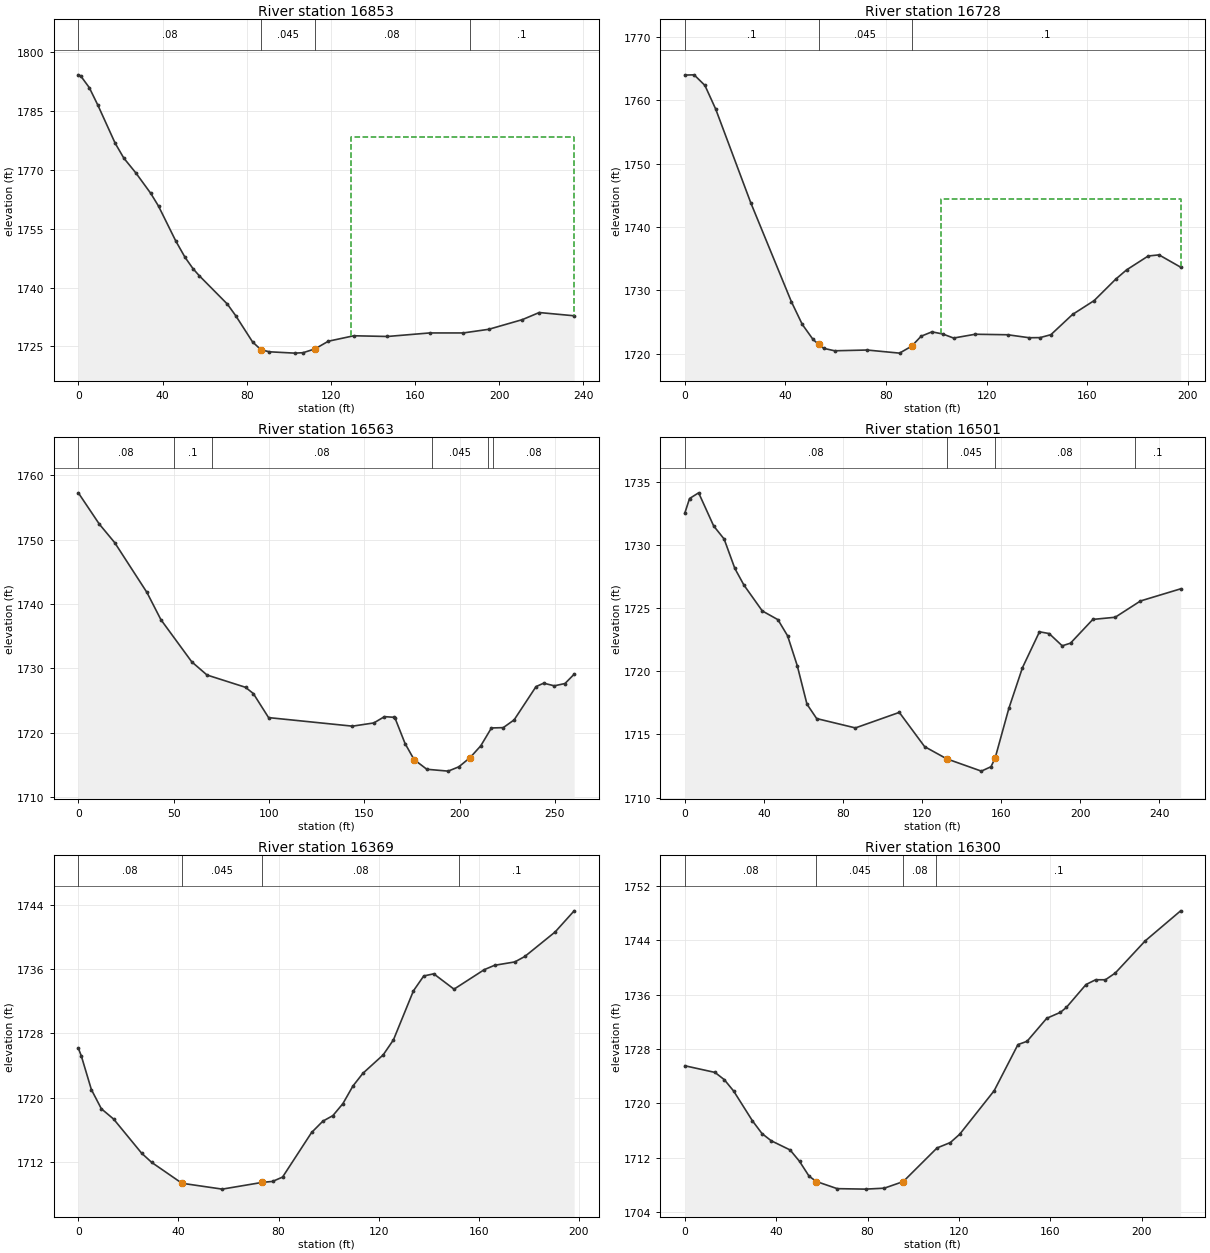
Type RM Length L Ch R = 1 ,16853   ,132.3,125.6,118
XS GIS Cut Line= 3
2159207.08611187625609.4966444392159271.35464848625624.224850746
2159440.72902101625633.597345669
#Sta/Elev= 30
       0  1794.3     1.1 1794.04     5.2 1791.04     9.3 1786.54    17.5 1776.85
    21.6 1773.06    27.4 1769.22    34.4 1764.06    38.1  1760.8    46.3  1751.9
    50.7 1747.73    54.5 1744.83    57.4 1743.07    70.8  1735.8    74.8 1732.82
    82.8 1726.13    86.8 1724.14    90.8 1723.62   102.8 1723.28   106.8 1723.39
   112.4 1724.35   118.8 1726.32   130.9 1727.71   146.9 1727.53   166.9 1728.43
   182.9 1728.43     195 1729.36     211 1731.83     219 1733.64   235.6 1732.81
#Mann= 4 ,-1,0
       0     .08       0    86.8    .045       0   112.4     .08       0
  185.93      .1       0
#XS Ineff= 2 , 0
                          129.58         1778.49
Permanent Ineff=
       F       F
Bank Sta=86.8,112.4
XS Rating Curve= 0 ,0
Exp/Cntr(USF)=0,0
Exp/Cntr=0.3,0.1

Type RM Length L Ch R = 1 ,16728   ,173.6,164.6,153.7
XS GIS Cut Line= 2
2159284.74392694625762.8038828182159468.17704186625690.501779128
#Sta/Elev= 30
       0 1763.99     3.7 1764.03       8 1762.36    12.3 1758.61    26.2 1743.87
    42.4 1728.21    46.7 1724.65      51 1722.26    53.2 1721.49    55.3 1720.85
    59.6 1720.47    72.5 1720.59    85.4  1720.1    90.2 1721.19      94 1722.77
    98.3 1723.46   102.6 1723.12   106.9 1722.48   115.5 1723.08   128.4    1723
     137 1722.53   141.3 1722.55   145.6 1723.01   154.2  1726.2   162.8 1728.39
   171.4 1731.78   175.7 1733.24   184.3 1735.43   188.6 1735.61   197.2 1733.67
#Mann= 3 ,-1,0
       0      .1       0    53.2    .045       0    90.2      .1       0
#XS Ineff= 2 , 0
                          101.75          1744.5
Permanent Ineff=
       F       F
Bank Sta=53.2,90.2
XS Rating Curve= 0 ,0
Exp/Cntr(USF)=0,0
Exp/Cntr=0.3,0.1

Type RM Length L Ch R = 1 ,16563   ,59.5,62.5,64.1
XS GIS Cut Line= 4
2159305.26098377 625855.554634062159434.85037411  625873.3293958
 2159455.4691837625853.2257475142159527.62251763625783.303959995
#Sta/Elev= 30
       0 1757.26      11  1752.4    19.1 1749.51      36 1741.77    43.3 1737.55
    59.5 1730.99    67.5 1728.94    87.7 1727.03    91.8 1726.06    99.8 1722.32
   143.8 1720.99     155 1721.49   160.6 1722.47   165.4 1722.37   166.2 1722.19
   171.4 1718.29   176.11715.807   182.8 1714.29     194    1714   199.6 1714.67
   205.51716.101   211.1 1717.93   216.7 1720.71   222.9 1720.76   228.6 1721.96
   240.1 1727.14   244.1 1727.67   249.7 1727.26   255.3 1727.62   260.1 1729.07
#Mann= 6 ,-1,0
       0     .08       0      50      .1       0      70     .08       0
   185.7    .045       0   215.1      .1       0  217.53     .08       0
Bank Sta=176.1,205.5
XS Rating Curve= 0 ,0
Exp/Cntr(USF)=0,0
Exp/Cntr=0.3,0.1

Type RM Length L Ch R = 1 ,16501   ,125.6,131.7,145.8
XS GIS Cut Line= 4
2159418.44016166625967.2845517272159437.44963107625933.398106239
2159558.94493563625847.4422445142159603.57586383625802.811316311
#Sta/Elev= 30
       0 1732.51     2.4 1733.67       7 1734.12    14.6  1731.5    19.9 1730.46
    25.3 1728.14    29.9 1726.82    39.2 1724.77    47.1 1724.08      52  1722.8
    56.9 1720.43    61.8 1717.39    66.7 1716.25    86.3 1715.51   108.5 1716.74
   121.3 1714.03   132.51713.063     150 1712.09   154.9 1712.44     157 1713.14
   163.9 1717.05   170.8 1720.28   179.4 1723.12   184.3 1722.98   190.9 1722.01
   195.1 1722.22   206.4  1724.1   217.7 1724.27   230.5 1725.56   250.8 1726.52
#Mann= 4 ,-1,0
       0     .08       0   132.5    .045       0     157     .08       0
  227.68      .1       0
Bank Sta=132.5,157
XS Rating Curve= 0 ,0
Exp/Cntr(USF)=0,0
Exp/Cntr=0.3,0.1

Type RM Length L Ch R = 1 ,16369   ,65.4,68.6,70.2
XS GIS Cut Line= 3
2159434.97013506625984.6410238062159546.54745557625995.385506521
2159631.67681863626007.782986578
#Sta/Elev= 30
       0 1726.16     1.2 1725.19     5.2 1721.02     9.2 1718.62    14.1 1717.34
    25.3 1713.09    29.3 1711.95    41.4 1709.35    57.5 1708.62    73.5 1709.46
    77.6 1709.58    81.6 1710.12    93.2 1715.67    97.7 1717.08   101.7 1717.77
   105.7 1719.26   109.7 1721.45   113.7 1723.04   121.8 1725.33   125.9  1727.2
   133.9 1733.31     138 1735.15     142 1735.42   150.1 1733.51   162.2 1735.94
   166.3 1736.48   174.4  1736.9   178.4 1737.58   190.5 1740.63   198.1 1743.26
#Mann= 4 ,-1,0
       0     .08       0    41.4    .045       0    73.5     .08       0
  152.09      .1       0
Bank Sta=41.4,73.5
XS Rating Curve= 0 ,0
Exp/Cntr(USF)=0,0
Exp/Cntr=0.3,0.1

Type RM Length L Ch R = 1 ,16300   ,65.1,65.4,67.6
XS GIS Cut Line= 3
2159387.40484154626032.2102578642159515.51780418626063.955062764
2159594.87981643626094.566124632
#Sta/Elev= 30
       0 1725.54    13.2 1724.56    17.3 1723.49    21.4 1721.81    29.6 1717.44
    33.8 1715.56    37.8 1714.51    46.1 1713.15    50.2 1711.48    54.4 1709.29
    57.6 1708.51    66.7 1707.46    79.1 1707.39    87.3 1707.53    95.6  1708.5
   110.4 1713.45   116.2 1714.24   120.3 1715.46   135.4 1721.87   145.8 1728.65
   149.8 1729.14   158.4 1732.52   164.4  1733.4     167 1734.12   175.6 1737.49
   179.8 1738.19   184.1 1738.19   188.4 1739.18   201.5 1743.91     217 1748.33
#Mann= 4 ,-1,0
       0     .08       0    57.6    .045       0    95.6     .08       0
     110      .1       0
Bank Sta=57.6,95.6
XS Rating Curve= 0 ,0
Exp/Cntr(USF)=0,0
Exp/Cntr=0.3,0.1

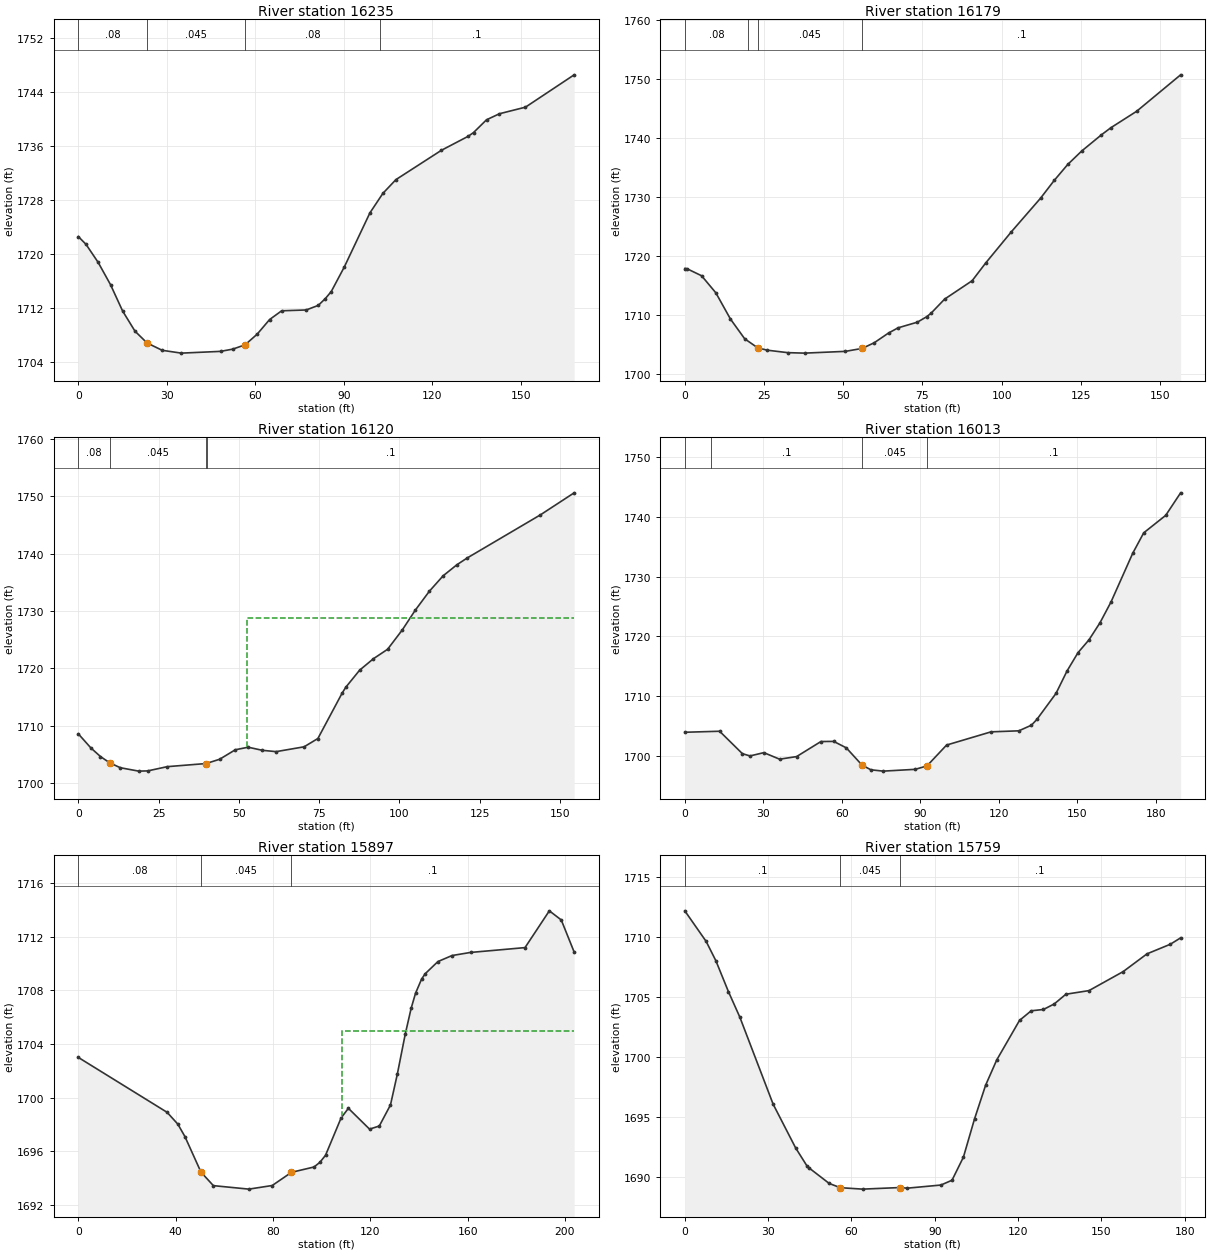
Type RM Length L Ch R = 1 ,16235   ,49.1,55.7,59.1
XS GIS Cut Line= 3
2159389.67232761626096.8336106962159469.03433986626118.374728307
2159547.26260908626153.520762304
#Sta/Elev= 30
       0 1722.55     2.6  1721.4     6.7 1718.74    10.9 1715.43      15 1711.53
    19.2 1708.54    23.3 1706.79    28.4 1705.71    34.9 1705.29    48.2 1705.55
    52.3 1705.88    56.5 1706.52    60.6  1708.1    64.8 1710.26    68.9 1711.56
    77.2 1711.68    81.3 1712.36    83.7 1713.37    85.7 1714.41    90.1 1718.03
    98.8 1726.06   103.2 1728.95   107.6 1730.98     123 1735.32   132.1  1737.4
   133.9 1737.95   138.3 1739.84   142.7 1740.74   151.5 1741.71     168  1746.5
#Mann= 4 ,-1,0
       0     .08       0    23.3    .045       0    56.5     .08       0
  102.23      .1       0
Bank Sta=23.3,56.5
XS Rating Curve= 0 ,0
Exp/Cntr(USF)=0,0
Exp/Cntr=0.3,0.1

Type RM Length L Ch R = 1 ,16179   ,58.8,58.8,57.8
XS GIS Cut Line= 3
2159375.52925628626138.664770686 2159440.6011496626173.610787469
2159517.12087601626204.941699068
#Sta/Elev= 30
       0 1717.84      .7 1717.81     5.3 1716.62     9.8 1713.73    14.4  1709.3
    18.9 1705.95      23 1704.42      26 1704.02    32.5  1703.6    37.8 1703.52
    50.7 1703.82      56 1704.32    59.8 1705.28    64.3 1706.92    67.3  1707.8
    73.4 1708.76    76.3 1709.67    77.7 1710.26      82 1712.66    90.7 1715.78
      95  1718.8   103.1 1724.08   112.3 1729.76   116.6 1732.76   120.9 1735.48
   125.3 1737.75   131.5 1740.48   134.5 1741.69   142.6 1744.46   156.5 1750.64
#Mann= 4 ,-1,0
       0     .08       0      20      .1       0      23    .045       0
      56      .1       0
Bank Sta=23,56
XS Rating Curve= 0 ,0
Exp/Cntr(USF)=0,0
Exp/Cntr=0.3,0.1

Type RM Length L Ch R = 1 ,16120   ,105.9,107.8,108.8
XS GIS Cut Line= 3
2159356.85121283626195.3014185762159405.05261529626219.402119805
2159497.84031503626257.963241773
#Sta/Elev= 30
       0 1708.58     3.9 1706.13     6.9 1704.62     9.8 1703.52    13.1 1702.67
    18.8 1702.08    21.6 1702.12    27.7 1702.86    39.7  1703.4      40 1703.44
      44 1704.15    48.9 1705.81    52.9 1706.25    57.3 1705.71    61.6 1705.48
    70.3 1706.32    74.6 1707.77    82.1 1715.64    83.3 1716.72    87.6 1719.69
    91.9 1721.69    96.3 1723.33   100.9 1726.72   104.9 1730.13   109.3 1733.45
   113.6 1736.15   117.9 1738.08   121.1 1739.26   143.9 1746.78   154.4 1750.62
#Mann= 4 ,-1,0
       0     .08       0     9.8    .045       0    39.7     .08       0
      40      .1       0
#XS Ineff= 2 , 0
                           52.55         1728.87
Permanent Ineff=
       F       F
Bank Sta=9.8,39.7
XS Rating Curve= 0 ,0
Exp/Cntr(USF)=0,0
Exp/Cntr=0.3,0.1

Type RM Length L Ch R = 1 ,16013   ,111.2,115.8,124.9
XS GIS Cut Line= 4
2159282.04263621626252.1609979522159321.57381141626288.763937945
2159396.73184819626335.6157011352159441.63145458626349.280798733
#Sta/Elev= 30
       0 1703.96    13.3 1704.13      22 1700.38    24.9    1700    30.2 1700.55
    36.2 1699.46    42.7 1699.89      52 1702.41    56.9 1702.43    61.7 1701.35
    67.7 1698.47    71.1 1697.68    75.8 1697.46      88 1697.76    92.5 1698.33
     100 1701.82     117 1704.03   127.6  1704.2   132.4 1705.14   134.5 1706.11
   141.8 1710.46     146  1714.2   150.2 1717.27   154.4 1719.42   158.6 1722.27
   162.8 1725.74   171.1 1733.89   175.3 1737.31   183.7 1740.23   189.4    1744
#Mann= 4 ,-1,0
       0     .08       0      10      .1       0    67.7    .045       0
    92.5      .1       0
Bank Sta=67.7,92.5
XS Rating Curve= 0 ,0
Exp/Cntr(USF)=0,0
Exp/Cntr=0.3,0.1

Type RM Length L Ch R = 1 ,15897   ,158.9,137.8,117.7
XS GIS Cut Line= 3
2159203.48299367626285.8091076932159263.81739661626387.468444156
2159332.41678626626438.711361723
#Sta/Elev= 30
       0    1703    36.5 1698.91    40.9 1698.03    43.8 1697.11    50.4 1694.46
    55.5 1693.45    70.1 1693.19    79.7 1693.46    87.6 1694.44    96.9 1694.84
    99.3 1695.19   101.6 1695.71     108 1698.49     111 1699.21   119.7 1697.66
   123.7 1697.89   128.3 1699.46   131.1 1701.74   134.4 1704.76   136.8 1706.66
   138.6 1707.78   141.1 1708.84   142.6 1709.24   147.8 1710.14   153.6 1710.59
   161.2 1710.82   183.6 1711.18   193.6 1713.92   198.5 1713.24   203.8 1710.85
#Mann= 3 ,-1,0
       0     .08       0    50.4    .045       0    87.6      .1       0
#XS Ineff= 2 , 0
                          108.17         1704.95
Permanent Ineff=
       F       F
Bank Sta=50.4,87.6
XS Rating Curve= 0 ,0
Exp/Cntr(USF)=0,0
Exp/Cntr=0.3,0.1

Type RM Length L Ch R = 1 ,15759   ,80.3,78.1,74.9
XS GIS Cut Line= 3
2159136.53660136626459.3738284842159253.89941257626472.597807211
 2159311.7543195626455.241335131
#Sta/Elev= 30
       0 1712.19     7.7 1709.64    11.2 1708.03    15.7 1705.47    19.8 1703.35
    31.8  1696.1    39.9 1692.46    43.9 1690.99    44.7  1690.8      52  1689.5
      56 1689.15      64 1689.03    77.3 1689.16    80.1 1689.11    92.2 1689.37
    96.2 1689.77   100.3 1691.69   104.3 1694.87   108.3 1697.68   112.3 1699.78
   120.5 1703.07   124.7 1703.87   129.1 1703.98     133 1704.44   137.2 1705.25
   145.5 1705.55   157.8 1707.13   166.4 1708.61   174.8 1709.41   178.5 1709.94
#Mann= 3 ,-1,0
       0      .1       0      56    .045       0    77.3      .1       0
Bank Sta=56,77.3
XS Rating Curve= 0 ,0
Exp/Cntr(USF)=0,0
Exp/Cntr=0.3,0.1

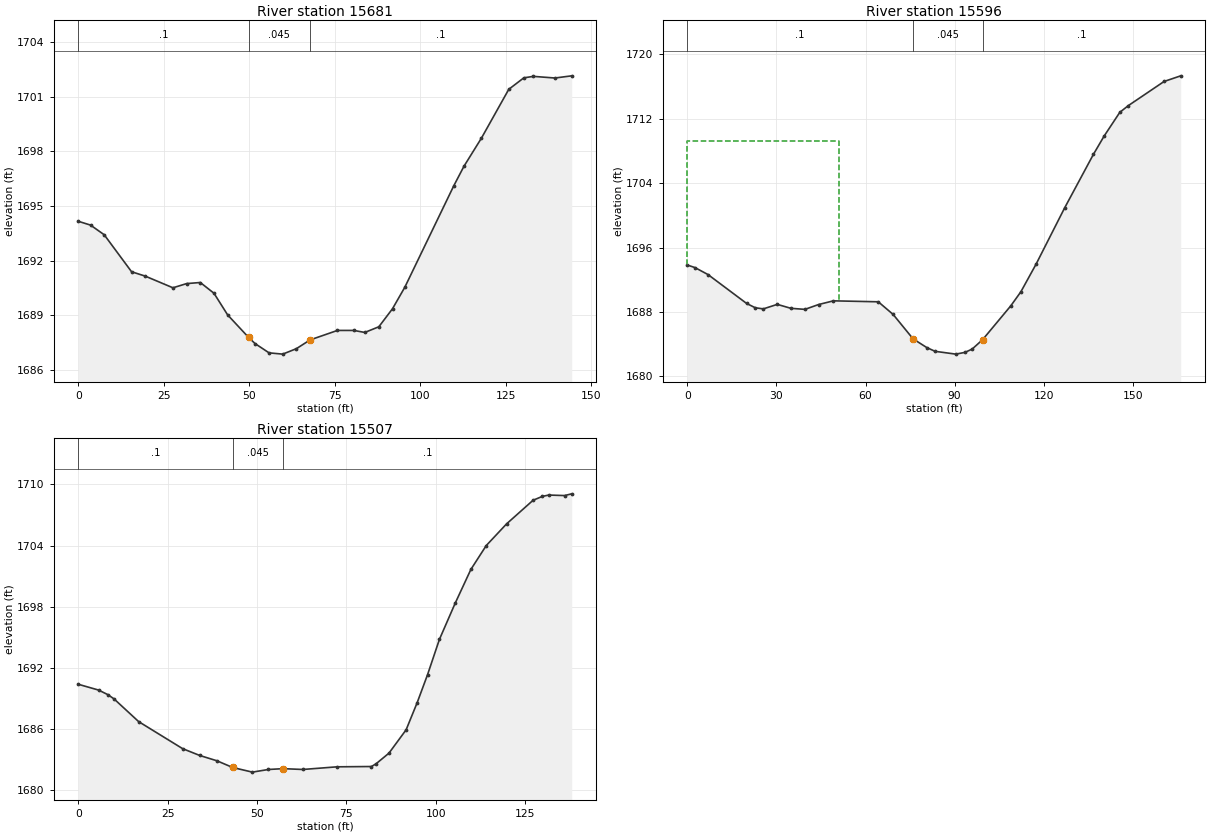
Type RM Length L Ch R = 1 ,15681   ,70.1,84.7,99.1
XS GIS Cut Line= 3
2159136.58875255626548.2796964462159238.60527512626540.210592966
2159276.93351665626523.207839204
#Sta/Elev= 30
       0 1694.17     3.6 1693.96     7.6 1693.43    15.6  1691.4    19.6 1691.16
    27.7 1690.52    31.7 1690.75    35.7 1690.81    39.7 1690.22    43.7 1689.03
    49.81687.802    51.7 1687.46    55.8 1686.95    59.8 1686.88    63.8 1687.18
    67.8 1687.66    75.8 1688.18    80.6 1688.18    83.8 1688.07    87.9 1688.38
    91.9 1689.37    95.5 1690.55   109.8 1696.11   112.8 1697.19   117.9 1698.73
   125.9 1701.41   130.3 1702.04   133.1 1702.12   139.4 1702.03   144.3 1702.15
#Mann= 3 ,-1,0
       0      .1       0    49.8    .045       0    67.8      .1       0
Bank Sta=49.8,67.8
XS Rating Curve= 0 ,0
Exp/Cntr(USF)=0,0
Exp/Cntr=0.3,0.1

Type RM Length L Ch R = 1 ,15596   ,92.1,89.2,86.5
XS GIS Cut Line= 4
2159122.11315616626567.8487692892159171.28194117626596.874934987
2159213.22847117626641.7032876552159252.29317849626668.920501774
#Sta/Elev= 30
       0 1693.83     2.6 1693.51       7 1692.64      20 1689.05    22.9 1688.52
    25.6 1688.38    30.3 1688.94    34.9 1688.45    39.6 1688.32    44.2 1688.92
    49.2 1689.38    64.3 1689.26    69.3 1687.69      76 1684.66    80.6 1683.58
    83.4 1683.11    90.4 1682.76    93.5 1682.98    95.9 1683.39    99.4 1684.55
   108.9 1688.76   112.3 1690.51   117.4 1693.93     127 1700.91   136.7 1707.57
   140.3 1709.84   145.6  1712.8   148.5 1713.64   160.5 1716.63   166.1 1717.33
#Mann= 3 ,-1,0
       0      .1       0      76    .045       0    99.4      .1       0
#XS Ineff= 2 , 0
            51.2 1709.25
Permanent Ineff=
       F       F
Bank Sta=76,99.4
XS Rating Curve= 0 ,0
Exp/Cntr(USF)=0,0
Exp/Cntr=0.3,0.1

Type RM Length L Ch R = 1 ,15507   ,78.8,78.5,78.2
XS GIS Cut Line= 3
2159083.86665347 626650.028553152159166.15870087626704.783183909
  2159202.021383626720.473107343
#Sta/Elev= 30
       0 1690.41     5.7 1689.84     8.3 1689.39      10 1688.98    16.9 1686.75
    29.2  1684.1      34 1683.43    38.8 1682.91    43.21682.254    48.7  1681.8
    53.2 1682.06    57.3 1682.14    62.8 1682.06    72.4 1682.32      82 1682.35
    83.3 1682.62    86.9 1683.66    91.7 1685.95    94.8 1688.62    97.7 1691.36
     101  1694.8   105.4 1698.34   109.8 1701.66   114.1    1704   119.8 1706.13
   127.2 1708.44   129.8 1708.82   131.6 1708.95     136  1708.9     138 1709.07
#Mann= 3 ,-1,0
       0      .1       0    43.2    .045       0    57.3      .1       0
Bank Sta=43.2,57.3
XS Rating Curve= 0 ,0
Exp/Cntr(USF)=0,0
Exp/Cntr=0.3,0.1