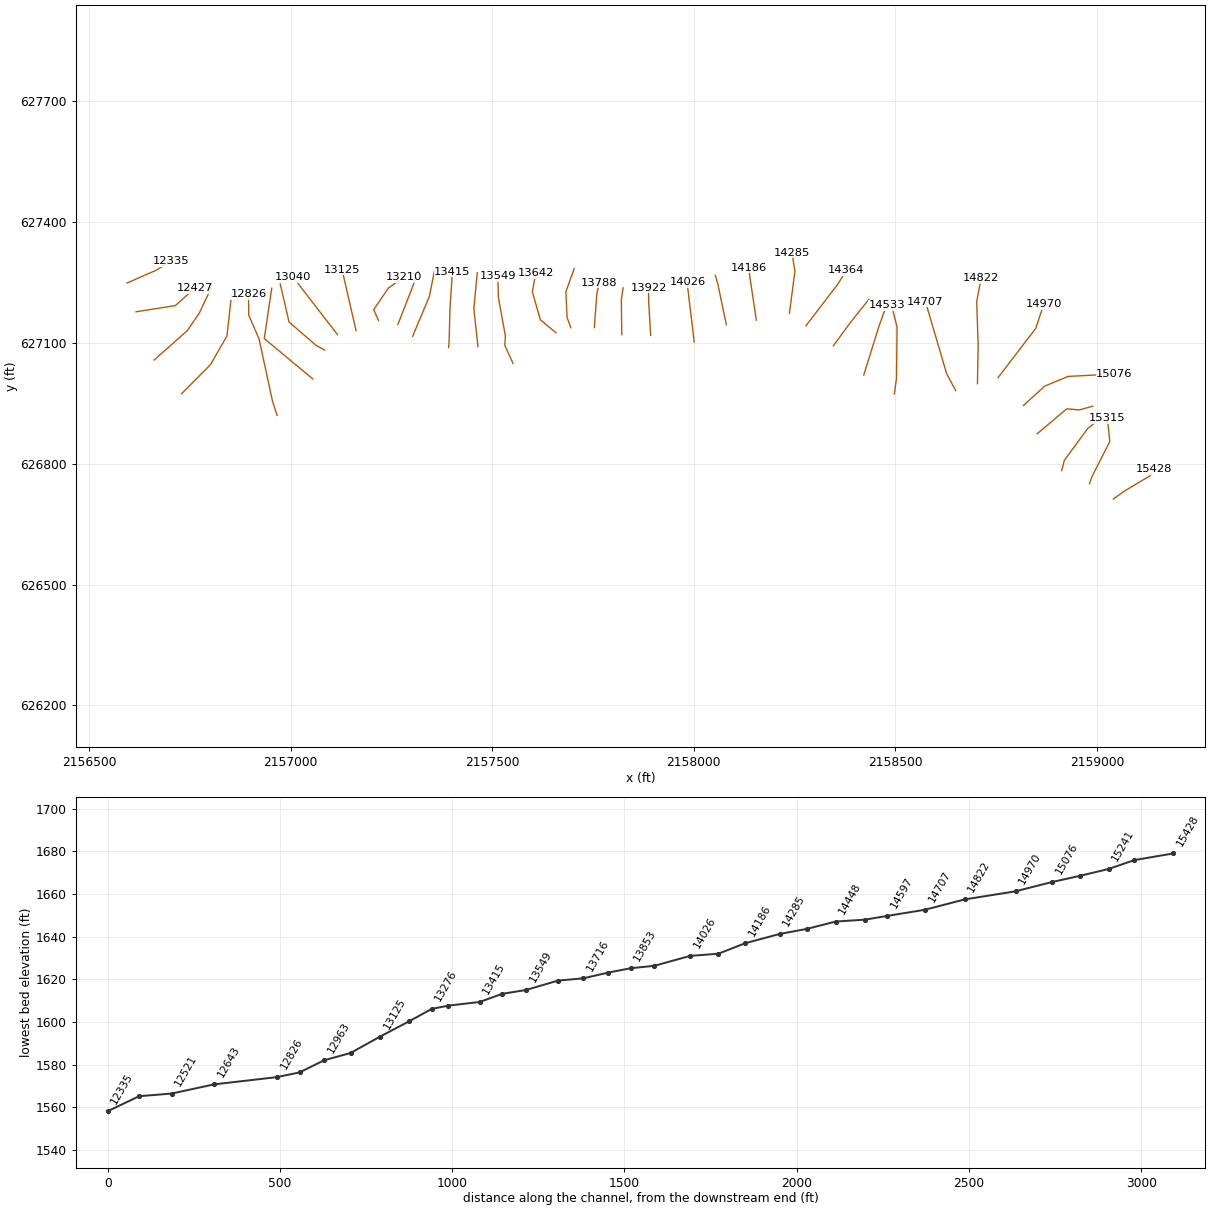
HEC-RAS study LFRFLIKANA.prj: LFRFLIKANA

--- LFRFLIKANA.g01 (geometry) --- (continued)

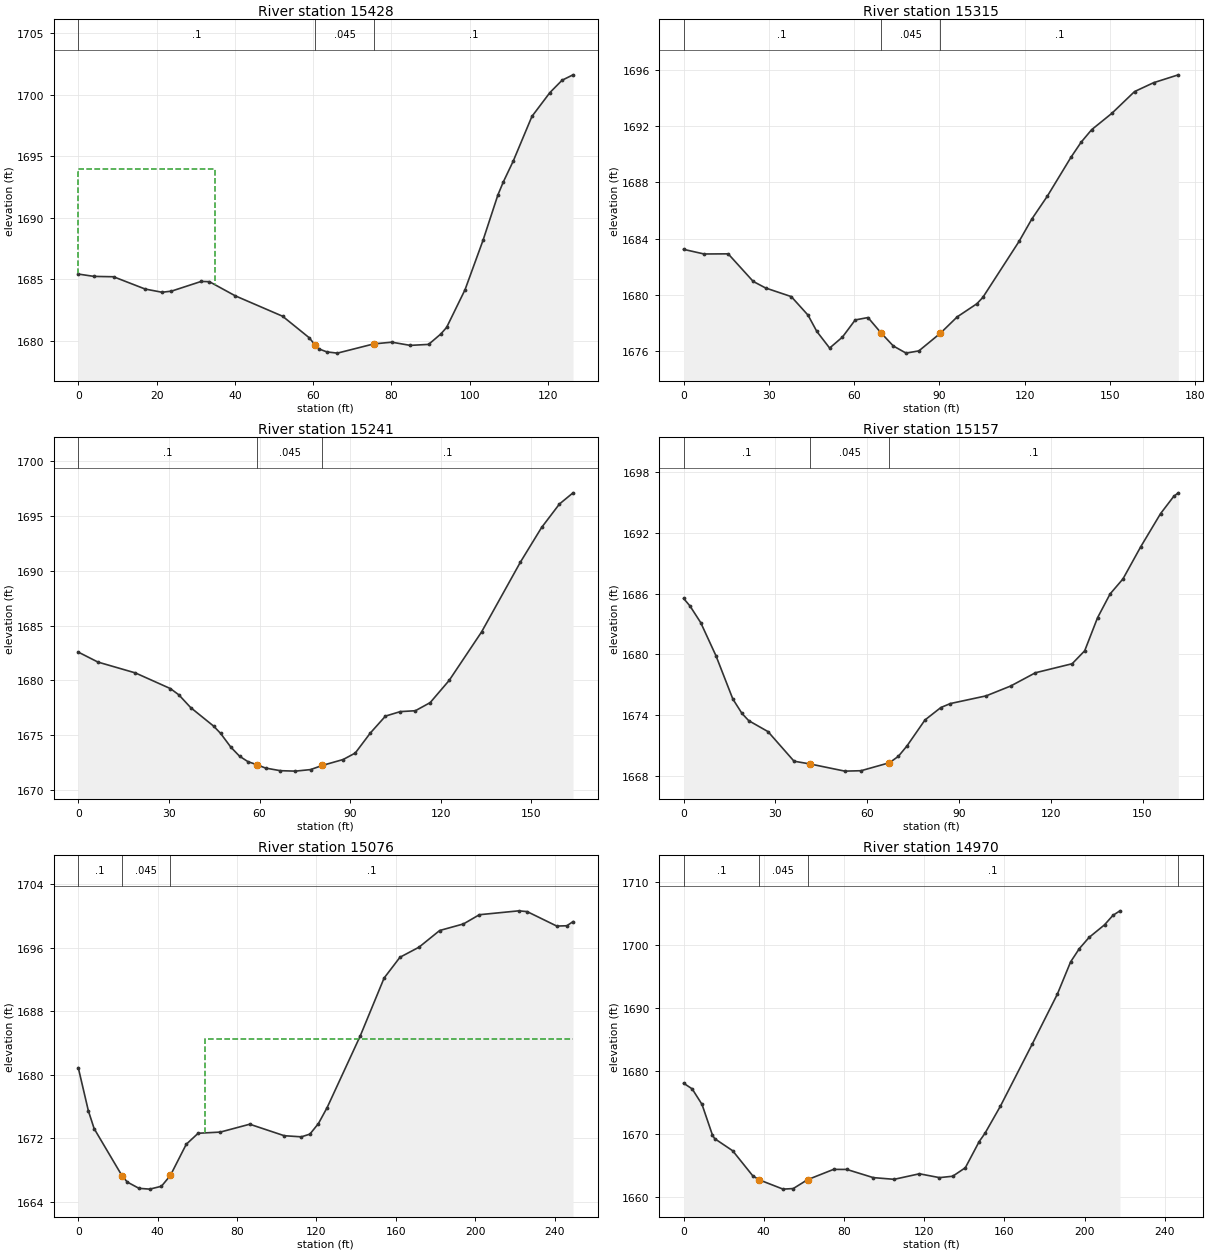
Type RM Length L Ch R = 1 ,15428   ,106.6,113.9,120.9
XS GIS Cut Line= 4
2159040.90733428626712.6243392212159066.60259816626731.203991562
2159131.43372547 626769.944543252159141.71183102626786.152325079
#Sta/Elev= 30
       0 1685.43       4 1685.24       9 1685.21    17.1 1684.21    21.4 1683.95
    23.8 1684.04    31.4 1684.83    33.5 1684.81    40.1 1683.66    52.2    1682
      59 1680.25    60.5 1679.66    61.5 1679.34    63.5  1679.1    66.2    1679
    75.5 1679.75    80.1 1679.89    84.8 1679.63    89.5 1679.71    92.6 1680.55
    94.1 1681.09    98.8 1684.15   103.4 1688.17   107.2 1691.86   108.6 1692.93
   111.1  1694.6   115.9 1698.25   120.5 1700.19   123.6 1701.19   126.4 1701.63
#Mann= 3 ,-1,0
       0      .1       0    60.5    .045       0    75.5      .1       0
#XS Ineff= 2 , 0
           34.86 1693.96
Permanent Ineff=
       F       F
Bank Sta=60.5,75.5
XS Rating Curve= 0 ,0
Exp/Cntr(USF)=0,0
Exp/Cntr=0.3,0.1

Type RM Length L Ch R = 1 ,15315   ,77,73.9,71.8
XS GIS Cut Line= 4
2158981.49843629626750.3742012532158987.46335984626767.726706139
2159031.92915361626855.0314963442159025.96423005626912.511668777
#Sta/Elev= 30
       0 1683.23     7.2  1682.9    15.7 1682.91    24.5 1680.95    28.9 1680.48
    37.9 1679.87    43.8 1678.55    46.9 1677.39    51.4 1676.21    55.9 1676.99
    60.4 1678.21    64.9 1678.38    69.4 1677.31    73.8 1676.36    78.3 1675.85
    82.8 1676.01    90.4 1677.27    96.3 1678.43   103.2 1679.36   105.3 1679.81
   118.1 1683.81   122.5 1685.37     128 1687.01   136.3 1689.77   139.9 1690.85
   143.6 1691.74   150.7  1692.9   158.7 1694.45   165.4 1695.08   174.1 1695.64
#Mann= 3 ,-1,0
       0      .1       0    69.4    .045       0    90.4      .1       0
Bank Sta=69.4,90.4
XS Rating Curve= 0 ,0
Exp/Cntr(USF)=0,0
Exp/Cntr=0.3,0.1

Type RM Length L Ch R = 1 ,15241   ,87.7,83.7,80.4
XS GIS Cut Line= 4
2158912.63068252626782.9101479132158919.13787185626808.396639464
2158977.16031006626887.5674430042159008.06945939626911.969402999
#Sta/Elev= 30
       0 1682.58     6.5 1681.67    18.9 1680.68    30.5 1679.25    33.3 1678.68
    37.2 1677.52    44.8 1675.83    47.1 1675.17    50.5 1673.91    53.4 1673.08
    56.2 1672.58    59.1 1672.31      62    1672    66.9 1671.76    71.9 1671.72
    76.9 1671.86    80.8 1672.24    87.7 1672.78    91.7 1673.37    96.7  1675.2
   101.7 1676.74   106.6 1677.15   111.6 1677.23   116.5 1677.97   122.8    1680
   133.5 1684.41   146.4  1690.8   153.4 1693.95   159.3 1696.09   163.8 1697.11
#Mann= 3 ,-1,0
       0      .1       0    59.1    .045       0    80.8      .1       0
Bank Sta=59.1,80.8
XS Rating Curve= 0 ,0
Exp/Cntr(USF)=0,0
Exp/Cntr=0.3,0.1

Type RM Length L Ch R = 1 ,15157   ,77.6,81,79
XS GIS Cut Line= 4
2158851.89691542 626874.553064342158925.10279541626936.371362994
2158956.55421051626933.6600341062158989.63242295626942.878552327
#Sta/Elev= 30
       0 1685.52     2.1 1684.77     5.6 1683.13    10.6 1679.85    16.1 1675.59
    19.1 1674.16    21.3 1673.45    27.6 1672.37    36.1 1669.45    41.3 1669.18
    52.7 1668.47      58 1668.51    67.3  1669.3    70.2 1669.93      73 1670.95
    78.9 1673.52    84.1 1674.75    87.2 1675.14    98.9  1675.9   106.9 1676.87
     115 1678.18     127 1679.07   131.1 1680.35   135.3 1683.61   139.4 1685.96
   143.6 1687.44   149.4 1690.61   155.9 1693.89   160.2 1695.59   161.7 1695.94
#Mann= 3 ,-1,0
       0      .1       0    41.3    .045       0    67.3      .1       0
Bank Sta=41.3,67.3
XS Rating Curve= 0 ,0
Exp/Cntr(USF)=0,0
Exp/Cntr=0.3,0.1

Type RM Length L Ch R = 1 ,15076   ,101.4,105.9,107.7
XS GIS Cut Line= 4
2158817.57901903 626944.517331852158870.46666896626992.718734309
2158928.71003026627016.8194355392159043.27539141627022.750885897
#Sta/Elev= 30
       0 1680.89     5.1 1675.44       8 1673.21    22.1 1667.25    24.7 1666.48
    30.6 1665.69      36 1665.59    41.9 1665.95    46.41667.309    54.4 1671.24
    60.4 1672.63    71.6 1672.78    86.4 1673.77   103.8 1672.32   112.4 1672.18
   116.7 1672.52     121 1673.85   125.4 1675.87   142.1 1684.91   154.1 1692.19
   162.1 1694.81   171.7 1696.08   182.1 1698.18   194.1 1699.01   202.1 1700.17
     222 1700.66   226.2 1700.56   241.1 1698.74   246.2 1698.78   249.3  1699.3
#Mann= 3 ,-1,0
       0      .1       0    22.1    .045       0    46.4      .1       0
#XS Ineff= 2 , 0
                           63.66          1684.5
Permanent Ineff=
       F       F
Bank Sta=22.1,46.4
XS Rating Curve= 0 ,0
Exp/Cntr(USF)=0,0
Exp/Cntr=0.3,0.1

Type RM Length L Ch R = 1 ,14970   ,125.7,147.8,159.6
XS GIS Cut Line= 3
2158754.74258317627013.7327358422158848.11902592627136.006323745
 2158868.3511396627196.504317083
#Sta/Elev= 30
       0 1678.08     4.3 1677.17     9.2  1674.7    14.4 1669.83    15.5 1669.26
    24.5 1667.33    34.5 1663.35    37.7 1662.71    49.6 1661.23    54.7 1661.32
    61.81662.728    74.8 1664.37    81.4 1664.36    94.6 1663.06     105 1662.79
   117.6 1663.67   127.6 1663.06   134.2 1663.28   140.5 1664.63   147.4 1668.79
   150.3 1670.11     158 1674.43   173.8 1684.26   186.4 1692.25     193 1697.37
   197.3 1699.46   202.2 1701.26   209.9 1703.26   214.1 1704.77   217.6 1705.49
#Mann= 4 ,-1,0
       0      .1       0    37.7    .045       0    61.8      .1       0
  246.71     .08       0
Bank Sta=37.7,61.8
XS Rating Curve= 0 ,0
Exp/Cntr(USF)=0,0
Exp/Cntr=0.3,0.1

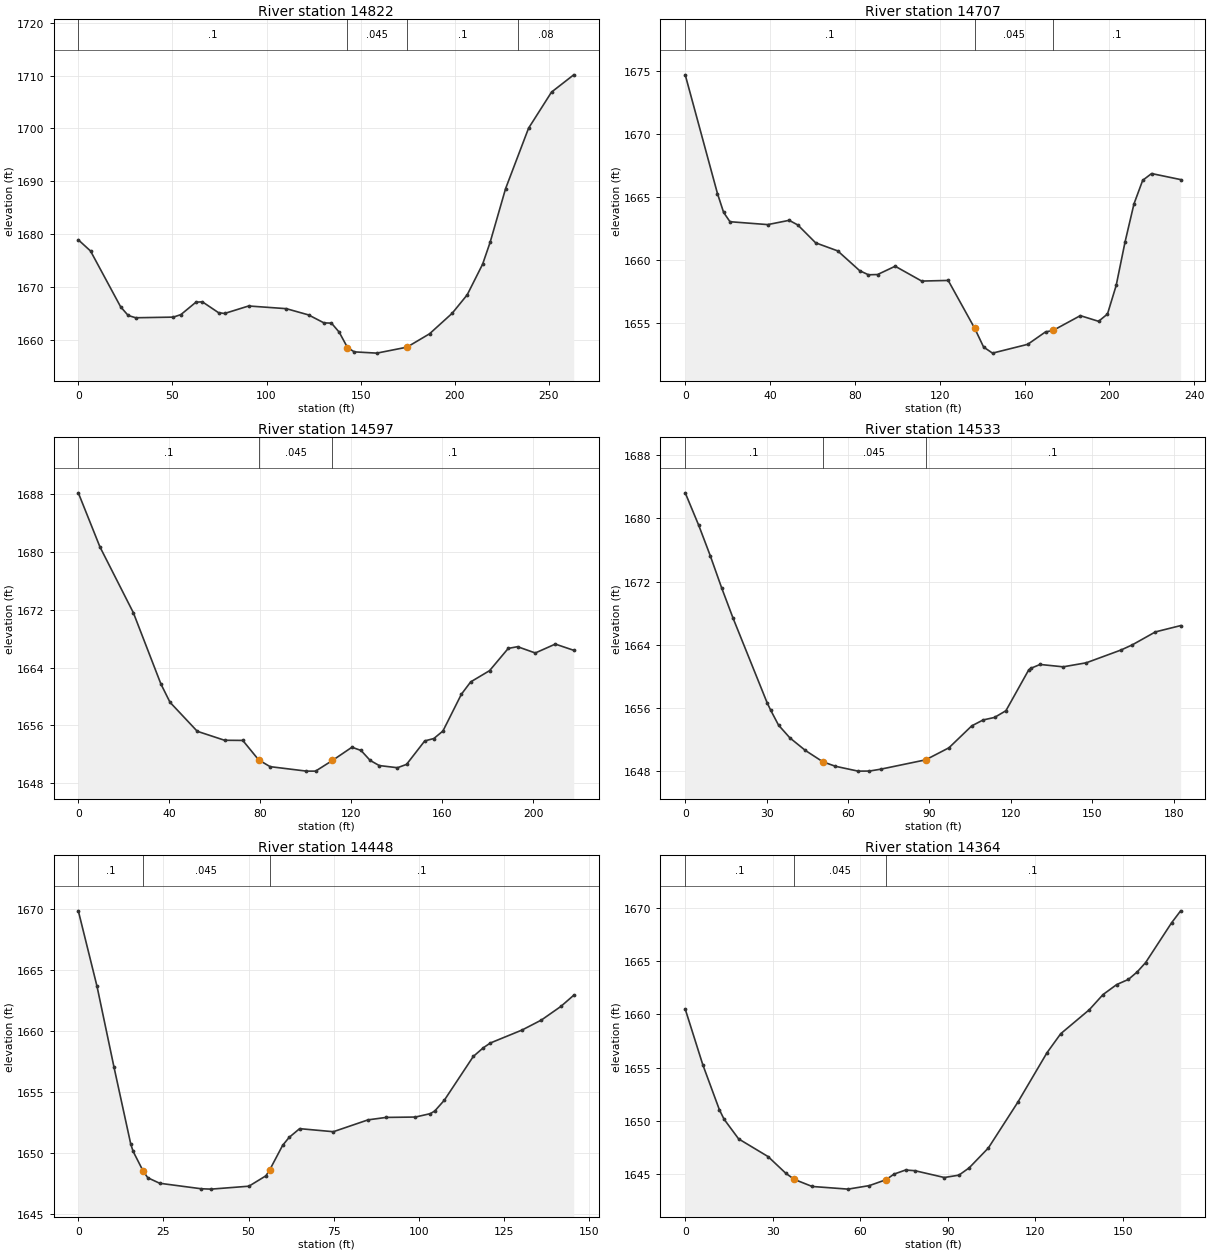
Type RM Length L Ch R = 1 ,14822   ,107.1,115.2,117.6
XS GIS Cut Line= 4
2158703.52859305626998.6697975732158705.33614565627093.867567431
2158701.72104046627202.3207229652158712.56635601627260.764923448
#Sta/Elev= 30
       0 1678.89     6.5 1676.77    22.5 1666.19    26.5 1664.56    30.5 1664.13
    50.5 1664.25    54.5 1664.73    62.5 1667.08    65.9 1667.15    74.5 1665.09
    77.7 1664.94    90.5 1666.36   110.5 1665.85   122.3 1664.67   130.5 1663.16
   134.5 1663.11   138.6  1661.4     143 1658.49   146.6 1657.67   158.6 1657.43
   174.6 1658.56   186.6 1661.09   198.6 1664.97   206.6 1668.47   214.8 1674.28
   218.8 1678.44     227 1688.59   239.2 1700.03   251.4 1706.87   263.2 1710.14
#Mann= 4 ,-1,0
       0      .1       0     143    .045       0   174.6      .1       0
  233.73     .08       0
Bank Sta=143,174.6
XS Rating Curve= 0 ,0
Exp/Cntr(USF)=0,0
Exp/Cntr=0.3,0.1

Type RM Length L Ch R = 1 ,14707   ,117.3,109.8,106.4
XS GIS Cut Line= 3
2158649.30201529626981.7993067122158627.00886665627023.975533864
2158574.58984147627202.320722965
#Sta/Elev= 30
       0 1674.71    15.2 1665.27    18.1 1663.77    21.1 1663.03    38.9  1662.8
      49 1663.14    53.1 1662.77    61.5 1661.35    71.9 1660.71    82.3 1659.13
    86.4 1658.81    90.7 1658.83      99 1659.49   111.5 1658.31     124 1658.36
   136.5 1654.55   140.7 1653.06   144.9 1652.58   161.5 1653.28   169.9 1654.27
   173.4 1654.38   186.3 1655.56   194.9 1655.11   199.1 1655.69   203.2 1657.96
   207.4 1661.43   211.6 1664.45   215.7 1666.32   219.9 1666.86   233.6 1666.38
#Mann= 3 ,-1,0
       0      .1       0   136.5    .045       0   173.4      .1       0
Bank Sta=136.5,173.4
XS Rating Curve= 0 ,0
Exp/Cntr(USF)=0,0
Exp/Cntr=0.3,0.1

Type RM Length L Ch R = 1 ,14597   ,70.4,64,58.1
XS GIS Cut Line= 4
2158497.44037488 626973.221931192158502.79608626627012.720302651
2158504.09529038627139.6588997682158491.44242223627189.065337289
#Sta/Elev= 30
       0 1688.12     9.5 1680.66    24.2 1671.57    36.3 1661.74    40.3 1659.21
    52.3  1655.2    64.3 1653.96    72.3 1653.94    79.3 1651.25    84.3 1650.32
   100.3  1649.7   104.3  1649.7   111.7 1651.17   120.3    1653   124.3 1652.55
   128.3 1651.18   132.3 1650.47   140.3 1650.17   144.3 1650.63   152.3 1653.87
   156.3  1654.2   160.3 1655.24   168.4 1660.31   172.5 1662.02   180.8 1663.57
     189 1666.64   193.1 1666.88   200.9 1666.01   209.7 1667.24   217.8 1666.38
#Mann= 3 ,-1,0
       0      .1       0    79.3    .045       0   111.7      .1       0
Bank Sta=79.3,111.7
XS Rating Curve= 0 ,0
Exp/Cntr(USF)=0,0
Exp/Cntr=0.3,0.1

Type RM Length L Ch R = 1 ,14533   ,92,85.3,76.7
XS GIS Cut Line= 3
2158421.55038866 627020.36042868 2158459.5089931627142.068969891
2158478.18703655627193.885477535
#Sta/Elev= 30
       0 1683.25       5 1679.11     9.2  1675.3    13.4 1671.22    17.6 1667.38
    30.2 1656.61    31.5 1655.68    34.4 1653.78    38.6 1652.16    44.3 1650.57
    50.7 1649.14    55.3 1648.57    63.7 1647.95    67.9 1647.96    72.1  1648.2
    88.6 1649.38    97.2 1650.91   105.6 1653.69   109.8 1654.44     114 1654.76
   118.2 1655.61   126.6 1660.79   127.3 1660.98   130.8 1661.48   139.3 1661.18
   147.8 1661.69   160.6 1663.31   164.8 1663.97   173.3 1665.61   182.6 1666.41
#Mann= 3 ,-1,0
       0      .1       0    50.7    .045       0    88.6      .1       0
Bank Sta=50.7,88.6
XS Rating Curve= 0 ,0
Exp/Cntr(USF)=0,0
Exp/Cntr=0.3,0.1

Type RM Length L Ch R = 1 ,14448   ,85.9,83.8,84.2
XS GIS Cut Line= 3
2158346.08418311 627092.746862332158390.54997688627153.480629429
2158434.47350487627208.249472974
#Sta/Elev= 30
       0 1669.84     5.5 1663.65    10.5 1657.02    15.4 1650.75    16.1 1650.15
      19 1648.56    20.4 1647.99    23.9 1647.54    36.1 1647.09      39 1647.06
    50.1  1647.3    55.1 1648.15    56.2 1648.63      60 1650.64    61.9 1651.29
      65 1652.01    74.9 1651.76    85.1 1652.73    90.4 1652.93      99 1652.96
   103.4 1653.24   104.7 1653.46   107.5 1654.34     116 1657.92   118.9 1658.62
     121 1659.02   130.3 1660.08     136  1660.9   141.7 1662.01   145.5 1662.93
#Mann= 3 ,-1,0
       0      .1       0      19    .045       0    56.2      .1       0
Bank Sta=19,56.2
XS Rating Curve= 0 ,0
Exp/Cntr(USF)=0,0
Exp/Cntr=0.3,0.1

Type RM Length L Ch R = 1 ,14364   ,68,79.2,95.9
XS GIS Cut Line= 3
 2158278.3009609627142.6353138762158357.47176444627246.208077411
2158378.07786399627279.828555627
#Sta/Elev= 30
       0 1660.48       6 1655.28    11.7 1651.05    13.3 1650.16    18.3 1648.31
    28.4 1646.65    34.5 1645.08    37.4 1644.51    43.5 1643.85    55.8  1643.6
    63.1 1643.93    68.7 1644.47    71.6 1645.01    75.5 1645.39    78.7 1645.33
    88.8 1644.69    93.8 1644.91    97.3 1645.59   103.9 1647.46     114 1651.75
     124 1656.39   128.7 1658.17   138.5 1660.42   143.2 1661.84   147.9 1662.78
   151.9 1663.26   154.9 1663.96   157.8 1664.84   166.7 1668.57   169.8 1669.69
#Mann= 3 ,-1,0
       0      .1       0    37.4    .045       0    68.7      .1       0
Bank Sta=37.4,68.7
XS Rating Curve= 0 ,0
Exp/Cntr(USF)=0,0
Exp/Cntr=0.3,0.1

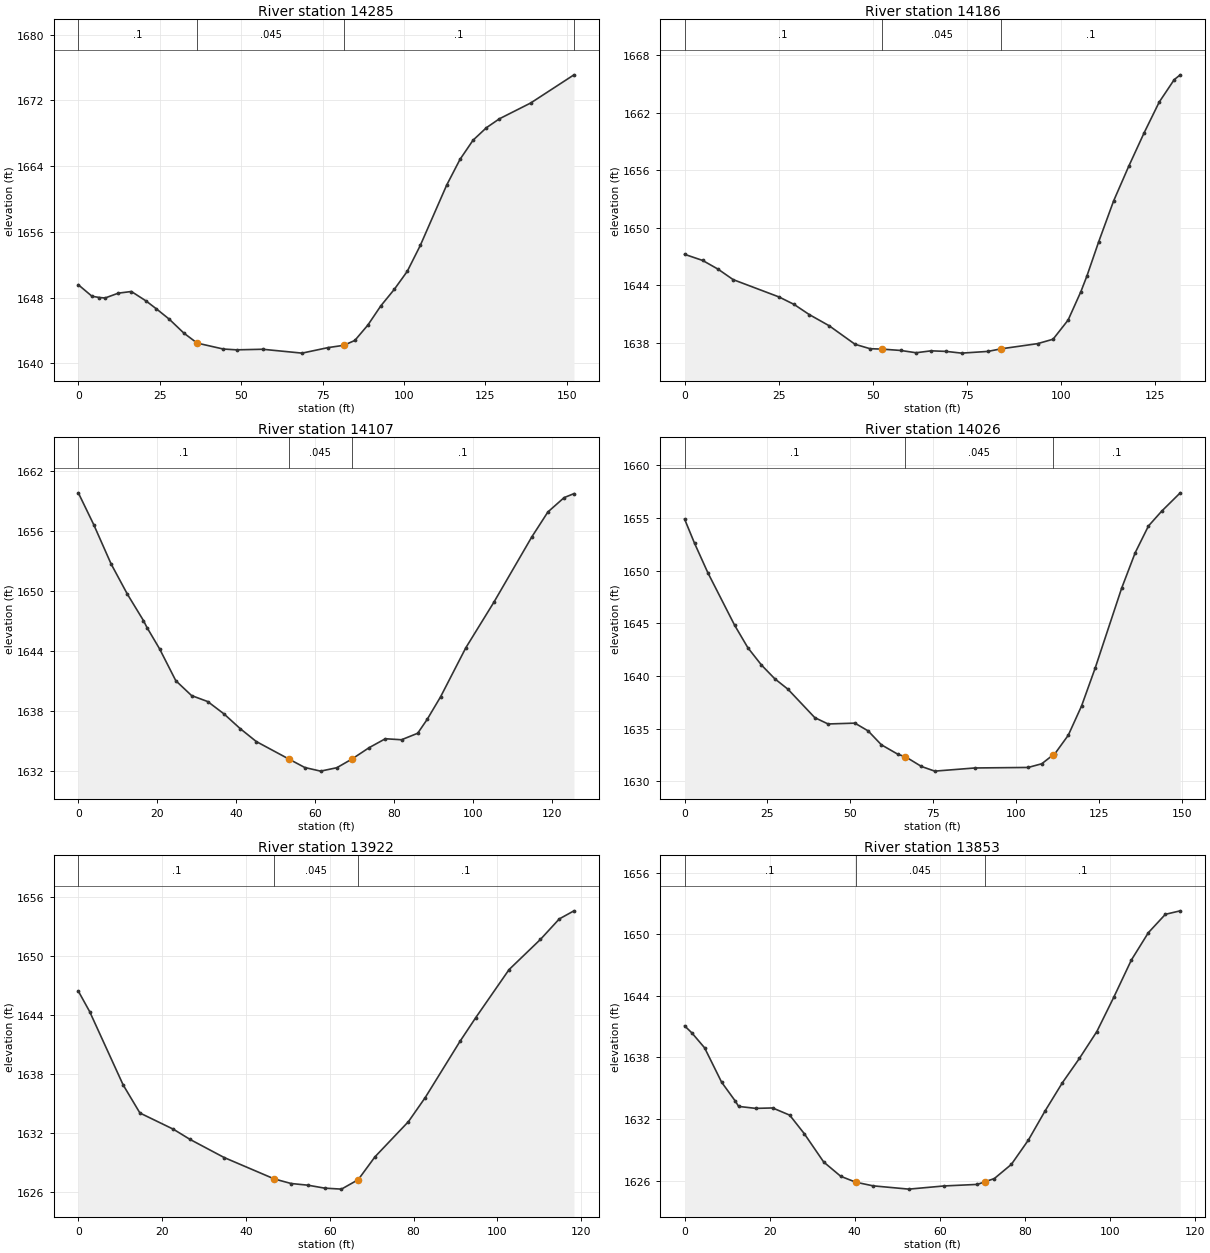
Type RM Length L Ch R = 1 ,14285   ,93.5,98.8,107.9
XS GIS Cut Line= 3
 2158237.0887618627173.0021974262158250.64540624627277.659492516
2158243.59595113627323.752083618
#Sta/Elev= 30
       0 1649.55     4.2 1648.15     6.5    1648     8.2 1647.94    12.3 1648.53
    16.3 1648.73    20.8 1647.58      24 1646.61    27.9 1645.37    32.4 1643.67
    36.5 1642.45    44.5 1641.73    48.6 1641.63    56.6  1641.7    68.7 1641.23
    76.8 1641.91    81.5 1642.18    84.9 1642.77    88.9 1644.64    92.9 1646.99
      97 1648.98     101 1651.18     105 1654.33   113.1 1661.67   117.2 1664.81
   121.2 1667.14   125.3 1668.66   129.3 1669.75   138.9 1671.67   152.2  1675.1
#Mann= 4 ,-1,0
       0      .1       0    36.5    .045       0    81.5      .1       0
  152.16     .08       0
Bank Sta=36.5,81.5
XS Rating Curve= 0 ,0
Exp/Cntr(USF)=0,0
Exp/Cntr=0.3,0.1

Type RM Length L Ch R = 1 ,14186   ,78.1,79.1,81.1
XS GIS Cut Line= 3
2158154.98475443627156.392994326 2158137.9863491627270.638090632
2158137.19572559627286.845872461
#Sta/Elev= 30
       0 1647.25     4.8 1646.61     8.9  1645.7    12.9 1644.61    25.1  1642.8
    29.1 1642.02    33.1 1640.97    38.4  1639.8    45.3 1637.86    49.3  1637.4
    52.4 1637.36    57.4 1637.22    61.5 1636.98    65.5 1637.18    69.5 1637.12
    73.6 1636.94    80.6 1637.12    84.1 1637.39    93.8 1637.93    97.9 1638.39
   101.9 1640.39   105.3 1643.36   106.9 1644.99     110 1648.53     114 1652.83
     118 1656.43   122.1 1659.93   126.1 1663.13   130.1 1665.48   131.7 1665.98
#Mann= 3 ,-1,0
       0      .1       0    52.4    .045       0    84.1      .1       0
Bank Sta=52.4,84.1
XS Rating Curve= 0 ,0
Exp/Cntr(USF)=0,0
Exp/Cntr=0.3,0.1

Type RM Length L Ch R = 1 ,14107   ,82.5,81.7,78.8
XS GIS Cut Line= 3
2158080.64630885627145.0397096322158059.22346331627247.467689859
2158053.19828801 627267.55160755
#Sta/Elev= 30
       0 1659.82     3.9 1656.64     8.3 1652.71    12.4  1649.7    16.5 1647.04
    17.4 1646.34    20.6  1644.2    24.7 1641.02    28.7 1639.53    32.8 1638.93
    36.9  1637.7      41 1636.23    45.1 1634.93    53.3 1633.19    57.4 1632.33
    61.4 1631.97    65.5 1632.31    69.3 1633.17    73.7 1634.32    77.8 1635.21
    81.9 1635.11      86 1635.76    88.4 1637.15    91.8 1639.41    98.2 1644.32
   105.3 1648.87   114.9  1655.4     119 1657.91   123.1 1659.34   125.6 1659.74
#Mann= 3 ,-1,0
       0      .1       0    53.3    .045       0    69.3      .1       0
Bank Sta=53.3,69.3
XS Rating Curve= 0 ,0
Exp/Cntr(USF)=0,0
Exp/Cntr=0.3,0.1

Type RM Length L Ch R = 1 ,14026   ,103.3,103.3,102.5
XS GIS Cut Line= 3
2158000.98010201627102.1940185562157984.24350393627241.442514551
2157984.24350393627250.815009474
#Sta/Elev= 30
       0  1654.9       3 1652.61       7 1649.82    15.1 1644.82    19.1 1642.68
    23.2 1641.04    27.2 1639.74    31.2 1638.74    39.3 1636.04    43.3 1635.44
    51.4 1635.52    55.4 1634.78    59.4 1633.46    64.5 1632.54    66.6 1632.34
    71.5  1631.4    75.5 1630.96    87.6 1631.26   103.7 1631.31   107.8 1631.66
   111.3 1632.52   111.8 1632.63   115.8 1634.37   119.8 1637.14   123.9 1640.73
   131.9 1648.33     136 1651.71     140 1654.25     144 1655.66   149.6  1657.4
#Mann= 3 ,-1,0
       0      .1       0    66.6    .045       0   111.3      .1       0
Bank Sta=66.6,111.3
XS Rating Curve= 0 ,0
Exp/Cntr(USF)=0,0
Exp/Cntr=0.3,0.1

Type RM Length L Ch R = 1 ,13922   ,69.8,69.5,68.7
XS GIS Cut Line= 3
2157892.89979655627118.4803667892157888.01940456627200.470952373
2157887.53136536627236.585853166
#Sta/Elev= 22
       0 1646.44     2.7 1644.36    10.7 1636.91    14.7 1634.06    22.7 1632.41
    26.7 1631.37    34.8 1629.54    46.8 1627.36    50.8  1626.9    54.8 1626.73
    58.8 1626.43    62.8 1626.33    66.8 1627.29    70.8 1629.61    78.8 1633.19
    82.8 1635.63    91.1 1641.34    94.8 1643.71   102.8 1648.62   110.3 1651.69
   114.8 1653.77   118.3 1654.59
#Mann= 3 ,-1,0
       0      .1       0    46.8    .045       0    66.8      .1       0
Bank Sta=46.8,66.8
XS Rating Curve= 0 ,0
Exp/Cntr(USF)=0,0
Exp/Cntr=0.3,0.1

Type RM Length L Ch R = 1 ,13853   ,67.5,64.7,62.7
XS GIS Cut Line= 3
2157821.15803417627120.4325235882157820.18195577627206.815461971
2157824.57430857627236.585853166
#Sta/Elev= 30
       0 1641.08     1.7  1640.4     4.7 1638.94     8.7 1635.59    11.9 1633.76
    12.7 1633.23    16.7 1633.04    20.7 1633.08    24.7 1632.38    28.1 1630.59
    32.7 1627.81    36.7 1626.42    40.2 1625.85    44.3 1625.49    52.7 1625.17
      61 1625.48    68.8 1625.63    70.61625.886    72.8  1626.2    76.8 1627.58
    80.8 1629.95    84.7 1632.77    88.8 1635.54    92.8 1637.91    96.9 1640.53
   100.9 1643.89     105 1647.49     109 1650.16     113 1651.95   116.5 1652.29
#Mann= 3 ,-1,0
       0      .1       0    40.2    .045       0    70.6      .1       0
Bank Sta=40.2,70.6
XS Rating Curve= 0 ,0
Exp/Cntr(USF)=0,0
Exp/Cntr=0.3,0.1

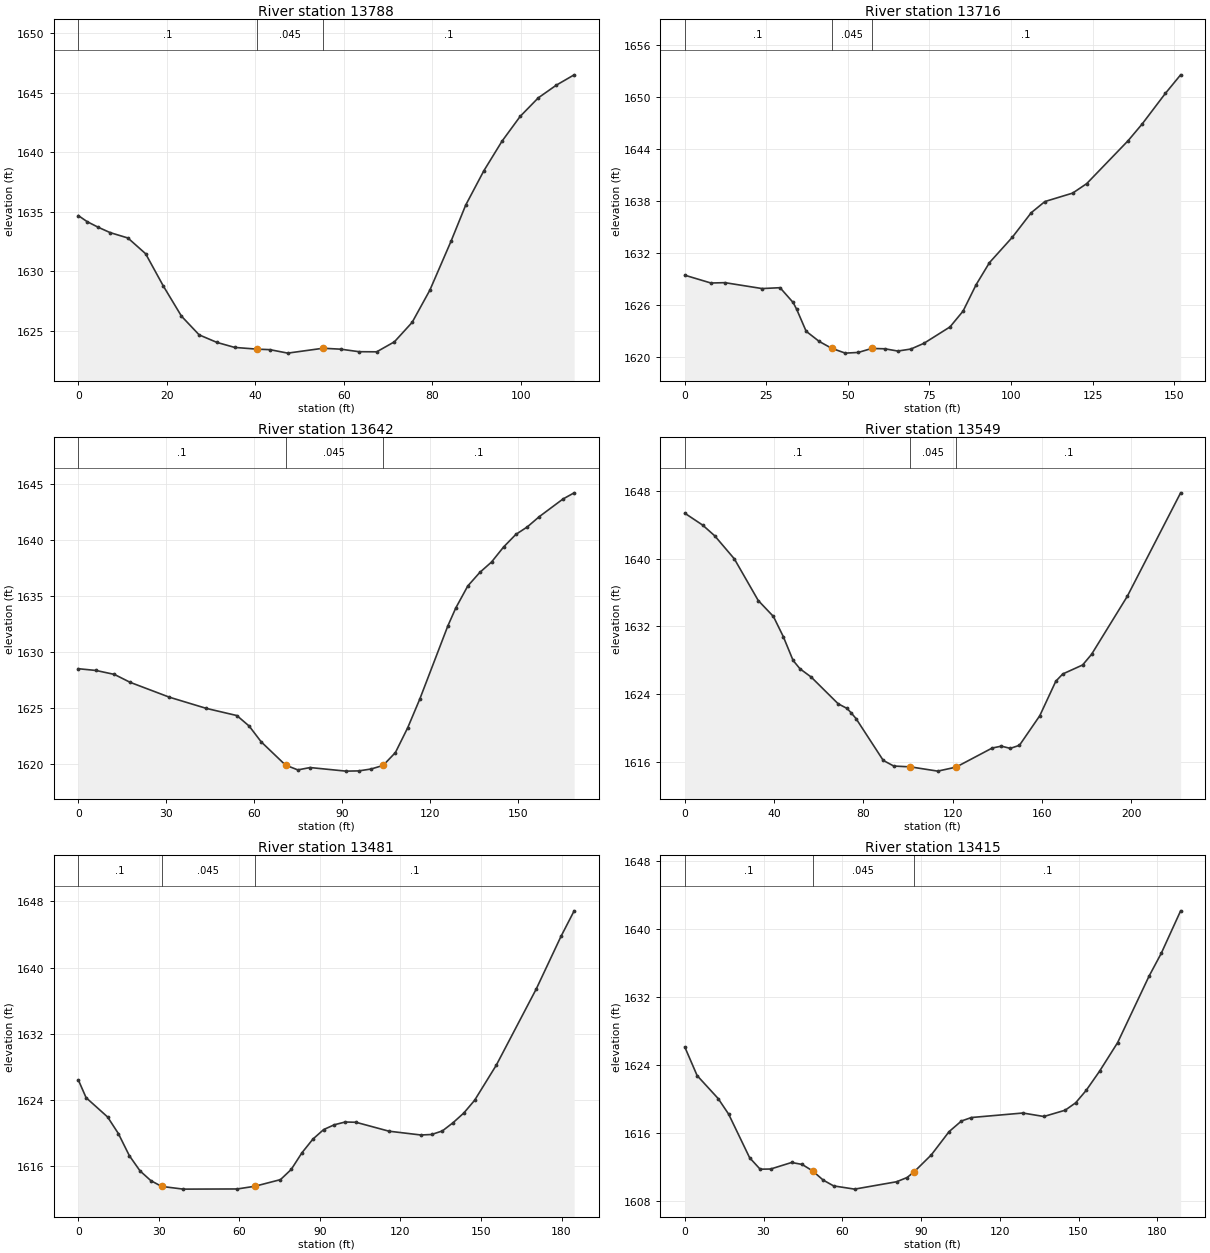
Type RM Length L Ch R = 1 ,13788   ,70.9,72.4,73.8
XS GIS Cut Line= 3
2157753.17772178627137.991558094 2157759.3270157627221.446261278
2157765.47630962627249.118083912
#Sta/Elev= 29
       0 1634.68       2 1634.17     4.5  1633.7     7.2 1633.25    11.2  1632.8
    15.2 1631.48    19.2 1628.77    23.3 1626.24    27.3 1624.67    31.3 1624.04
    35.3 1623.62    40.31623.476    43.3 1623.43    47.3 1623.14    55.3 1623.55
    59.3 1623.47    63.4 1623.26    67.4 1623.25    71.4 1624.09    75.4 1625.72
    79.4 1628.42    84.2 1632.54    87.5 1635.56    91.6 1638.44    95.7 1640.92
    99.8    1643   103.9 1644.56     108 1645.63     112 1646.49
#Mann= 3 ,-1,0
       0      .1       0    40.3    .045       0    55.3      .1       0
Bank Sta=40.3,55.3
XS Rating Curve= 0 ,0
Exp/Cntr(USF)=0,0
Exp/Cntr=0.3,0.1

Type RM Length L Ch R = 1 ,13716   ,70.3,73.9,83.1
XS GIS Cut Line= 4
2157694.75942955627137.5523228142157685.53548867627163.467204329
2157682.46084171627226.7170846372157703.10489987627284.256906306
#Sta/Elev= 30
       0 1629.44       8 1628.54    12.3 1628.58    23.7  1627.9    29.2    1628
    33.2  1626.3    34.3 1625.51    37.2 1622.98    41.2 1621.81      451621.021
    49.2 1620.46    53.2 1620.54    57.3    1621    61.3 1620.96    65.3  1620.7
    69.3 1620.93    73.3 1621.59    81.3 1623.48    85.3  1625.3    89.3 1628.34
    93.4 1630.89   100.4 1633.81   106.2 1636.64   110.4 1637.93   118.9  1638.9
   123.2 1639.99   135.9 1644.94   140.2 1646.86   147.3 1650.38     152 1652.53
#Mann= 3 ,-1,0
       0      .1       0      45    .045       0    57.3      .1       0
Bank Sta=45,57.3
XS Rating Curve= 0 ,0
Exp/Cntr(USF)=0,0
Exp/Cntr=0.3,0.1

Type RM Length L Ch R = 1 ,13642   ,92.7,92.6,92
XS GIS Cut Line= 4
2157657.78786168627125.3129372172157619.32513083627157.205274651
2157599.44205231627226.4947906872157607.87729774627272.888640554
#Sta/Elev= 30
       0 1628.52     6.1 1628.36    12.3 1628.01    17.7  1627.3    31.1 1625.97
    43.7 1624.97    54.1 1624.33    58.3 1623.39    62.4 1621.98    70.7  1619.9
    74.9 1619.47    79.1 1619.68    91.3 1619.36    95.7 1619.38    99.9 1619.55
     104 1619.87   108.2 1621.02   112.4 1623.24   116.5 1625.79   126.1 1632.35
   128.8 1633.95   132.9 1635.92     137 1637.13     141 1638.06   145.1  1639.4
   149.3 1640.53   153.2  1641.2   157.3 1642.12   165.4  1643.7   169.2 1644.25
#Mann= 3 ,-1,0
       0      .1       0    70.7    .045       0     104      .1       0
Bank Sta=70.7,104
XS Rating Curve= 0 ,0
Exp/Cntr(USF)=0,0
Exp/Cntr=0.3,0.1

Type RM Length L Ch R = 1 ,13549   ,70.9,68.5,66.9
XS GIS Cut Line= 5
2157551.48027107627048.989993037 2157531.0366276 627094.01654106
 2157532.5626064627116.8366000912157515.08959801 627213.23940501
2157513.88456295627265.055912655
#Sta/Elev= 30
       0 1645.34       8 1643.94    13.4 1642.68    22.2 1639.96    32.9 1635.06
    39.7 1633.18    44.1 1630.82    48.5 1628.01    51.6 1627.02    56.6 1626.05
    68.7  1622.9    72.7 1622.35    74.5 1621.84    76.7 1621.16    88.9 1616.23
    93.6 1615.57   101.1 1615.47   113.3 1614.97   121.5 1615.44   137.7 1617.69
   141.8 1617.91   145.8 1617.65   149.9 1618.01     159 1621.49   166.2 1625.56
   169.3 1626.41   178.2 1627.47   182.2 1628.72   198.2 1635.55   222.1 1647.74
#Mann= 3 ,-1,0
       0      .1       0   101.1    .045       0   121.5      .1       0
Bank Sta=101.1,121.5
XS Rating Curve= 0 ,0
Exp/Cntr(USF)=0,0
Exp/Cntr=0.3,0.1

Type RM Length L Ch R = 1 ,13481   ,70.3,66.1,65.4
XS GIS Cut Line= 3
2157464.47812542627090.325828738 2157454.2353274627184.921081065
2157462.67057283627274.093675616
#Sta/Elev= 30
       0  1626.4     2.9 1624.25    10.9 1621.92    14.9 1619.92      19 1617.24
      23 1615.39      27 1614.22      31 1613.52    39.1 1613.19    59.2 1613.21
    65.81613.539    75.3 1614.34    79.3 1615.57    83.3 1617.59    87.4 1619.25
    91.4  1620.4    95.4 1620.98    99.4 1621.31   103.4 1621.28   115.7  1620.2
   127.6 1619.74   131.6  1619.8   135.6 1620.23   139.6 1621.23   143.6  1622.4
   147.6 1623.93   155.7 1628.19   170.6 1637.42   179.8 1643.77   184.7 1646.86
#Mann= 3 ,-1,0
       0      .1       0      31    .045       0    65.8      .1       0
Bank Sta=31,65.8
XS Rating Curve= 0 ,0
Exp/Cntr(USF)=0,0
Exp/Cntr=0.3,0.1

Type RM Length L Ch R = 1 ,13415   ,87,91.3,79.3
XS GIS Cut Line= 4
 2157391.5735042627088.5182761462157392.77853927627101.773661822
2157395.18860939 627189.13870378 2157401.2137847 627277.10626327
#Sta/Elev= 30
       0 1626.11     4.7 1622.74    12.7 1620.04    16.7  1618.2    24.7 1613.06
    28.7 1611.71    32.7 1611.73    40.7  1612.5    44.7 1612.27    48.7 1611.51
    52.7 1610.43    56.7 1609.74    64.7 1609.36    80.7 1610.23    84.7 1610.73
    87.4 1611.41    93.9 1613.39   100.7 1616.14   105.4 1617.39   109.2  1617.8
   128.8 1618.33   136.8 1617.92   144.9 1618.66   148.9 1619.53   152.9 1620.99
     158 1623.25   164.9 1626.63   176.9 1634.48   181.5 1637.14   188.9 1642.16
#Mann= 3 ,-1,0
       0      .1       0    48.7    .045       0    87.4      .1       0
Bank Sta=48.7,87.4
XS Rating Curve= 0 ,0
Exp/Cntr(USF)=0,0
Exp/Cntr=0.3,0.1

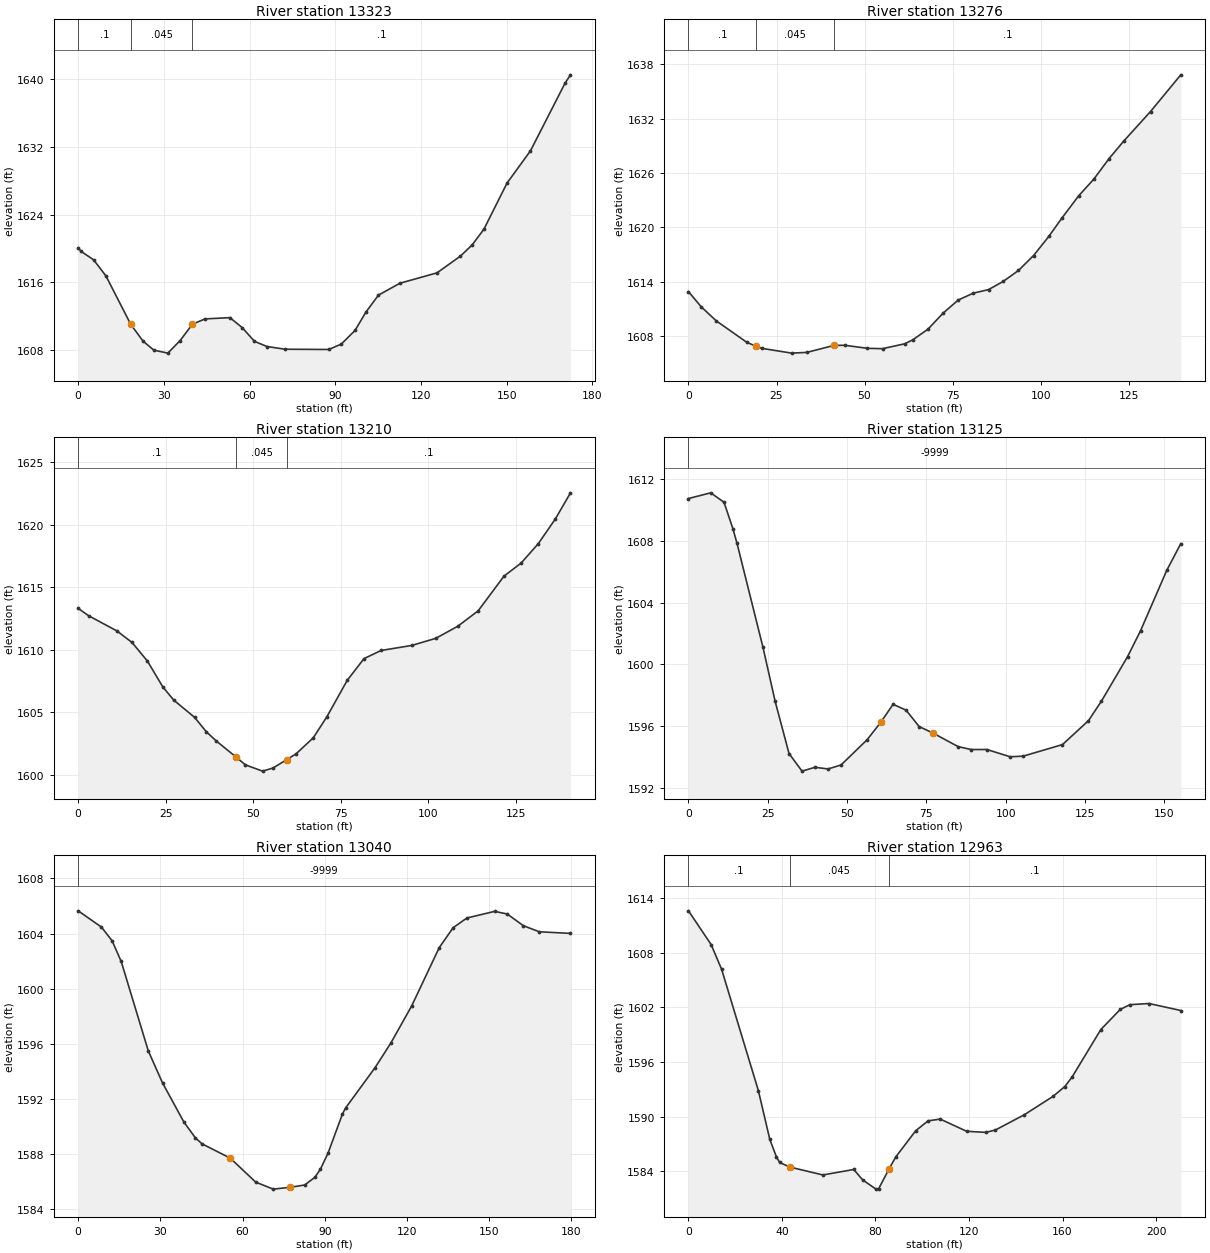
Type RM Length L Ch R = 1 ,13323   ,47.9,47.7,49.2
XS GIS Cut Line= 3
2157302.40090965 627116.234082562157343.97461928627215.649475133
2157356.62748742627278.913815862
#Sta/Elev= 30
       0 1620.07       1 1619.66     5.4 1618.66     9.7 1616.77    18.4 1611.04
    22.7 1609.06    26.5 1607.99    31.4 1607.64    35.7 1609.13      40 1611.06
    44.4 1611.68    53.1 1611.83    57.4 1610.66    61.7 1609.03    66.1 1608.42
    72.4  1608.1    87.7 1608.07    92.1 1608.71    96.9 1610.32   100.7 1612.48
   105.1 1614.49   112.6 1615.89   125.6 1617.12   133.8  1619.1   137.9 1620.42
     142 1622.27   150.1 1627.72   158.3 1631.53   170.4 1639.52   172.3  1640.5
#Mann= 3 ,-1,0
       0      .1       0    18.4    .045       0      40      .1       0
Bank Sta=18.4,40
XS Rating Curve= 0 ,0
Exp/Cntr(USF)=0,0
Exp/Cntr=0.3,0.1

Type RM Length L Ch R = 1 ,13276   ,67.7,65.7,61.5
XS GIS Cut Line= 3
2157265.86026648627145.8468814512157297.48520664627226.885790595
2157316.06485898627276.299759585
#Sta/Elev= 30
       0 1612.91     3.6 1611.24     7.9 1609.68    16.5 1607.33    19.2 1606.87
    20.8 1606.65    29.3 1606.12    33.6  1606.2    41.4 1606.98    44.5 1606.98
    50.8 1606.65    55.1 1606.61    61.4 1607.15    63.7 1607.59      68 1608.76
    72.3 1610.53    76.6 1611.98    80.9 1612.74    85.2 1613.13    89.4 1614.04
    93.7 1615.24      98 1616.89   102.3 1618.99     106    1621   110.8 1623.48
   115.1 1625.32   119.4 1627.57   123.6 1629.52   131.2 1632.78   139.8 1636.83
#Mann= 3 ,-1,0
       0      .1       0    19.2    .045       0    41.4      .1       0
Bank Sta=19.2,41.4
XS Rating Curve= 0 ,0
Exp/Cntr(USF)=0,0
Exp/Cntr=0.3,0.1

Type RM Length L Ch R = 1 ,13210   ,64.6,84.8,84.1
XS GIS Cut Line= 4
2157218.06279178627155.0713645932157205.77288019 627182.61087438
2157242.53687312627236.373272641 2157279.6961778627262.463848268
#Sta/Elev= 30
       0 1613.32       3 1612.73    11.1 1611.51    15.4 1610.59    19.8  1609.1
    24.2 1607.03    27.3 1605.98    33.3 1604.59    36.6 1603.45    39.5  1602.7
    45.2  1601.4    47.8 1600.79    52.7 1600.29    55.7 1600.54    59.6 1601.21
    62.3 1601.68    67.2 1602.96    71.1 1604.65    76.9 1607.56    81.7  1609.3
    86.6 1609.95    95.3 1610.35   102.2 1610.92   108.5 1611.89   114.3 1613.12
   121.7  1615.9   126.6 1616.95   131.5  1618.5   136.4 1620.49   140.7 1622.57
#Mann= 3 ,-1,0
       0      .1       0    45.2    .045       0    59.6      .1       0
Bank Sta=45.2,59.6
XS Rating Curve= 0 ,0
Exp/Cntr(USF)=0,0
Exp/Cntr=0.3,0.1

Type RM Length L Ch R = 1 ,13125   ,70.9,85.2,83.3
XS GIS Cut Line= 2
 2157162.0636562627130.3102445722157127.31630435627281.563423228
#Sta/Elev= 30
       0 1610.74       7 1611.11    11.2  1610.5      14 1608.79    15.3 1607.84
    23.5 1601.09    27.3 1597.62    31.7 1594.22    35.8 1593.08    39.9 1593.33
      44 1593.22    48.1 1593.48    56.3 1595.11    60.71596.264    64.5 1597.41
    68.6 1597.03    72.7 1595.97    77.21595.533      85 1594.67    89.1 1594.48
    94.1 1594.48   101.4 1594.01   105.5 1594.05   117.9  1594.8   126.1 1596.35
   130.2 1597.62   138.4 1600.49   142.5 1602.17   150.8  1606.1   155.2 1607.82
#Mann= 1 ,-1,0
       0   -9999       0
Bank Sta=60.7,77.2
XS Rating Curve= 0 ,0
Exp/Cntr(USF)=0,0
Exp/Cntr=0.3,0.1

Type RM Length L Ch R = 1 ,13040   ,66.5,76.9,71.9
XS GIS Cut Line= 2
2157115.73385373627120.7717558272157006.04123317627263.167766364
#Sta/Elev= 30
       0 1605.65     8.5 1604.47    12.4 1603.47    15.7 1601.98    25.6 1595.48
    30.8 1593.15    38.6 1590.31    42.8 1589.16    45.2 1588.73    55.51587.693
    64.8 1585.95    71.2 1585.44    77.41585.574    82.7 1585.74    86.4  1586.3
    88.4 1586.88    91.2 1588.05    96.4 1590.86    97.6 1591.33   108.4 1594.27
   114.1 1596.04   121.7 1598.73   131.8 1602.98   136.9 1604.43   141.9 1605.13
     152 1605.61   156.6 1605.42   162.5 1604.57   168.3 1604.13   179.7 1604.01
#Mann= 1 ,-1,0
       0   -9999       0
Bank Sta=55.5,77.4
XS Rating Curve= 0 ,0
Exp/Cntr(USF)=0,0
Exp/Cntr=0.3,0.1

Type RM Length L Ch R = 1 ,12963   ,70.2,70.9,70.8
XS GIS Cut Line= 4
2157084.69663629627081.991792988 2157063.7109507627093.216694586
2156995.87350191627151.7813985752156973.91173791627246.461003357
#Sta/Elev= 30
       0 1612.62     9.7 1608.91    14.2 1606.17    29.9 1592.85    34.8 1587.48
    37.6 1585.58      39 1584.95    43.3 1584.45    57.5 1583.58    70.7 1584.18
    74.5 1583.04    80.2 1582.02    81.3 1582.04    85.8 1584.24    88.7 1585.57
    97.2 1588.44   102.5 1589.53   107.7 1589.72     119 1588.38   127.2 1588.26
   131.3 1588.52   143.6 1590.19   155.9 1592.21     161  1593.3   164.1 1594.35
   176.4 1599.57   184.7 1601.78   188.8  1602.3     197 1602.43   210.6 1601.66
#Mann= 3 ,-1,0
       0      .1       0    43.3    .045       0    85.8      .1       0
Bank Sta=43.3,85.8
XS Rating Curve= 0 ,0
Exp/Cntr(USF)=0,0
Exp/Cntr=0.3,0.1

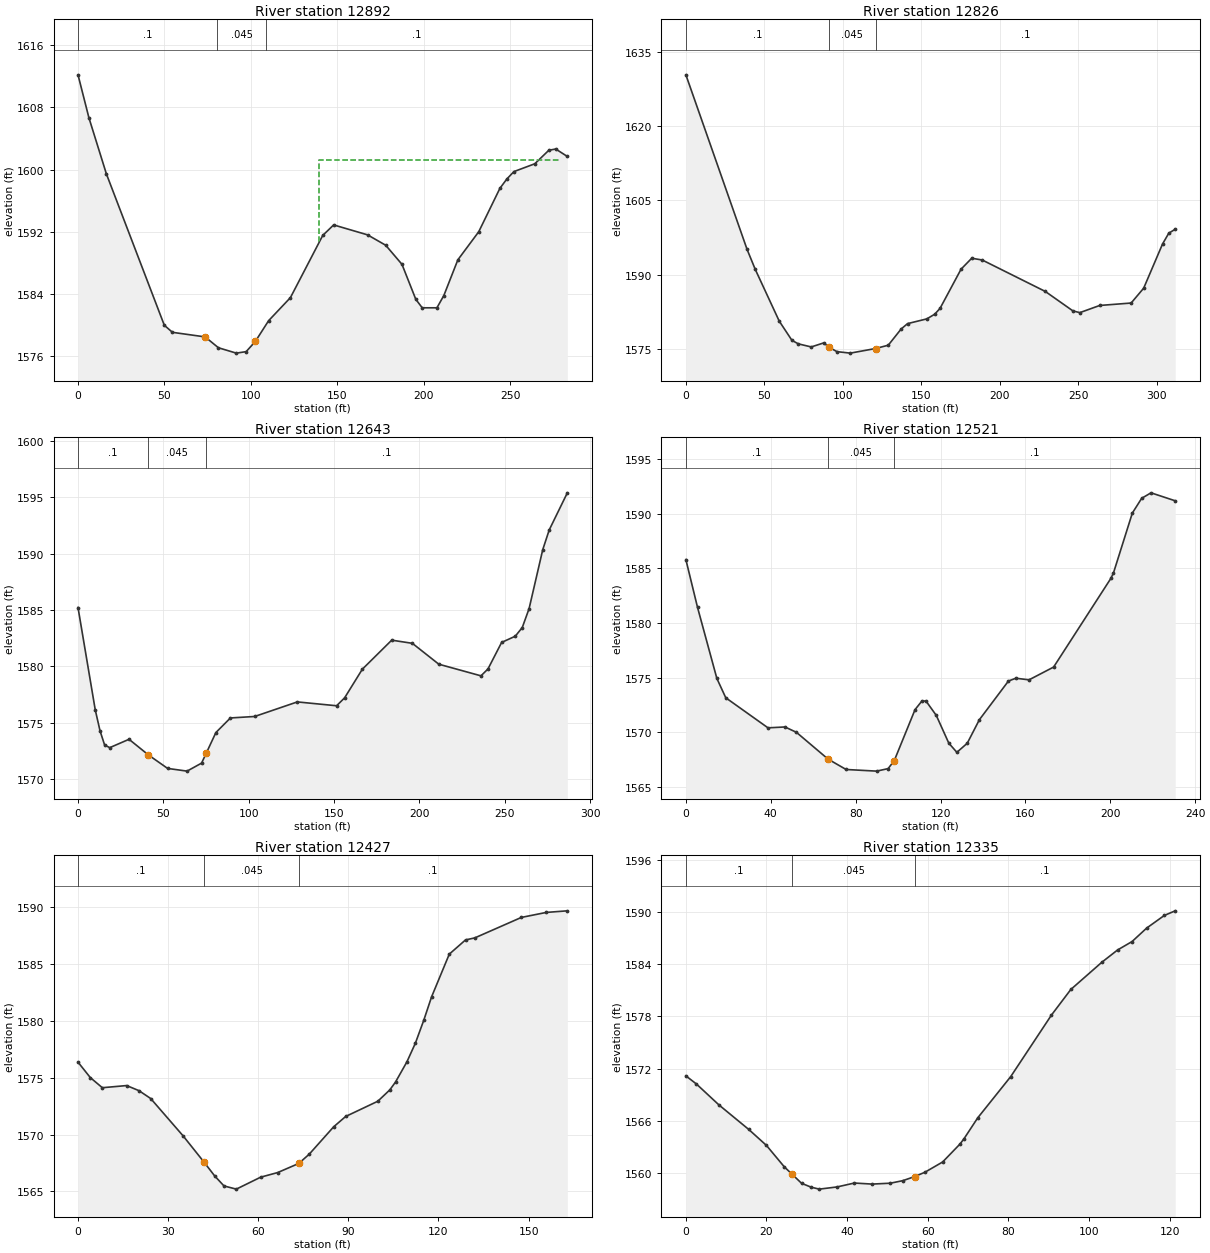
Type RM Length L Ch R = 1 ,12892   ,77.5,66.1,51.4
XS GIS Cut Line= 3
2157054.57424081627010.6805587922156934.25624957627110.775314949
2156952.91537204627235.804210911
#Sta/Elev= 30
       0 1612.21     6.3 1606.68    16.4 1599.45    49.9 1579.94    54.6 1579.03
    73.5 1578.44    81.2 1577.04    91.5 1576.35    97.2 1576.54   102.51577.849
   110.2 1580.53   122.8  1583.5   141.5 1591.52   147.8 1592.87   167.4 1591.59
   177.9 1590.25   187.3 1587.79   195.3 1583.28     199 1582.19   207.5 1582.19
   211.5 1583.77   219.6 1588.37   231.7    1592   243.9 1597.58   247.9 1598.78
     252 1599.74   264.1 1600.75   272.2 1602.49   276.2 1602.65   282.9 1601.69
#Mann= 3 ,-1,0
       0      .1       0    80.3    .045       0   108.8      .1       0
#XS Ineff= 1 ,-1
  139.44   278.2 1601.23
Permanent Ineff=
       F
Bank Sta=73.5,102.5
XS Rating Curve= 0 ,0
Exp/Cntr(USF)=0,0
Exp/Cntr=0.3,0.1

Type RM Length L Ch R = 1 ,12826   ,199,182.6,155.6
XS GIS Cut Line= 5
2156966.11140514626919.9987936682156954.73051845 626955.48038159
2156921.25732229627110.1265478152156895.81769322627169.039373044
2156895.14822929627221.257559042
#Sta/Elev= 30
       0 1630.36      39  1595.1    44.2 1591.07    59.5 1580.61    67.6 1576.72
    71.7 1576.01    79.9 1575.39    87.9 1576.21    91.3 1575.31    96.3 1574.44
   104.8 1574.14   120.9 1575.07     129 1575.74   137.2 1579.01   141.3  1580.1
   153.6 1581.06   158.6    1582     162 1583.18   175.4  1591.1   182.2 1593.31
   188.9 1592.95   229.1  1586.6   246.7 1582.67   251.1 1582.32   263.8 1583.77
   283.8 1584.26   291.8 1587.26   303.8 1596.17   307.8 1598.37   311.9 1599.17
#Mann= 3 ,-1,0
       0      .1       0    91.3    .045       0   120.9      .1       0
Bank Sta=91.3,120.9
XS Rating Curve= 0 ,0
Exp/Cntr(USF)=0,0
Exp/Cntr=0.3,0.1

Type RM Length L Ch R = 1 ,12643   ,120.9,122.5,115.3
XS GIS Cut Line= 4
2156729.21749528626973.8282639942156800.89699752627046.016558817
2156841.73429683627116.9797346612156853.11518352627219.407714888
#Sta/Elev= 30
       0 1585.22    10.1 1576.16    12.9  1574.3    15.6 1573.04    18.6 1572.81
    29.9 1573.55    41.2 1572.17    52.5 1570.97    63.9 1570.73    72.4 1571.44
    75.2 1572.34    80.8 1574.15    89.3 1575.44   103.5 1575.57   128.5 1576.86
   151.5 1576.52   156.2 1577.22   166.6 1579.76   183.8 1582.33   195.9 1582.05
   211.4  1580.2   236.1 1579.17   240.2 1579.78   248.2 1582.13   256.2 1582.68
   260.3 1583.45   264.3 1585.13   272.3 1590.35   276.1  1592.1   286.7 1595.38
#Mann= 3 ,-1,0
       0      .1       0    41.2    .045       0    75.2      .1       0
Bank Sta=41.2,75.2
XS Rating Curve= 0 ,0
Exp/Cntr(USF)=0,0
Exp/Cntr=0.3,0.1

Type RM Length L Ch R = 1 ,12521   ,101.3,94.5,78.1
XS GIS Cut Line= 4
2156661.24001278627057.5125714792156743.32310014627130.369013122
2156772.77951275627173.2147041972156802.23592537627235.474849041
#Sta/Elev= 30
       0 1585.79     5.5 1581.41    14.6 1574.92    18.8 1573.15    38.7  1570.4
    46.7 1570.48    52.1 1569.99      67 1567.54    75.5 1566.59    89.9 1566.44
    95.3 1566.67    98.2  1567.4     108 1572.07   111.3 1572.87   113.2 1572.84
     118 1571.54   123.9    1569   127.7 1568.16   132.6 1568.99   138.3 1571.14
     152 1574.68   155.5 1574.94   161.7 1574.79   173.3 1575.96   200.3 1584.08
   201.5 1584.57   210.4 1590.05   214.8  1591.4   219.2  1591.9   230.6 1591.17
#Mann= 3 ,-1,0
       0      .1       0      67    .045       0    98.2      .1       0
Bank Sta=67,98.2
XS Rating Curve= 0 ,0
Exp/Cntr(USF)=0,0
Exp/Cntr=0.3,0.1

Type RM Length L Ch R = 1 ,12427   ,84.5,91.5,95.8
XS GIS Cut Line= 3
2156616.12495476627177.2314877352156713.86668752627192.629157966
2156761.39862606627235.474849041
#Sta/Elev= 30
       0 1576.37     4.1 1575.01     8.1 1574.12    16.2 1574.31    20.3 1573.86
    24.2 1573.17      35 1569.88      42 1567.56    45.5 1566.36    48.6 1565.48
    52.7  1565.2    60.8 1566.25    66.5 1566.66    73.5 1567.46      77 1568.28
    85.1 1570.68    89.1 1571.59    99.8 1572.93   103.8 1573.93   105.7 1574.62
   109.5  1576.4   112.3 1578.03   115.1 1580.05   117.7 1582.11   123.6 1585.87
     129 1587.12   132.1  1587.3   147.6  1589.1   155.9 1589.54   162.9 1589.68
#Mann= 3 ,-1,0
       0      .1       0      42    .045       0    73.5      .1       0
Bank Sta=42,73.5
XS Rating Curve= 0 ,0
Exp/Cntr(USF)=0,0
Exp/Cntr=0.3,0.1

Type RM Length L Ch R = 1 ,12335   ,106.9,114,121.4
XS GIS Cut Line= 3
2156593.83625312627248.7055382022156666.17830372627280.330478356
2156702.15167315627302.863248216
#Sta/Elev= 30
       0 1571.17     2.6 1570.24     8.2 1567.83    15.6 1565.01      20 1563.17
    24.4 1560.72    26.4 1559.84    28.7 1558.82    31.1 1558.37    33.1 1558.15
    37.5  1558.4    41.8 1558.85    46.2 1558.73    50.7 1558.83    53.8 1559.12
    56.8  1559.6    59.3 1560.09    63.7 1561.27      68 1563.33      69 1563.94
    72.4 1566.34    80.6 1571.09    90.7 1578.16    95.5  1581.1   103.2 1584.23
   107.1 1585.64   110.7 1586.61   114.3 1588.15   118.7 1589.61   121.4 1590.14
#Mann= 3 ,-1,0
       0      .1       0    26.4    .045       0    56.8      .1       0
Bank Sta=26.4,56.8
XS Rating Curve= 0 ,0
Exp/Cntr(USF)=0,0
Exp/Cntr=0.3,0.1