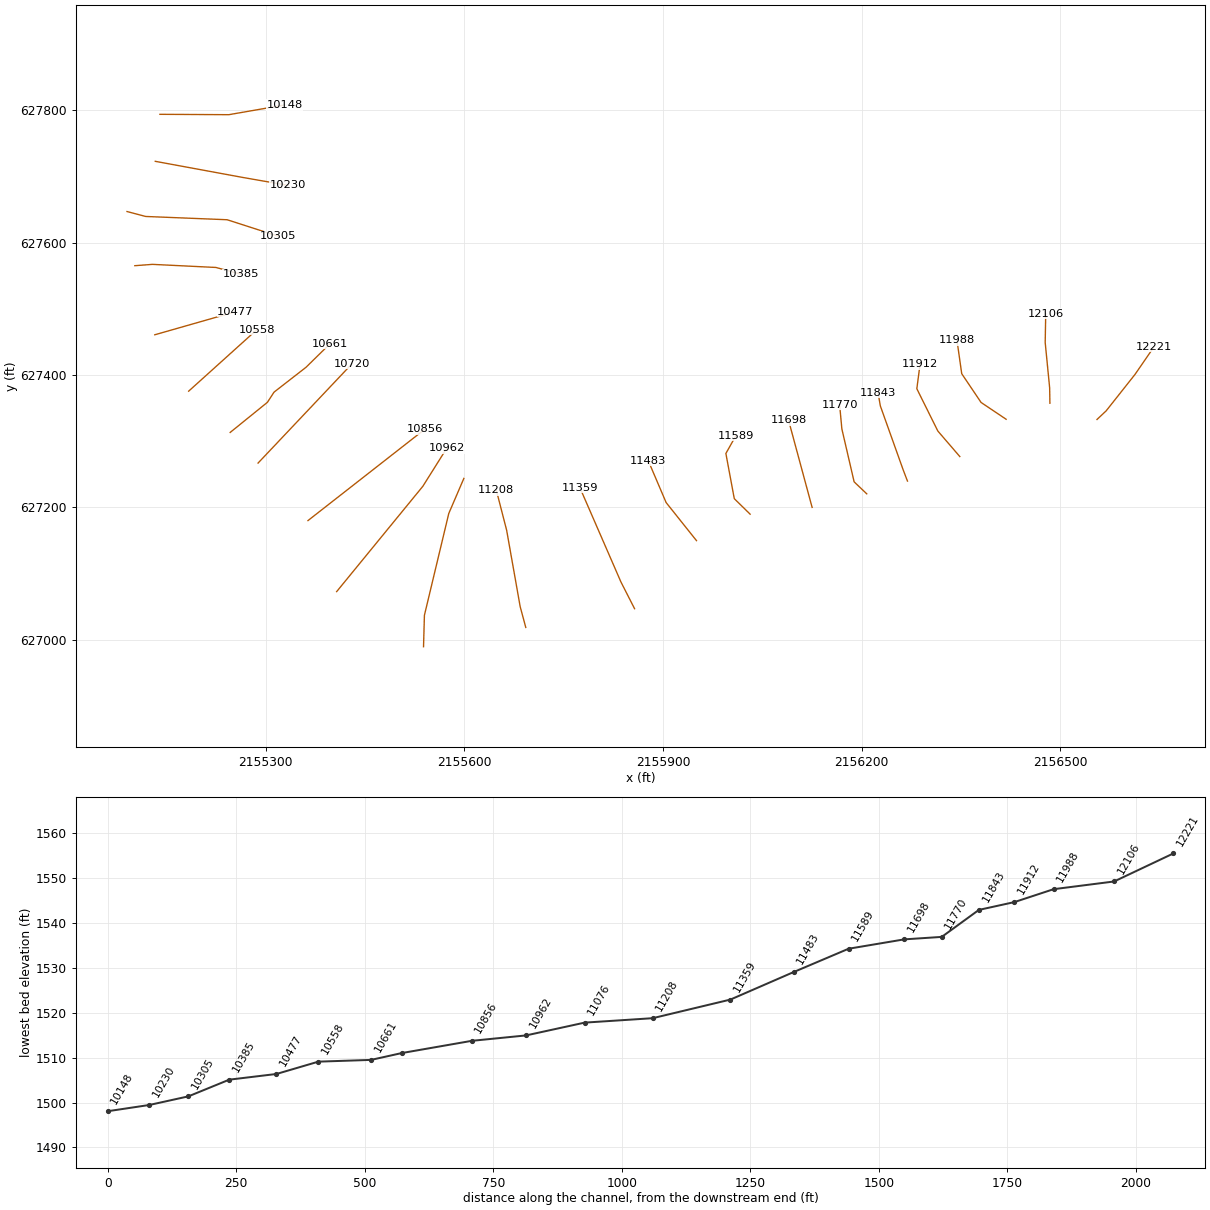
HEC-RAS study LFRFLIKANA.prj: LFRFLIKANA

--- LFRFLIKANA.g01 (geometry) --- (continued)

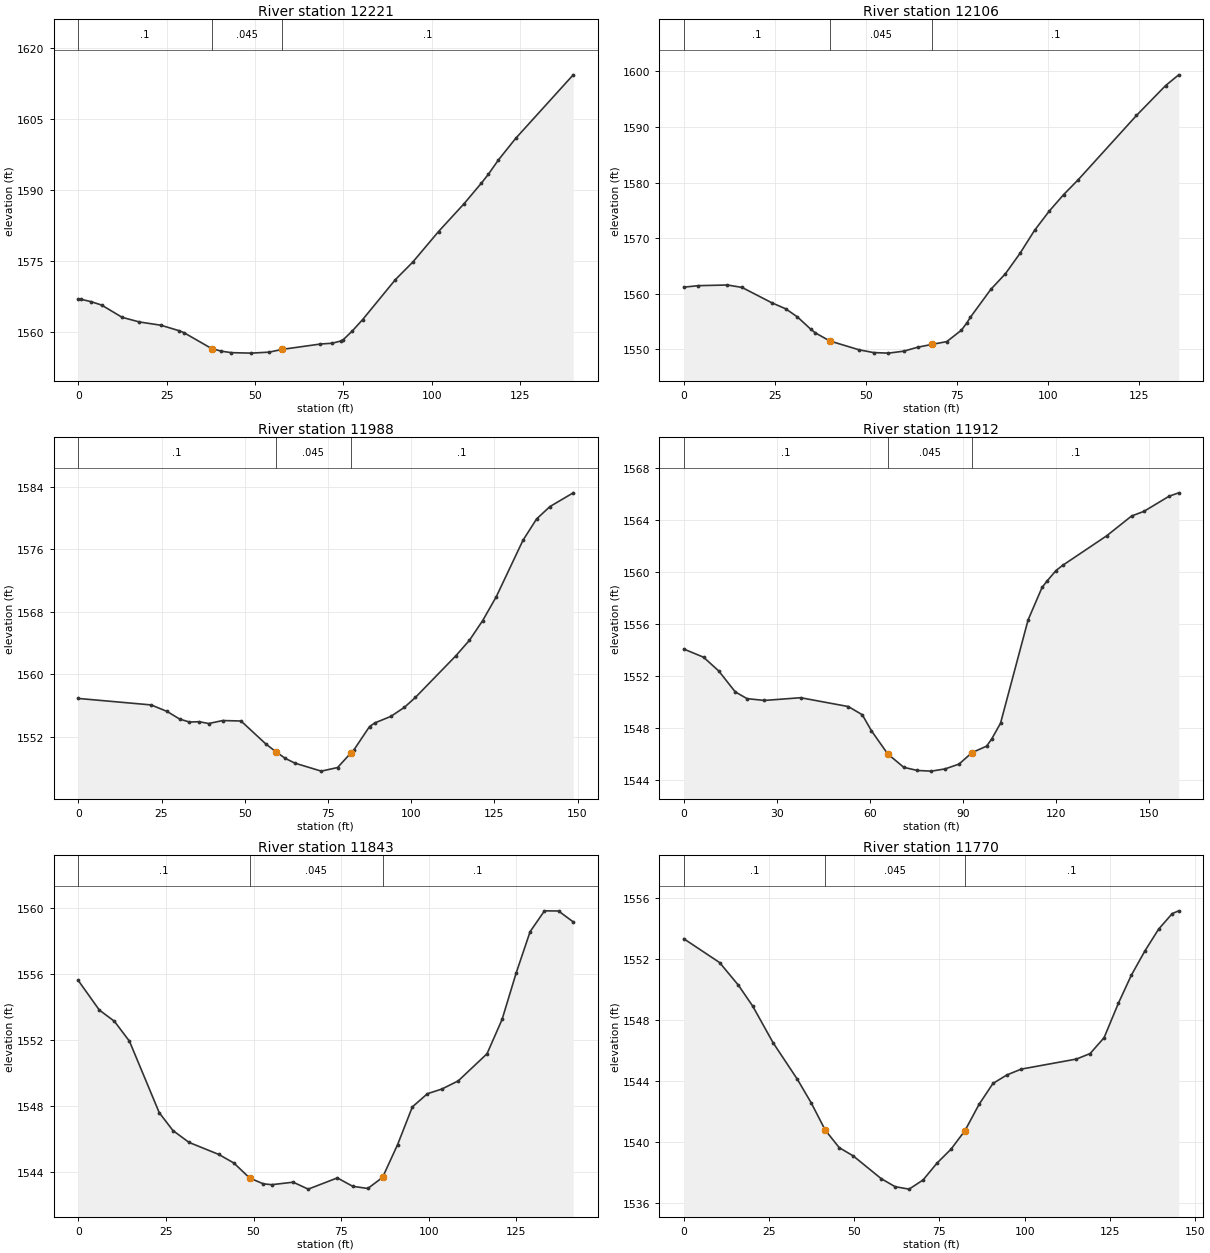
Type RM Length L Ch R = 1 ,12221   ,103.7,115.4,130.5
XS GIS Cut Line= 4
2156555.61276464  627332.67823272156569.44867596627345.723520513
2156612.93296867627400.6718540312156641.79072656627442.574899735
#Sta/Elev= 30
       0 1566.91      .8 1566.91     3.6 1566.42     6.6  1565.7    12.4 1563.11
    17.3 1562.13    23.4 1561.44    28.5 1560.29    29.9 1559.87    37.7 1556.53
    40.5 1555.97    43.3 1555.66    48.9 1555.56      54 1555.77    57.6 1556.34
    68.5 1557.48    71.8 1557.65    74.4 1558.14      75 1558.43    77.5 1560.23
    80.4 1562.61    89.7 1571.07    94.6 1574.75   101.9 1581.21   109.1 1587.06
     114  1591.4     116 1593.29   118.8 1596.27   123.7 1600.84     140 1614.26
#Mann= 3 ,-1,0
       0      .1       0    37.7    .045       0    57.6      .1       0
Bank Sta=37.7,57.6
XS Rating Curve= 0 ,0
Exp/Cntr(USF)=0,0
Exp/Cntr=0.3,0.1

Type RM Length L Ch R = 1 ,12106   ,112.7,117.7,129.3
XS GIS Cut Line= 4
 2156484.4566493627357.1875613192156484.06133755627380.510954683
2156477.34103776627448.8998877662156478.13166127627492.779492229
#Sta/Elev= 30
       0 1561.17       4 1561.44      12 1561.56      16 1561.12    24.2 1558.35
      28 1557.27    31.2 1555.82    34.8 1553.64    36.1 1552.95    40.1 1551.49
    48.1  1549.9    52.1  1549.4    56.2  1549.3    60.4 1549.65    64.2 1550.36
    68.2 1550.88    72.2 1551.37    76.2 1553.41    77.7 1554.72    78.7 1555.76
    84.3 1560.77    88.3 1563.58    92.3 1567.24    96.3 1571.38   100.3 1574.82
   104.3 1577.83   108.3  1580.5   124.3 1592.07   132.3 1597.45   135.9 1599.38
#Mann= 3 ,-1,0
       0      .1       0    40.1    .045       0    68.2      .1       0
Bank Sta=40.1,68.2
XS Rating Curve= 0 ,0
Exp/Cntr(USF)=0,0
Exp/Cntr=0.3,0.1

Type RM Length L Ch R = 1 ,11988   ,77.5,76.3,72.7
XS GIS Cut Line= 4
2156418.30781614627332.9856973962156380.48965854627358.373496575
 2156351.2365889627401.8577892872156344.12097736627452.062381781
#Sta/Elev= 30
       0 1556.89    21.9 1556.06    26.7 1555.22    30.5 1554.24    33.4 1553.87
    36.3 1553.91    39.2 1553.68    43.4 1554.06    48.9    1554    56.4 1551.04
    59.3 1550.09    62.2 1549.21    65.1  1548.6      73 1547.58    77.9 1548.04
    81.9 1549.91    82.7 1550.23    87.5 1553.29    89.1 1553.76    93.9 1554.59
      98 1555.76   101.3 1557.03   113.4 1562.34   117.5 1564.33   121.5 1566.87
   125.6 1569.94   133.6 1577.15   137.7 1579.89   141.7 1581.47   148.7 1583.23
#Mann= 3 ,-1,0
       0      .1       0    59.3    .045       0    81.9      .1       0
Bank Sta=59.3,81.9
XS Rating Curve= 0 ,0
Exp/Cntr(USF)=0,0
Exp/Cntr=0.3,0.1

Type RM Length L Ch R = 1 ,11912   ,71.6,69,64.4
XS GIS Cut Line= 4
2156348.33550485 627276.634397962156315.14883926627315.189494753
2156283.42629127 627379.122629942156288.30668326627416.213609133
#Sta/Elev= 30
       0 1554.08     6.4 1553.45    11.3 1552.39    16.6 1550.79    20.4 1550.27
      26 1550.13    37.7 1550.34    53.1 1549.66    57.6 1549.03    60.5 1547.82
    65.81546.024      71 1544.99    75.4 1544.75    79.9  1544.7    84.3 1544.87
    88.8 1545.24      93 1546.12    97.7 1546.62    99.3 1547.15   102.2 1548.38
   111.1 1556.32   115.6 1558.81   117.2  1559.3   120.1 1560.11   122.2  1560.5
   136.4 1562.77   144.5  1564.3   148.5 1564.66   156.6 1565.82   159.7 1566.08
#Mann= 3 ,-1,0
       0      .1       0    65.8    .045       0      93      .1       0
Bank Sta=65.8,93
XS Rating Curve= 0 ,0
Exp/Cntr(USF)=0,0
Exp/Cntr=0.3,0.1

Type RM Length L Ch R = 1 ,11843   ,75.1,72.2,69.1
XS GIS Cut Line= 4
2156269.27315447627239.5434187672156262.92864487627256.136751564
2156228.27786168627353.2565523452156224.86158728627373.266159541
#Sta/Elev= 30
       0  1555.6       6 1553.81    10.3 1553.13    14.6 1551.92    23.1 1547.59
      27 1546.51    31.6 1545.79    40.1 1545.06    44.4 1544.54    48.9 1543.63
    52.8 1543.28    55.2 1543.23    61.3 1543.38    65.6 1542.96    73.9 1543.64
    78.3 1543.13    82.6    1543    86.8 1543.67    91.1 1545.66    95.3 1547.94
    99.6 1548.74   103.8 1549.03   108.4 1549.52   116.6 1551.16   120.9 1553.24
   124.9 1556.04   128.9 1558.56     133 1559.82     137 1559.81   141.2 1559.15
#Mann= 3 ,-1,0
       0      .1       0    48.9    .045       0    86.8      .1       0
Bank Sta=48.9,86.8
XS Rating Curve= 0 ,0
Exp/Cntr(USF)=0,0
Exp/Cntr=0.3,0.1

Type RM Length L Ch R = 1 ,11770   ,71.7,72.9,73.6
XS GIS Cut Line= 4
2156207.76512752627220.2806520082156188.73159872627238.338102404
2156170.18610912627318.3765311892156166.76983472627354.979471182
#Sta/Elev= 30
       0 1553.36    10.5  1551.8      16 1550.32    20.2 1548.95    26.2 1546.54
    33.3 1544.15    37.4 1542.59    41.5 1540.81    45.6 1539.66    49.7 1539.12
    57.9 1537.63      62  1537.1    66.1 1536.94    70.2 1537.54    74.3 1538.65
    78.4 1539.56    82.5 1540.78    86.6 1542.49    90.7 1543.87    94.8 1544.43
      99 1544.81   115.2 1545.47   119.2 1545.83   123.3 1546.87   127.5 1549.13
   131.3 1550.97   135.3 1552.57   139.3 1553.99   143.3 1555.01   145.2 1555.19
#Mann= 3 ,-1,0
       0      .1       0    41.5    .045       0    82.5      .1       0
Bank Sta=41.5,82.5
XS Rating Curve= 0 ,0
Exp/Cntr(USF)=0,0
Exp/Cntr=0.3,0.1

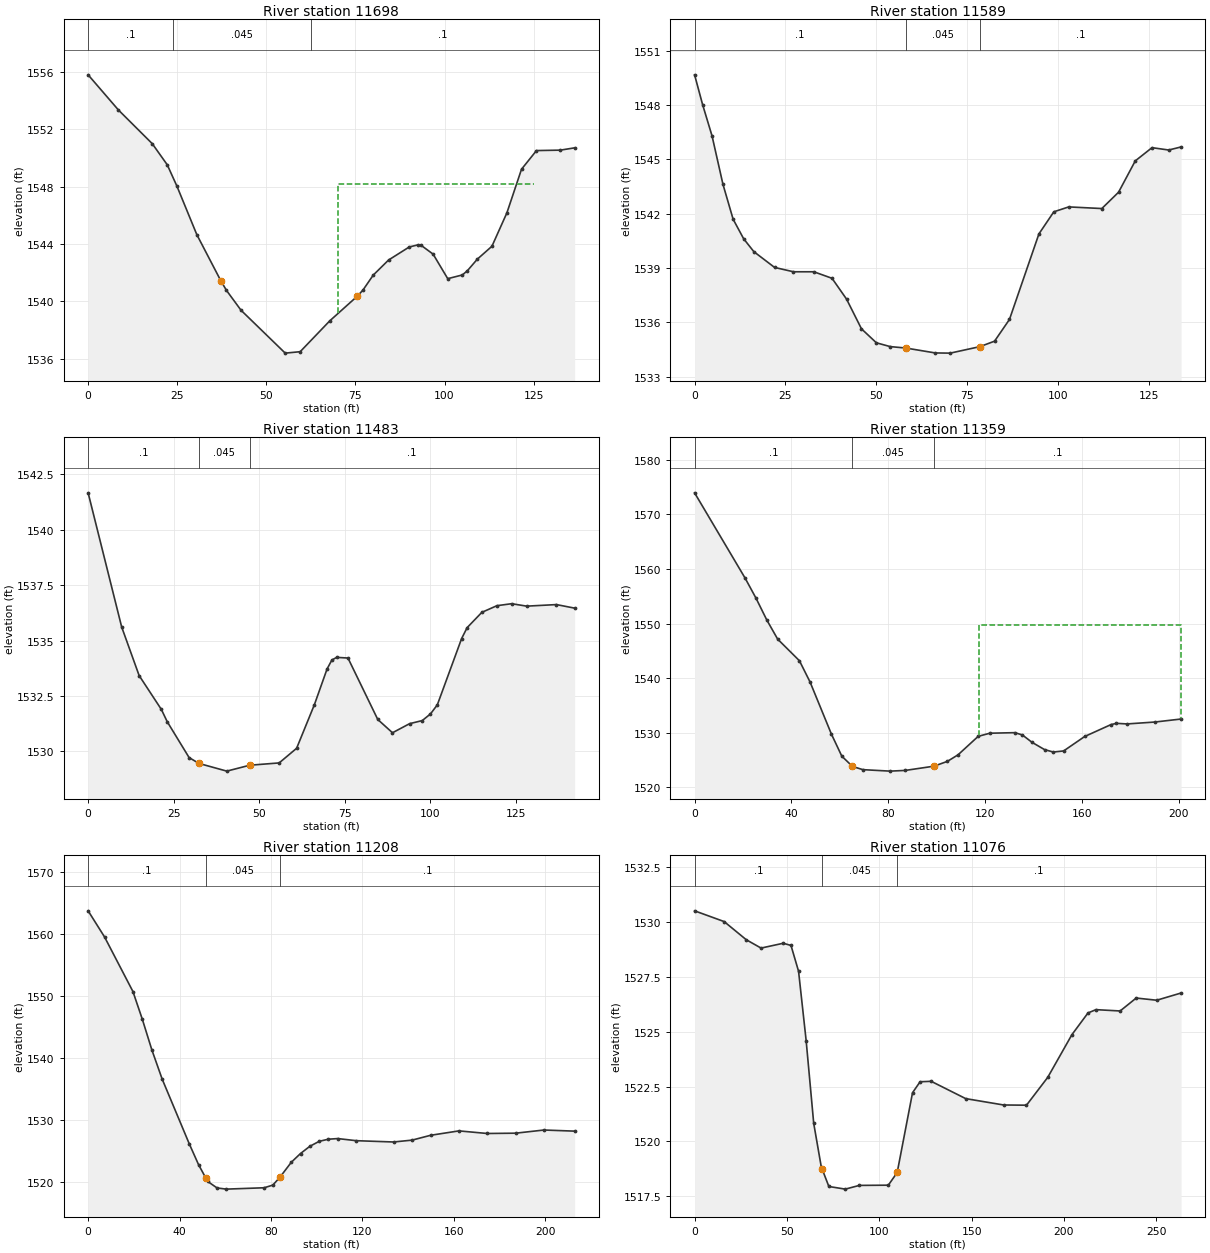
Type RM Length L Ch R = 1 ,11698   ,113.9,108.3,107.1
XS GIS Cut Line= 2
2156125.24644623627199.7676663062156089.64839802627331.503661354
#Sta/Elev= 30
       0 1555.79     8.5 1553.34      18 1550.99    22.2 1549.52    24.9 1548.04
    30.5 1544.65    37.2 1541.45    38.8 1540.77    42.9 1539.38    55.3 1536.39
    59.5 1536.49    67.8 1538.64    75.51540.353    77.1 1540.78      80 1541.83
    84.3 1542.88    90.1 1543.79    92.6 1543.94    93.4 1543.91    96.8 1543.29
   100.9 1541.58     105 1541.84   106.4 1542.13   109.2 1542.94   113.3 1543.84
   117.5 1546.17   121.6 1549.21   125.8 1550.51   132.5 1550.54   136.5  1550.7
#Mann= 3 ,-1,0
       0      .1       0    23.8    .045       0    62.5      .1       0
#XS Ineff= 1 ,-1
    70.2     125 1548.18
Permanent Ineff=
       F
Bank Sta=37.2,75.5
XS Rating Curve= 0 ,0
Exp/Cntr(USF)=0,0
Exp/Cntr=0.3,0.1

Type RM Length L Ch R = 1 ,11589   ,99.6,106.6,114.6
XS GIS Cut Line= 4
2156031.58297635627189.5341824132156007.66905555627212.960064009
2155994.98003636627281.2855519962156010.10925155627308.127707991
#Sta/Elev= 30
       0 1549.66     2.2 1548.02     4.8 1546.29     7.8 1543.62    10.6 1541.69
    13.5 1540.61    16.3  1539.9      22 1539.03    27.2 1538.79    32.8 1538.79
    37.8 1538.43    41.8 1537.28    45.9 1535.64      50 1534.87    53.8 1534.66
    58.11534.581    66.2 1534.31    70.3  1534.3    78.5 1534.66    82.5 1534.96
    86.6 1536.16    94.7 1540.88    98.8  1542.1   102.9 1542.37     112 1542.28
   116.6 1543.18   121.2 1544.91   125.8 1545.64   130.4 1545.51   133.8 1545.68
#Mann= 3 ,-1,0
       0      .1       0    58.1    .045       0    78.5      .1       0
Bank Sta=58.1,78.5
XS Rating Curve= 0 ,0
Exp/Cntr(USF)=0,0
Exp/Cntr=0.3,0.1

Type RM Length L Ch R = 1 ,11483   ,126.6,123.3,119
XS GIS Cut Line= 3
2155950.56846916627149.5149680212155904.69278437 627207.10359361
2155877.85062838627270.060650398
#Sta/Elev= 30
       0 1541.66     9.8 1535.61    14.9 1533.42    21.4 1531.89    23.1 1531.34
    29.5 1529.72    32.41529.456    40.5 1529.11    47.21529.376    55.8 1529.48
    60.9 1530.14    66.1 1532.11    69.8 1533.72    71.2 1534.12    72.6 1534.24
    75.9 1534.21    84.6 1531.44    88.9 1530.84    93.9 1531.25    97.6 1531.39
     100 1531.69     102  1532.1   109.1 1535.09   110.7 1535.58     115 1536.27
   119.4 1536.57   123.7 1536.66   128.1 1536.55   136.8 1536.62   142.1 1536.46
#Mann= 3 ,-1,0
       0      .1       0    32.4    .045       0    47.2      .1       0
Bank Sta=32.4,47.2
XS Rating Curve= 0 ,0
Exp/Cntr(USF)=0,0
Exp/Cntr=0.3,0.1

Type RM Length L Ch R = 1 ,11359   ,154.2,151.1,143.6
XS GIS Cut Line= 3
2155857.06005436627046.5912190112155836.50384326627086.913017707
 2155774.4398982627229.620560152
#Sta/Elev= 30
       0 1573.97    20.9 1558.31    25.4 1554.63    29.8 1550.68    34.3 1547.16
    43.3 1543.19    47.7 1539.28    56.5 1529.75    60.8  1525.7    65.2 1523.82
    69.5 1523.23    80.7 1522.96      87 1523.09    98.9 1523.87   104.4 1524.75
   108.8 1525.95   117.1 1529.33   121.9 1529.91   132.3 1530.01   135.4 1529.58
   139.3 1528.25   144.5 1526.91   148.1 1526.46   152.4 1526.66   161.1 1529.31
   171.9 1531.48   174.2 1531.72   178.6 1531.61   190.1 1531.96   200.9 1532.51
#Mann= 3 ,-1,0
       0      .1       0    65.2    .045       0    98.9      .1       0
#XS Ineff= 2 , 0
                          117.61          1549.7
Permanent Ineff=
       F       F
Bank Sta=65.2,98.9
XS Rating Curve= 0 ,0
Exp/Cntr(USF)=0,0
Exp/Cntr=0.3,0.1

Type RM Length L Ch R = 1 ,11208   ,140.7,132.4,121
XS GIS Cut Line= 4
2155692.70885337 627018.274310612155684.27360794627049.605222209
2155663.78801189627165.2885881132155648.12255609627226.142858719
#Sta/Elev= 30
       0 1563.68     7.2 1559.46    19.6 1550.67    23.7 1546.21    27.9 1541.24
    32.4 1536.54    44.2 1526.15    48.3 1522.76    51.5 1520.58    52.3 1520.05
    56.4    1519    60.4 1518.81      77 1519.03    80.8 1519.46    83.9 1520.73
    88.9 1523.15    92.9 1524.55      97 1525.72   101.1 1526.52   105.1 1526.86
   109.2 1526.96   117.3 1526.62   133.6 1526.41   141.7 1526.71   149.8 1527.49
   162.2  1528.2   174.6 1527.78     187 1527.83   199.4 1528.34   212.8 1528.16
#Mann= 3 ,-1,0
       0      .1       0    51.5    .045       0    83.9      .1       0
Bank Sta=51.5,83.9
XS Rating Curve= 0 ,0
Exp/Cntr(USF)=0,0
Exp/Cntr=0.3,0.1

Type RM Length L Ch R = 1 ,11076   ,120.5,113.8,100.4
XS GIS Cut Line= 4
2155538.25133291626989.1620377562155539.59026076627036.693976293
2155576.41077653627190.6706785962155599.17254991627243.558328518
#Sta/Elev= 30
       0 1530.52      16 1530.03      28  1529.2      36 1528.82      48 1529.04
    52.2 1528.94    56.3 1527.76    60.4  1524.6    64.5 1520.82    68.6 1518.83
      69 1518.75    72.7 1517.94    81.6 1517.82    89.2 1517.99   104.9    1518
   109.7 1518.58     118 1522.22   122.1 1522.72   128.1 1522.74   146.8 1521.95
   167.3 1521.66   179.7 1521.65   191.2 1522.92   204.3 1524.87     213 1525.86
   217.3 1526.01   230.4 1525.95   239.1 1526.54   250.2 1526.44   263.4 1526.77
#Mann= 3 ,-1,0
       0      .1       0      69    .045       0   109.7      .1       0
Bank Sta=69,109.7
XS Rating Curve= 0 ,0
Exp/Cntr(USF)=0,0
Exp/Cntr=0.3,0.1

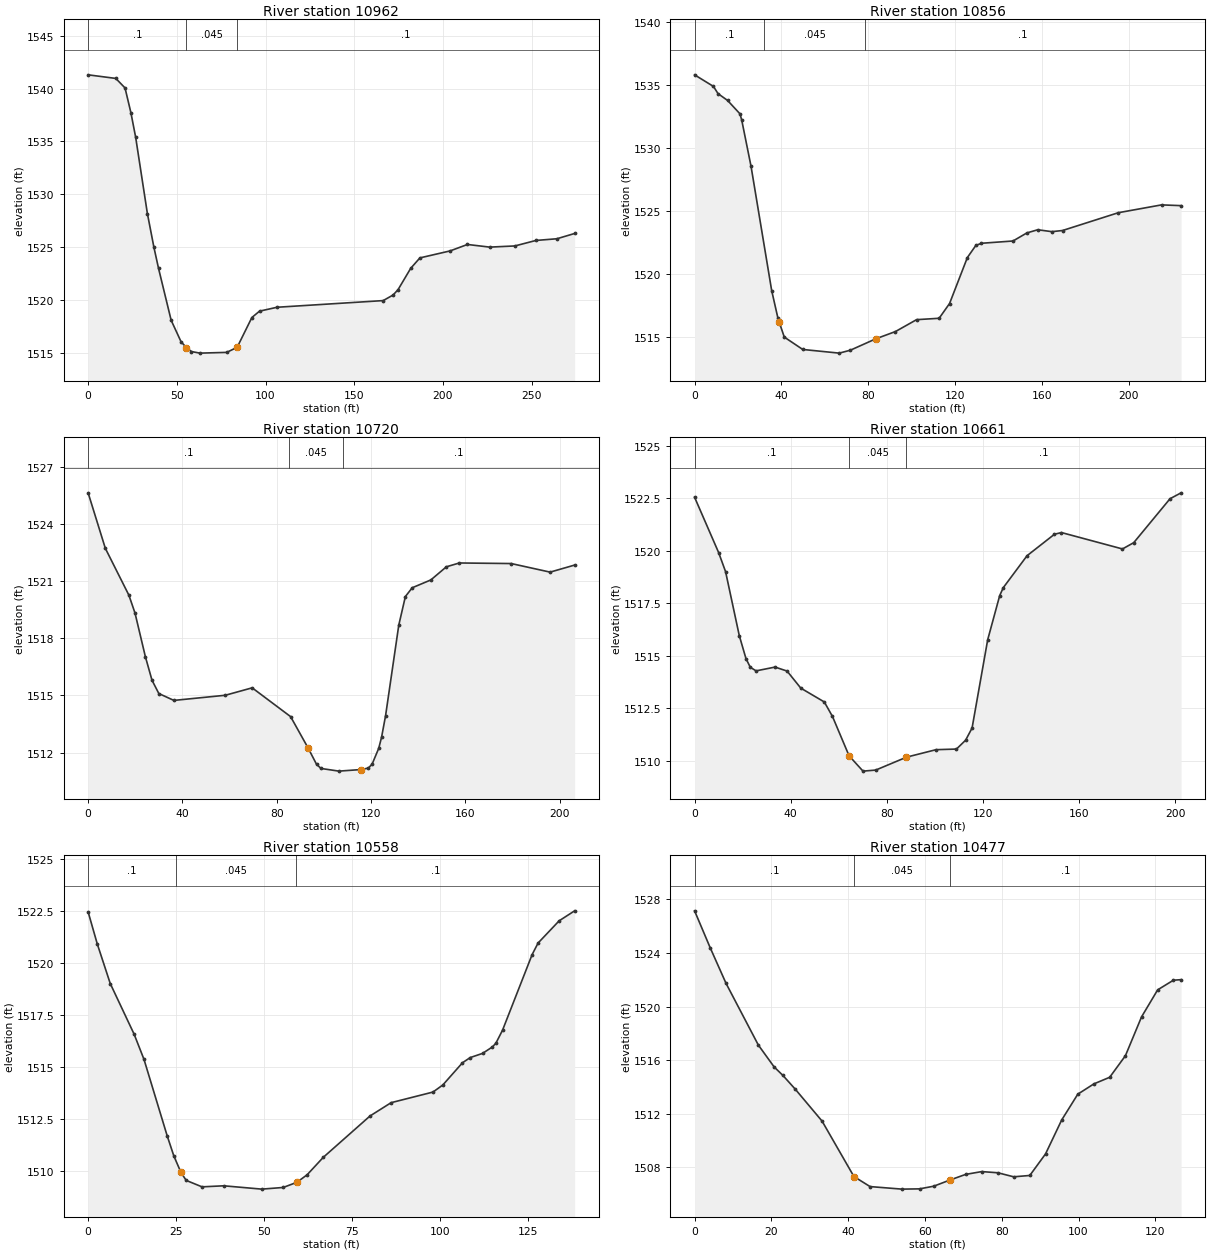
Type RM Length L Ch R = 1 ,10962   ,102,105.6,97.9
XS GIS Cut Line= 3
 2155407.0129922627072.4401798392155537.18653279627231.623823766
2155573.63512416627289.644030431
#Sta/Elev= 30
       0  1541.3    15.6 1540.96    20.8 1540.06    24.1 1537.73    26.8 1535.39
    33.4 1528.18    37.1 1524.97    39.7 1522.98    46.8 1518.08    52.4 1516.04
    55.4  1515.5    58.2 1515.12      63 1514.97    78.1 1515.04      84 1515.52
    92.3 1518.34    96.6 1518.94   106.5 1519.31   166.3 1519.94   171.9 1520.47
   174.7 1520.98   181.8 1522.99     187 1523.98     204 1524.64   213.8 1525.25
   226.3    1525   240.5 1525.11   252.4 1525.63   264.2 1525.79   274.2 1526.29
#Mann= 3 ,-1,0
       0      .1       0    55.4    .045       0      84      .1       0
Bank Sta=55.4,84
XS Rating Curve= 0 ,0
Exp/Cntr(USF)=0,0
Exp/Cntr=0.3,0.1

Type RM Length L Ch R = 1 ,10856   ,140.4,136.4,137.4
XS GIS Cut Line= 2
2155363.68217706627179.8174989282155540.09312448627317.798209484
#Sta/Elev= 30
       0  1535.8     8.7 1534.88    10.8 1534.31    15.2 1533.77    20.9 1532.71
    21.7 1532.22      26 1528.55    35.5 1518.71    38.4 1516.51      391516.199
    41.3 1515.03    49.8 1514.05    66.6 1513.76    71.7 1513.99    83.4 1514.89
    92.5 1515.47   102.2 1516.41   112.6 1516.52   117.4 1517.69   125.6 1521.33
   129.5 1522.29   132.1 1522.46   146.6 1522.64     153 1523.28     158 1523.53
   164.5 1523.38   169.4 1523.47   195.1 1524.88     215  1525.5     224 1525.44
#Mann= 3 ,-1,0
       0      .1       0      32    .045       0    78.6      .1       0
Bank Sta=39,83.4
XS Rating Curve= 0 ,0
Exp/Cntr(USF)=0,0
Exp/Cntr=0.3,0.1

Type RM Length L Ch R = 1 ,10720   ,62.1,59.5,60.8
XS GIS Cut Line= 2
2155288.27350719627266.7362271672155430.03257023627416.703963493
#Sta/Elev= 30
       0 1525.63     7.3 1522.72    17.3 1520.26    19.9 1519.32    24.3 1517.03
    27.1  1515.8      30  1515.1    36.4 1514.74    58.2 1515.01    69.6  1515.4
    85.9 1513.89    93.3 1512.25    96.9 1511.39    98.8 1511.17   106.4 1511.03
   115.71511.112   118.9 1511.19   120.5  1511.4   123.3 1512.23   124.5 1512.81
   126.2 1513.94   131.8 1518.69   134.6 1520.19   137.5 1520.65   145.4 1521.06
     152 1521.75   157.5 1521.95   179.5 1521.92     196 1521.47   206.4 1521.84
#Mann= 3 ,-1,0
       0      .1       0    85.1    .045       0   108.2      .1       0
Bank Sta=93.3,115.7
XS Rating Curve= 0 ,0
Exp/Cntr(USF)=0,0
Exp/Cntr=0.3,0.1

Type RM Length L Ch R = 1 ,10661   ,101.7,102.4,95.8
XS GIS Cut Line= 5
2155246.16591344627313.0621115392155302.40088298627358.585658307
2155312.44284182627373.9833285372155360.64424428627411.473308228
2155396.79529613 627446.95489615
#Sta/Elev= 30
       0 1522.54      10 1519.91    12.9    1519    18.6 1515.96    21.4 1514.86
    23.2 1514.45    25.6 1514.28    33.5 1514.46    38.5 1514.27    44.2 1513.46
      54  1512.8    57.4 1512.11    64.3 1510.24    70.1 1509.51    75.4 1509.56
    88.21510.174   100.5 1510.53     109 1510.56   112.8 1510.98   115.5 1511.56
     122 1515.76     127 1517.86   128.5 1518.24   138.4 1519.76   149.8 1520.78
   152.7 1520.86   178.1 1520.08   182.8 1520.38   197.9 1522.47   202.5 1522.75
#Mann= 3 ,-1,0
       0      .1       0    64.3    .045       0    88.2      .1       0
Bank Sta=64.3,88.2
XS Rating Curve= 0 ,0
Exp/Cntr(USF)=0,0
Exp/Cntr=0.3,0.1

Type RM Length L Ch R = 1 ,10558   ,88.6,81.6,69.4
XS GIS Cut Line= 2
2155183.46246161627375.4432762212155286.19432878627468.129680307
#Sta/Elev= 30
       0 1522.46     2.6 1520.92     6.3 1519.01    13.1 1516.57    15.9 1515.36
    22.5 1511.68    24.4 1510.71    26.41509.929    27.9 1509.54    32.4 1509.23
    38.6 1509.28    49.4 1509.12    55.5  1509.2    59.41509.449    62.3 1509.81
    66.9 1510.65    80.2 1512.64    86.2 1513.28    98.1 1513.79   100.9 1514.13
   106.5  1515.2   108.7 1515.45   112.2 1515.65     115 1515.96     116 1516.14
   117.9 1516.77   126.3  1520.4     128 1520.96     134 1522.03   138.4 1522.51
#Mann= 3 ,-1,0
       0      .1       0    25.1    .045       0    59.2      .1       0
Bank Sta=26.4,59.4
XS Rating Curve= 0 ,0
Exp/Cntr(USF)=0,0
Exp/Cntr=0.3,0.1

Type RM Length L Ch R = 1 ,10477   ,97.4,91.8,85.6
XS GIS Cut Line= 2
2155132.25409538 627460.684345812155254.09652937627495.496469809
#Sta/Elev= 29
       0 1527.15     4.1 1524.37     8.2 1521.73    16.6 1517.13    20.7  1515.5
      23 1514.86    26.2 1513.84    33.2 1511.45    41.5 1507.31    45.7 1506.56
      54 1506.37    58.6 1506.39    62.3 1506.59    66.5 1507.05    70.6 1507.47
    74.8 1507.68      79 1507.59    83.1 1507.29    87.3 1507.39    91.4    1509
    95.6 1511.53    99.8 1513.46     104 1514.23   108.1 1514.72   112.2 1516.33
   116.4 1519.23   120.6 1521.25   124.7 1521.97   126.7 1522.01
#Mann= 3 ,-1,0
       0      .1       0    41.5    .045       0    66.5      .1       0
Bank Sta=41.5,66.5
XS Rating Curve= 0 ,0
Exp/Cntr(USF)=0,0
Exp/Cntr=0.3,0.1

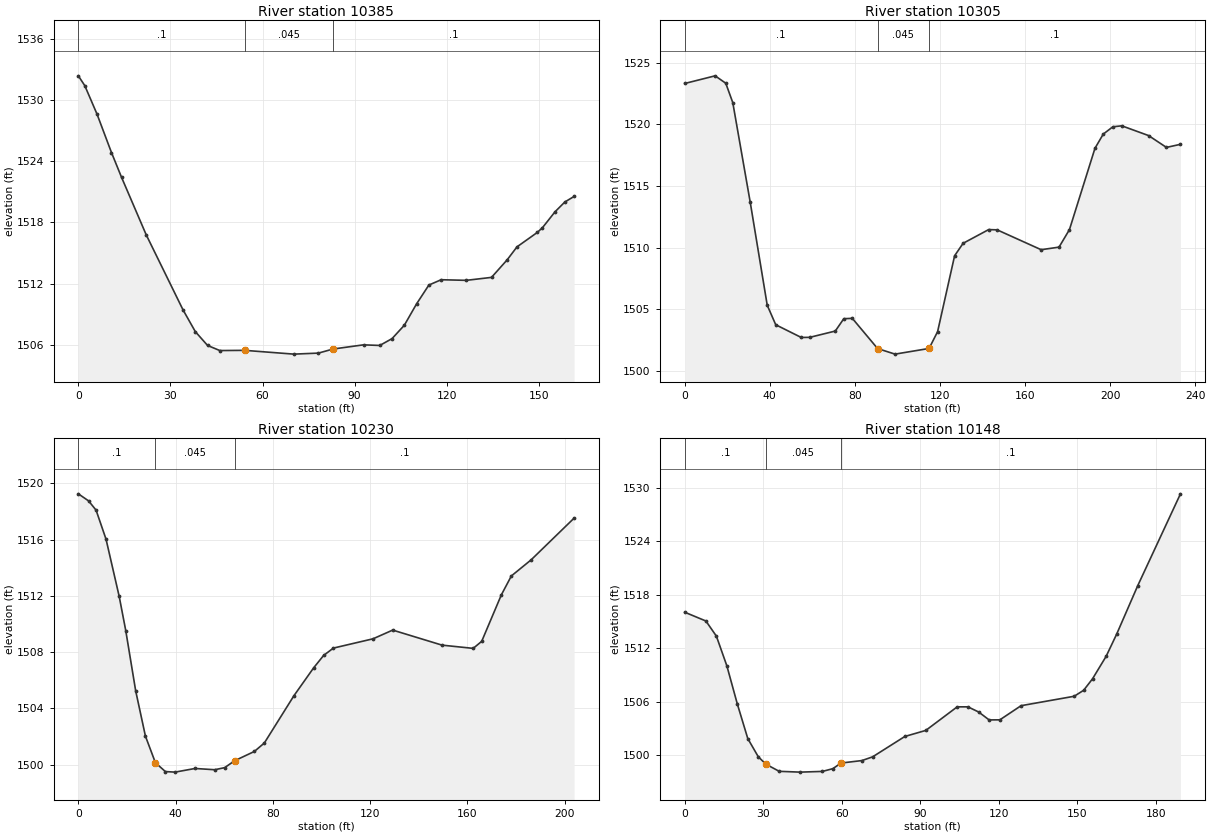
Type RM Length L Ch R = 1 ,10385   ,78.6,79.4,77.2
XS GIS Cut Line= 4
2155102.12821884627565.1207178072155128.90677576627567.129109576
2155224.64011676627562.4428621152155262.13009645627552.400903269
#Sta/Elev= 30
       0 1532.37     2.1 1531.41     6.1 1528.61    10.8 1524.85    14.1 1522.41
    22.1  1516.8    34.1 1509.44    38.1 1507.31    42.1 1505.95    46.1 1505.45
    54.2 1505.47    70.2  1505.1    78.2  1505.2      83  1505.6    92.9 1506.01
    98.2 1505.95   102.2 1506.62   106.2 1507.93   110.2 1510.03   114.2 1511.87
   118.2 1512.39   126.4 1512.33   134.6 1512.62   139.7 1514.34   142.9 1515.61
   149.5 1517.02   151.2 1517.49   155.3 1519.05   158.5 1520.01   161.5 1520.55
#Mann= 3 ,-1,0
       0      .1       0    54.2    .045       0      83      .1       0
Bank Sta=54.2,83
XS Rating Curve= 0 ,0
Exp/Cntr(USF)=0,0
Exp/Cntr=0.3,0.1

Type RM Length L Ch R = 1 ,10305   ,82.5,75.8,74.8
XS GIS Cut Line= 4
 2155090.3415056627646.986856973 2155118.4424604627639.548368939
2155241.59076229627634.5893769162155318.45513864627609.794416803
#Sta/Elev= 30
       0 1523.31    14.3 1523.93    19.3 1523.33    22.6 1521.76    30.8 1513.69
    38.8 1505.34    42.8 1503.76    54.8 1502.73    58.8 1502.74    70.8 1503.25
    74.8 1504.25    78.8 1504.28    90.7 1501.83    98.9 1501.38   114.9 1501.84
   118.9  1503.2   126.9 1509.35   130.9 1510.36   142.9 1511.47   146.9 1511.45
   167.6 1509.84     176 1510.05   180.9 1511.47   192.9 1518.06   196.8 1519.21
   201.3  1519.8   205.5 1519.88   218.1 1519.09   226.5 1518.13   233.1 1518.38
#Mann= 3 ,-1,0
       0      .1       0    90.7    .045       0   114.9      .1       0
Bank Sta=90.7,114.9
XS Rating Curve= 0 ,0
Exp/Cntr(USF)=0,0
Exp/Cntr=0.3,0.1

Type RM Length L Ch R = 1 ,10230   ,76.1,81.3,83.4
XS GIS Cut Line= 3
2155132.98821536627722.8977388682155265.30106512627698.495778873
2155333.62655311627686.565931764
#Sta/Elev= 30
       0 1519.25     4.2 1518.75     7.3 1518.09    11.4 1516.02    16.8 1511.96
    19.5 1509.53    23.6 1505.23    27.6 1502.02    31.7 1500.13    35.8  1499.5
    39.8 1499.46      48 1499.72    56.1 1499.63    60.2 1499.78    64.3 1500.27
    72.4 1500.93    76.5 1501.53    88.7  1504.9    96.8 1506.88   100.9 1507.76
   104.9 1508.28   121.2 1508.94   129.3 1509.56   149.6 1508.49   162.4 1508.26
   165.9 1508.76     174 1512.07   178.1 1513.41   186.2 1514.55   203.9 1517.52
#Mann= 3 ,-1,0
       0      .1       0    31.7    .045       0    64.3      .1       0
Bank Sta=31.7,64.3
XS Rating Curve= 0 ,0
Exp/Cntr(USF)=0,0
Exp/Cntr=0.3,0.1

Type RM Length L Ch R = 1 ,10148   ,62.1,60.5,60.4
XS GIS Cut Line= 3
2155140.03767047627793.9345557442155244.15269979627793.392289966
2155328.20389533627808.033465964
#Sta/Elev= 30
       0 1516.04     8.1 1515.05    12.1 1513.35    16.1 1510.01    20.1 1505.72
    24.1 1501.83    28.1 1499.79      311498.956    36.1 1498.15    44.1 1498.06
    52.6 1498.14    56.6 1498.45    59.7 1499.08    67.7 1499.36    71.8 1499.78
    84.1 1502.07    92.1 1502.75   104.1  1505.4   108.2  1505.4   112.3 1504.82
   116.3 1503.93   120.4 1503.94   128.5 1505.53   148.8 1506.59   152.4 1507.26
   155.8 1508.55     161 1511.08     165 1513.56   173.1 1519.04   189.4 1529.35
#Mann= 3 ,-1,0
       0      .1       0      31    .045       0    59.7      .1       0
Bank Sta=31,59.7
XS Rating Curve= 0 ,0
Exp/Cntr(USF)=0,0
Exp/Cntr=0.3,0.1