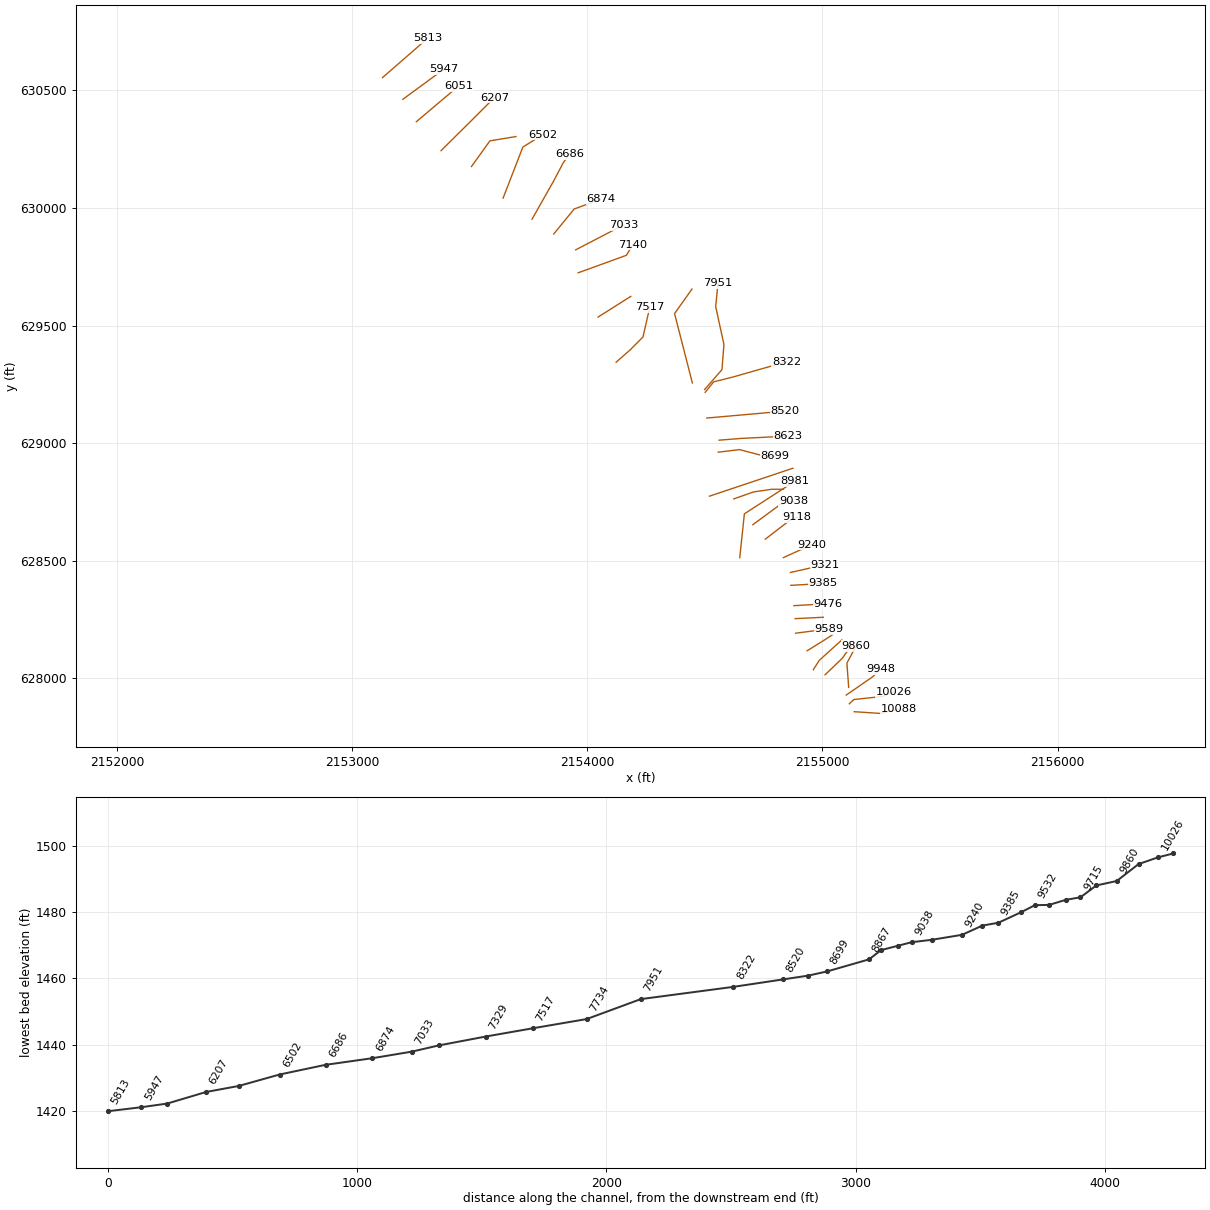
HEC-RAS study LFRFLIKANA.prj: LFRFLIKANA

--- LFRFLIKANA.g01 (geometry) --- (continued)

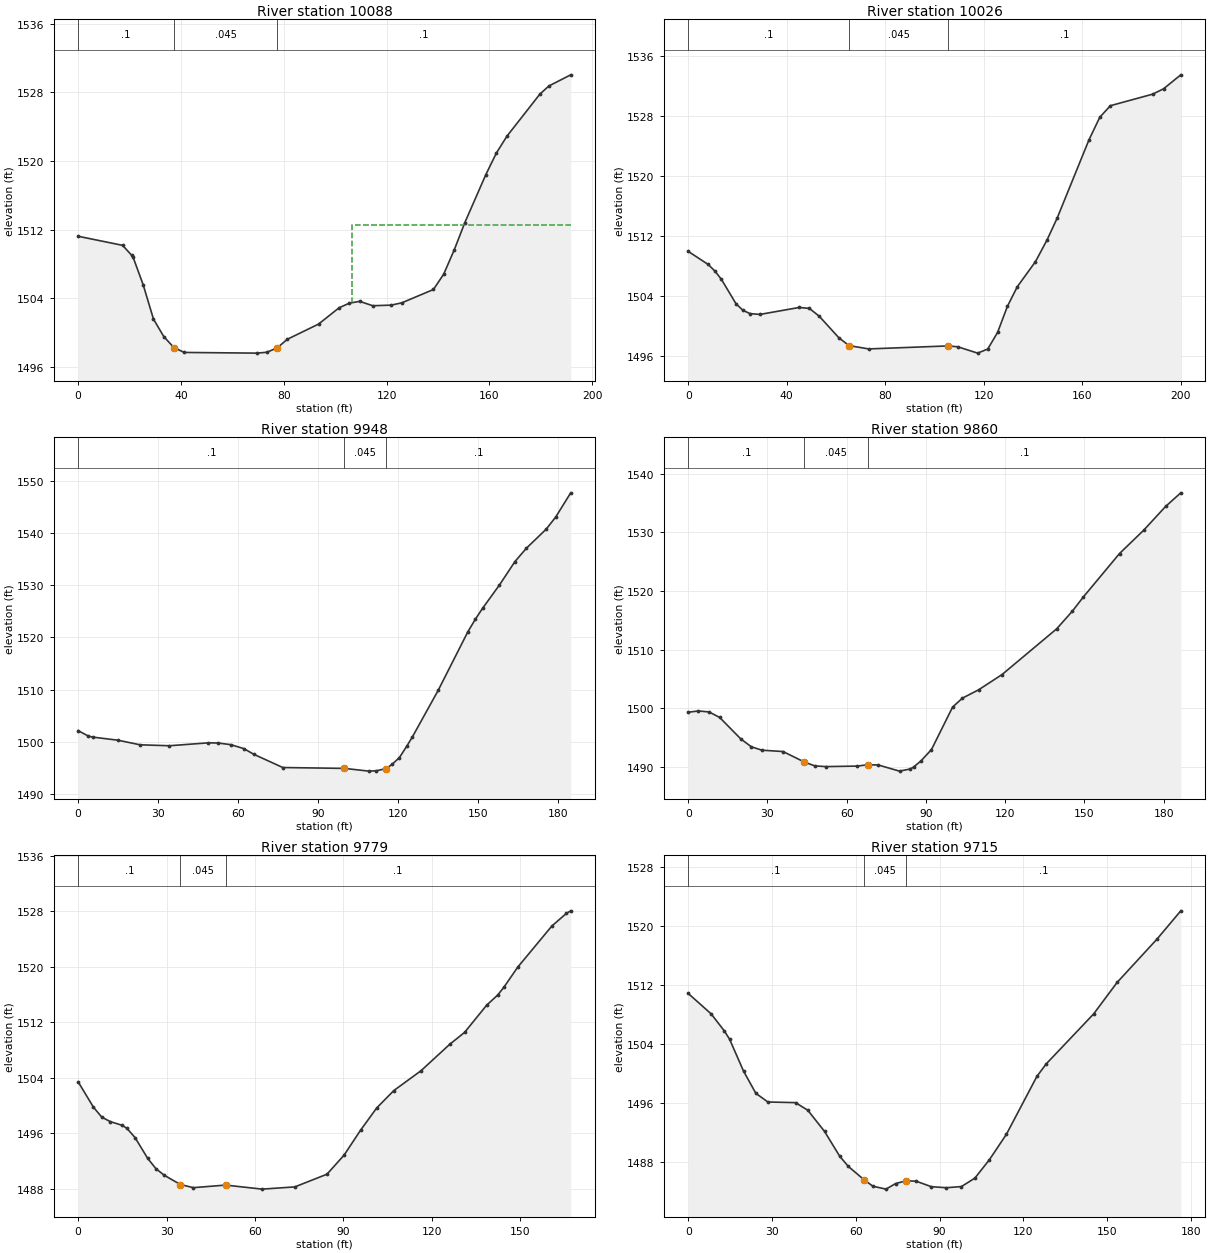
Type RM Length L Ch R = 1 ,10088   ,57.5,62.3,66.1
XS GIS Cut Line= 3
2155134.91873735 627858.069551942155243.06816823  627850.8724624
2155324.40803488627868.224967286
#Sta/Elev= 30
       0 1511.23    17.3 1510.17    20.8 1509.02    21.3 1508.84    25.3 1505.57
    29.3 1501.58    33.3 1499.55    37.3 1498.25    41.3  1497.7    69.4 1497.62
    73.4 1497.72    77.4 1498.23    81.4 1499.24    93.5    1501   101.5  1502.9
   105.5 1503.44   109.5 1503.65   114.6 1503.14   121.8 1503.21   125.9 1503.48
   138.2 1505.03   142.2 1506.82   146.3 1509.65   150.4 1512.81   158.6 1518.42
   162.7 1520.93   166.8 1522.89   179.6 1527.78   183.1 1528.73   191.6 1530.03
#Mann= 3 ,-1,0
       0      .1       0    37.3    .045       0    77.4      .1       0
#XS Ineff= 2 , 0
                          106.37         1512.49
Permanent Ineff=
       F       F
Bank Sta=37.3,77.4
XS Rating Curve= 0 ,0
Exp/Cntr(USF)=0,0
Exp/Cntr=0.3,0.1

Type RM Length L Ch R = 1 ,10026   ,72.6,77.7,82.6
XS GIS Cut Line= 4
2155114.26342632627891.6762418212155133.87764935627909.854214152
2155255.09549876627922.6929047732155302.71270611 627941.96653632
#Sta/Elev= 30
       0 1509.96     8.1 1508.22    10.9 1507.32    13.5 1506.22    19.4 1502.99
    22.2 1502.12    25.1 1501.68    29.1 1501.57    45.1  1502.5    49.2 1502.37
    53.2 1501.33    61.2 1498.45    65.3 1497.42    73.3 1496.98   105.5 1497.38
   109.5 1497.26   117.5 1496.42   121.6 1496.96   125.6 1499.17   129.6 1502.65
   133.6 1505.25     141  1508.6   145.7 1511.49   149.8 1514.39   162.7 1524.79
   167.1 1527.81   171.4 1529.35   188.6 1530.89     193  1531.6     200 1533.46
#Mann= 3 ,-1,0
       0      .1       0    65.3    .045       0   105.5      .1       0
Bank Sta=65.3,105.5
XS Rating Curve= 0 ,0
Exp/Cntr(USF)=0,0
Exp/Cntr=0.3,0.1

Type RM Length L Ch R = 1 ,9948    ,73.5,87.7,102.9
XS GIS Cut Line= 4
2155101.07132262627928.7443420112155143.15039415627957.682055747
2155212.01326354 628005.456146122155248.29304057628039.468437085
#Sta/Elev= 30
       0 1502.15     3.8 1501.12     5.4 1500.92    14.9 1500.32    23.2 1499.44
    34.2 1499.26    48.6 1499.81    52.3 1499.79    57.2 1499.47    62.1 1498.71
    65.8 1497.63    76.7 1495.09    99.81494.925   108.9  1494.4   111.8 1494.47
   115.41494.885   117.6 1495.68   120.4 1496.99   123.3 1499.29   125.3 1500.99
   134.9 1509.84   146.1 1521.13   148.9 1523.52   151.6  1525.6   157.9 1530.05
   163.7 1534.53     168 1537.09   175.4 1540.73     179 1543.07   184.6 1547.69
#Mann= 3 ,-1,0
       0      .1       0    99.8    .045       0   115.4      .1       0
Bank Sta=99.8,115.4
XS Rating Curve= 0 ,0
Exp/Cntr(USF)=0,0
Exp/Cntr=0.3,0.1

Type RM Length L Ch R = 1 ,9860    ,92.8,81.3,66.2
XS GIS Cut Line= 3
2155111.53138937627961.3408218552155104.09290133628064.735805527
2155143.51688791 628137.63298826
#Sta/Elev= 30
       0 1499.33     3.8 1499.55     7.9 1499.38    11.9 1498.44    19.9 1494.78
    23.9 1493.44    27.9 1492.86    35.9 1492.63      44 1490.83    47.9 1490.19
      52 1490.06      64 1490.15      68 1490.38      72 1490.33      80 1489.29
    84.1 1489.66    85.3 1489.98    88.1 1491.02    92.1 1492.97   100.1 1500.21
   103.8 1501.73     110 1503.17   118.8 1505.75   139.5 1513.55   145.4 1516.54
   149.6 1518.98   163.3 1526.39   172.4 1530.34   180.8 1534.44   186.5 1536.74
#Mann= 3 ,-1,0
       0      .1       0      44    .045       0      68      .1       0
Bank Sta=44,68
XS Rating Curve= 0 ,0
Exp/Cntr(USF)=0,0
Exp/Cntr=0.3,0.1

Type RM Length L Ch R = 1 ,9779    ,63.5,64.1,62.9
XS GIS Cut Line= 3
2155011.11180091628014.8979356992155084.00898364628084.819723219
2155122.68912142628138.376837063
#Sta/Elev= 30
       0 1503.43     5.2 1499.77       8 1498.35    10.9  1497.7    14.9 1497.17
    16.5 1496.75    19.3  1495.4    23.6 1492.39    26.4 1490.91    29.2 1489.97
    34.7 1488.63    39.1 1488.18      501488.553    62.4 1487.97    73.5 1488.29
    84.4 1490.12    90.2 1492.86    95.8 1496.46   101.3 1499.68   107.1 1502.18
   116.3 1505.03   126.1 1508.86   131.1 1510.56   138.6 1514.49   142.3 1515.93
   144.4 1517.05   149.1 1519.95   160.7 1525.89   165.6  1527.7   167.1 1528.08
#Mann= 3 ,-1,0
       0      .1       0    34.7    .045       0      50      .1       0
Bank Sta=34.7,50
XS Rating Curve= 0 ,0
Exp/Cntr(USF)=0,0
Exp/Cntr=0.3,0.1

Type RM Length L Ch R = 1 ,9715    ,61.3,58.6,55.5
XS GIS Cut Line= 4
2154961.28307204628036.708890994 2154986.1029745628075.915533765
2155040.12190424628124.9875586022155082.52128604628162.923847575
#Sta/Elev= 30
       0 1510.85     8.2 1508.09    12.9 1505.79    14.8 1504.66    19.8 1500.34
    24.2 1497.34    28.5 1496.17    38.4 1496.08    42.8 1495.05    48.8 1492.18
    54.2 1488.84    57.3 1487.45    62.9 1485.66    66.1 1484.77    70.8 1484.38
    74.2 1485.13      78 1485.51    81.6 1485.45      87 1484.71    92.4 1484.57
    97.8 1484.73   102.6 1485.87   107.8 1488.36   113.9 1491.81   124.8 1499.63
   128.1 1501.31   145.1 1508.08   153.5 1512.34   167.8 1518.21   176.3 1522.03
#Mann= 3 ,-1,0
       0      .1       0    62.9    .045       0      78      .1       0
Bank Sta=62.9,78
XS Rating Curve= 0 ,0
Exp/Cntr(USF)=0,0
Exp/Cntr=0.3,0.1

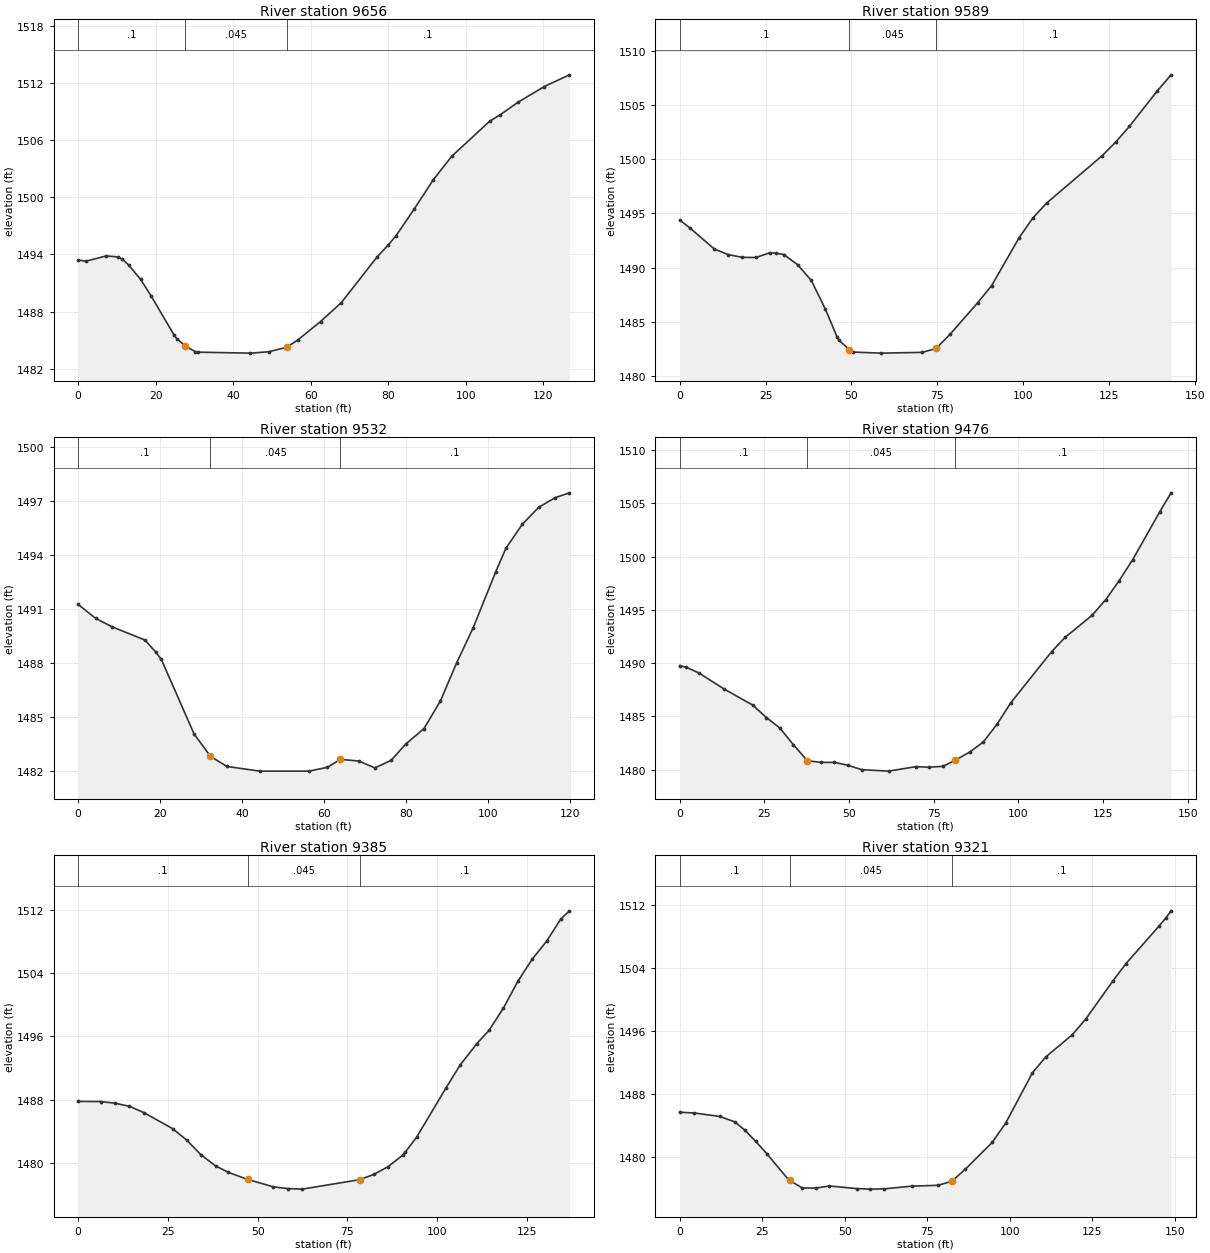
Type RM Length L Ch R = 1 ,9656    ,73.9,67.2,58.5
XS GIS Cut Line= 3
2154934.49537416628116.8052217652155011.11180091628164.411545182
2155041.60960185628184.495462874
#Sta/Elev= 30
       0 1493.42       2 1493.29     7.3 1493.85    10.2 1493.74    11.4 1493.52
    13.1 1492.86    16.1 1491.39    18.9 1489.59    24.7 1485.56    25.5 1485.13
    27.6 1484.39    30.2 1483.79      31 1483.73    44.4 1483.63    49.1 1483.77
    53.8 1484.25    56.7 1485.03    62.5 1486.95    67.9 1488.95      77  1493.7
    79.9 1494.97      82 1495.98    86.7  1498.8    91.5  1501.8    96.3  1504.3
   106.1    1508   108.9  1508.7   113.4 1509.99   120.2 1511.65   126.7 1512.88
#Mann= 3 ,-1,0
       0      .1       0    27.6    .045       0    53.8      .1       0
Bank Sta=27.6,53.8
XS Rating Curve= 0 ,0
Exp/Cntr(USF)=0,0
Exp/Cntr=0.3,0.1

Type RM Length L Ch R = 1 ,9589    ,60.7,57,56.5
XS GIS Cut Line= 3
2154886.14520194628191.9339509082154985.07709279628204.579380566
2155028.22032339628207.554775779
#Sta/Elev= 30
       0 1494.39     2.9 1493.68    10.1 1491.71    14.1  1491.2    18.2 1490.94
    22.2 1490.93    26.2 1491.36      28 1491.33    30.3  1491.2    34.3 1490.27
    38.3 1488.81    42.4 1486.16    45.8 1483.59    46.4 1483.27    49.4 1482.41
    50.4 1482.19    58.5 1482.09    70.6 1482.16    74.6 1482.52    78.7 1483.83
    86.7 1486.74    90.8 1488.34    98.8 1492.76   102.8 1494.59   106.9 1495.99
   122.9 1500.32   126.9  1501.6   130.9 1503.05   138.9 1506.29     143 1507.81
#Mann= 3 ,-1,0
       0      .1       0    49.4    .045       0    74.6      .1       0
Bank Sta=49.4,74.6
XS Rating Curve= 0 ,0
Exp/Cntr(USF)=0,0
Exp/Cntr=0.3,0.1

Type RM Length L Ch R = 1 ,9532    ,55.7,55.9,58.2
XS GIS Cut Line= 2
2154883.91365553 628253.673401592155003.67331288628259.624192017
#Sta/Elev= 27
       0 1491.25     4.3 1490.48     8.3 1490.01    16.3 1489.28    18.9 1488.62
    20.3 1488.21    28.3 1484.07    32.3 1482.83    36.3 1482.27    44.3 1482.01
    56.3 1482.01    60.8 1482.22      64 1482.66    68.5 1482.57    72.4 1482.19
    76.4 1482.61    79.9  1483.5    84.4 1484.37    88.4  1485.9    92.4 1488.03
    96.4 1489.96   101.9 1493.06   104.4 1494.37   108.4  1495.7   112.4 1496.64
   116.4 1497.17   119.9 1497.44
#Mann= 3 ,-1,0
       0      .1       0    32.3    .045       0      64      .1       0
Bank Sta=32.3,64
XS Rating Curve= 0 ,0
Exp/Cntr(USF)=0,0
Exp/Cntr=0.3,0.1

Type RM Length L Ch R = 1 ,9476    ,88.8,90.6,89.7
XS GIS Cut Line= 3
2154878.58023481 628308.914927992154982.04454519628314.771398389
2155023.52787719628315.259437588
#Sta/Elev= 30
       0 1489.76     1.8 1489.62     5.6 1489.09    13.1 1487.57    21.6 1486.05
    25.6 1484.89    29.6  1483.9    33.6 1482.33    37.7 1480.84    41.7 1480.68
    45.7 1480.68    49.7 1480.41    53.7    1480    61.7 1479.86    69.7 1480.28
    73.6 1480.23    77.7 1480.31    81.4 1480.88    85.7 1481.66    89.7 1482.61
    93.7 1484.26    97.8 1486.29   109.8 1491.06   113.8 1492.41   121.8 1494.49
   125.8 1495.95   129.8 1497.75   133.8 1499.72   141.8 1504.22   145.1 1505.98
#Mann= 3 ,-1,0
       0      .1       0    37.7    .045       0    81.4      .1       0
Bank Sta=37.7,81.4
XS Rating Curve= 0 ,0
Exp/Cntr(USF)=0,0
Exp/Cntr=0.3,0.1

Type RM Length L Ch R = 1 ,9385    ,61,64.2,69.4
XS GIS Cut Line= 3
2154865.89121562628395.297866374 2154967.4033692628401.154336773
2155002.54219159628403.594532772
#Sta/Elev= 30
       0 1487.79     6.3 1487.77    10.3 1487.56    14.3 1487.17    18.3 1486.38
    26.3 1484.36    30.3 1482.89    34.3 1481.02    38.3 1479.65    41.8 1478.84
    47.2 1477.94    54.4    1477    58.4 1476.78    62.4 1476.71    78.4  1477.9
    82.4 1478.57    86.4 1479.56    90.4 1480.99    91.1 1481.35    94.4 1483.33
   102.5  1489.5   106.5 1492.43   111.1 1495.09   114.5 1496.77   118.5 1499.58
   122.5 1502.95   126.5 1505.74   130.5 1508.01   134.5 1510.84   136.9 1511.86
#Mann= 3 ,-1,0
       0      .1       0    47.2    .045       0    78.4      .1       0
Bank Sta=47.2,78.4
XS Rating Curve= 0 ,0
Exp/Cntr(USF)=0,0
Exp/Cntr=0.3,0.1

Type RM Length L Ch R = 1 ,9321    ,75.9,81.5,90.1
XS GIS Cut Line= 3
2154863.85026972 628449.984629512154960.92126658628471.946393506
2155009.67638265628479.852628544
#Sta/Elev= 30
       0 1485.65     4.4 1485.56    12.1 1485.12    16.7 1484.43    19.7 1483.39
      23 1481.96    26.4 1480.38    33.1    1477    33.3 1476.97    37.2    1476
    41.3    1476    45.4 1476.26    53.6 1475.93    57.7 1475.86    61.8 1475.89
    70.4 1476.24    78.3 1476.35    82.4 1476.85    86.5 1478.37    94.7 1481.81
    98.8 1484.28   106.9 1490.68   110.9 1492.68     119 1495.53   123.1 1497.55
   131.3 1502.38   135.2 1504.56   145.3 1509.38   147.4 1510.43   148.9  1511.3
#Mann= 3 ,-1,0
       0      .1       0    33.3    .045       0    82.4      .1       0
Bank Sta=33.3,82.4
XS Rating Curve= 0 ,0
Exp/Cntr(USF)=0,0
Exp/Cntr=0.3,0.1

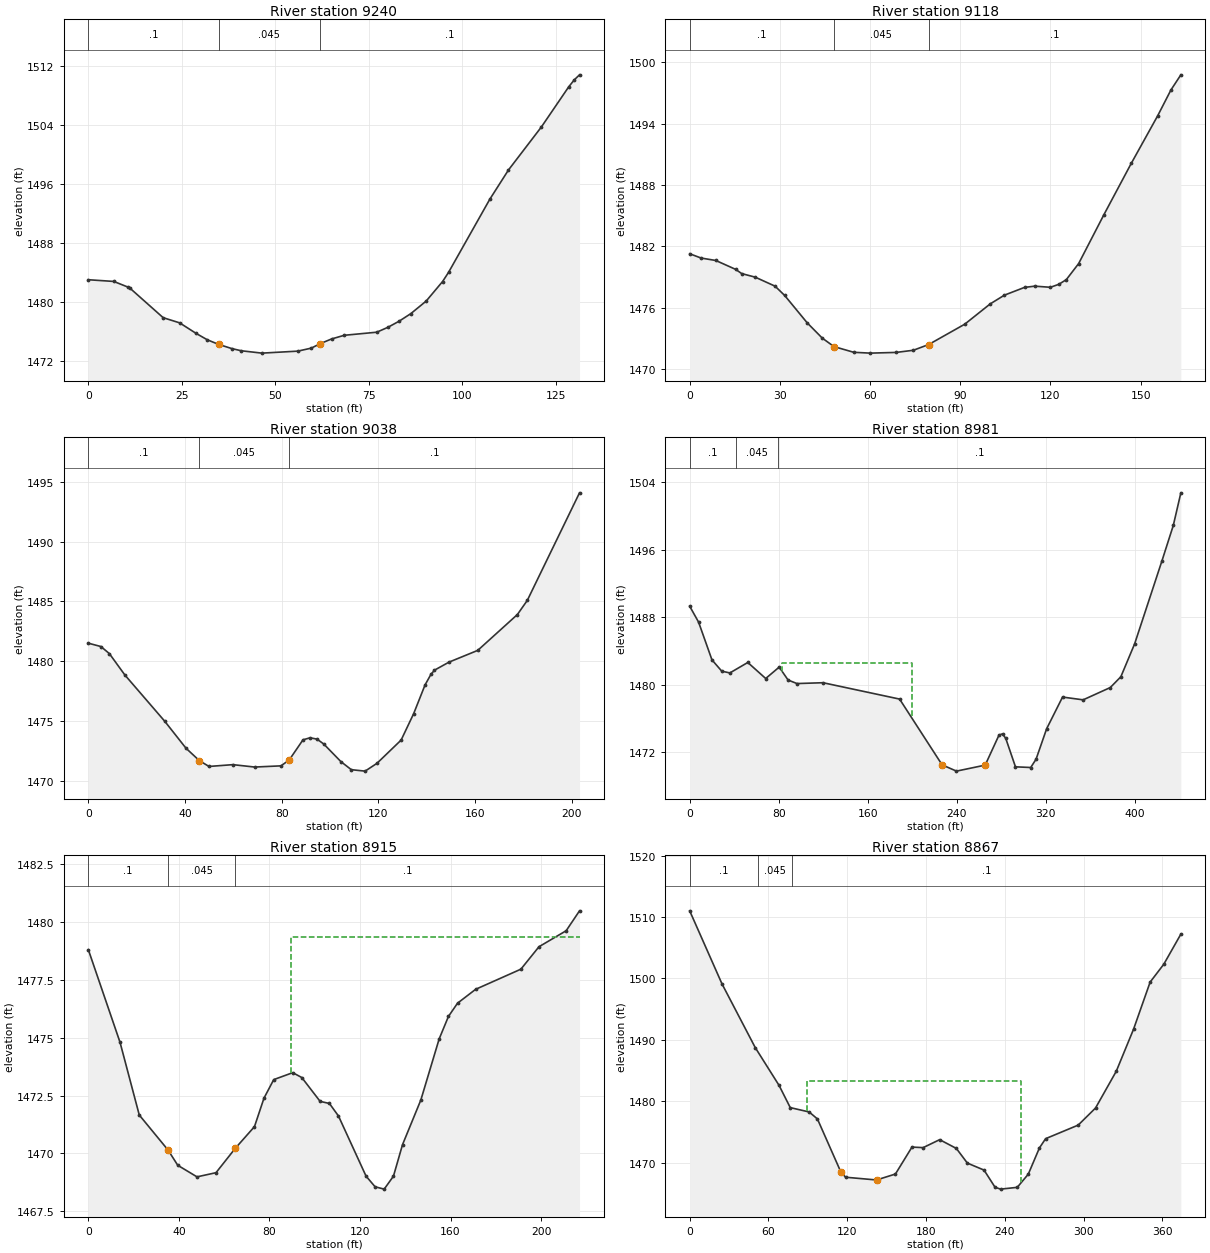
Type RM Length L Ch R = 1 ,9240    ,116.3,121.5,124.9
XS GIS Cut Line= 2
2154833.98227068628513.2345098182154953.45426682628567.699684528
#Sta/Elev= 30
       0 1483.03     6.8  1482.8    10.7 1482.01    11.2 1481.85      20 1477.88
    24.4 1477.18    28.8 1475.75    31.8 1474.88    34.8 1474.26    38.4 1473.68
    40.9 1473.39    46.4 1473.07      56 1473.34    59.6 1473.75      62 1474.36
      65 1474.99    68.4 1475.49    77.1 1475.91    80.1 1476.58    83.1 1477.41
    86.2 1478.43    90.3 1480.13    94.7 1482.79    96.3 1484.04   107.3 1493.94
   112.3 1497.92   121.1 1503.76   128.4  1509.2   129.9 1510.16   131.3 1510.84
#Mann= 3 ,-1,0
       0      .1       0    34.8    .045       0      62      .1       0
Bank Sta=34.8,62
XS Rating Curve= 0 ,0
Exp/Cntr(USF)=0,0
Exp/Cntr=0.3,0.1

Type RM Length L Ch R = 1 ,9118    ,80.5,80.4,79.2
XS GIS Cut Line= 3
2154757.20399951628591.8644765972154856.43863683 628668.32395125
 2154891.1436466628684.049658802
#Sta/Elev= 30
       0 1481.29     3.8 1480.87     8.7 1480.63    15.3 1479.76    17.3 1479.35
    21.8    1479    28.4 1478.12    31.6 1477.21    39.1 1474.53    44.1 1473.04
      48 1472.21    54.6 1471.65    60.1 1471.57    68.7 1471.64    74.4 1471.85
    79.5 1472.41    91.5  1474.4     100 1476.39   104.7 1477.24   111.4    1478
   114.8 1478.12     120 1478.01   122.8  1478.3   125.3 1478.76   129.4 1480.33
   137.8 1485.11   146.9 1490.13   155.7 1494.79   160.1 1497.31   163.4 1498.79
#Mann= 3 ,-1,0
       0      .1       0      48    .045       0    79.5      .1       0
Bank Sta=48,79.5
XS Rating Curve= 0 ,0
Exp/Cntr(USF)=0,0
Exp/Cntr=0.3,0.1

Type RM Length L Ch R = 1 ,9038    ,57.3,57,54
XS GIS Cut Line= 3
2154703.97789839628653.2163820532154822.24985813 628740.24669205
2154877.29466958628752.148272905
#Sta/Elev= 30
       0 1481.52     5.2 1481.24     8.7 1480.65    15.1 1478.87    31.6 1475.01
    40.4 1472.76    45.9 1471.73    49.9 1471.24    59.8 1471.39    68.8 1471.19
    79.7 1471.29    83.1 1471.78    88.8 1473.46    91.7 1473.63    94.6 1473.52
    97.4 1473.11   104.5 1471.64   108.8 1470.97   114.5 1470.85   119.4  1471.5
   129.4 1473.44   134.6 1475.65   139.3 1478.04   141.7 1478.91   143.2 1479.27
   149.2 1479.94   161.1 1480.92   177.5 1483.91   181.6 1485.09   203.2 1494.06
#Mann= 3 ,-1,0
       0      .1       0    45.9    .045       0    83.1      .1       0
Bank Sta=45.9,83.1
XS Rating Curve= 0 ,0
Exp/Cntr(USF)=0,0
Exp/Cntr=0.3,0.1

Type RM Length L Ch R = 1 ,8981    ,71.6,66,64.1
XS GIS Cut Line= 3
2154648.40092607628513.2616348522154668.02939672628699.414905458
2154881.41442089628837.337108244
#Sta/Elev= 30
       0 1489.29       8  1487.4      20 1482.93    28.8 1481.59    36.1 1481.38
    52.2 1482.62    68.3 1480.72    80.4 1482.07    88.4 1480.54    96.4 1480.12
   119.8 1480.22   188.6 1478.28   226.81470.483   239.7 1469.74   265.51470.453
   277.9 1474.01   281.1 1474.16     284 1473.61   292.7 1470.25   306.4 1470.17
   311.2 1471.15   320.7 1474.76     335 1478.52   353.5 1478.19   377.9 1479.65
   387.4 1480.93   399.8 1484.84   424.2 1494.62   434.5 1498.86   441.3 1502.73
#Mann= 3 ,-1,0
       0      .1       0    41.3    .045       0    79.7      .1       0
#XS Ineff= 1 ,-1
   83.27   199.6 1482.57
Permanent Ineff=
       F
Bank Sta=226.8,265.5
XS Rating Curve= 0 ,0
Exp/Cntr(USF)=0,0
Exp/Cntr=0.3,0.1

Type RM Length L Ch R = 1 ,8915    ,46.6,48.2,47.4
XS GIS Cut Line= 4
2154622.93516578628762.8863125922154707.13656895628792.534693987
2154785.01298408628803.9987347932154834.03164131628803.998734793
#Sta/Elev= 30
       0  1478.8      14  1474.8    22.5 1471.66    35.2 1470.15    39.5 1469.49
      48 1468.99    56.4 1469.17    64.9 1470.22    73.4 1471.16    77.6 1472.39
    81.9 1473.19    90.3 1473.49    94.3 1473.28   102.4 1472.25   106.5 1472.16
   110.5 1471.62   122.7 1469.02   126.7 1468.56   130.7 1468.46   134.8 1469.02
   138.8 1470.38   146.9 1472.31     155 1474.95   159.1 1475.92   163.1 1476.49
   171.1 1477.09   191.1 1477.96   199.1 1478.93   211.1 1479.62     217 1480.48
#Mann= 3 ,-1,0
       0      .1       0    35.2    .045       0    64.9      .1       0
#XS Ineff= 2 , 0
                           89.72         1479.33
Permanent Ineff=
       F       F
Bank Sta=35.2,64.9
XS Rating Curve= 0 ,0
Exp/Cntr(USF)=0,0
Exp/Cntr=0.3,0.1

Type RM Length L Ch R = 1 ,8867    ,171.2,168,154.2
XS GIS Cut Line= 2
2154519.58083541628774.6083938742154874.32458198628893.311857648
#Sta/Elev= 30
       0 1511.01    24.6 1499.11    49.9 1488.74    68.1 1482.56    76.6 1478.95
      91 1478.24    97.3  1477.1     1151468.528   118.7 1467.61   142.31467.161
   156.7 1468.13   169.3 1472.52   177.8 1472.43   190.4 1473.73   203.1  1472.3
   211.5 1469.91   224.2 1468.77   232.6 1465.97   236.8 1465.67   249.5 1465.96
   257.9 1468.11   266.4 1472.39   271.1 1473.89   295.9  1476.1   309.1 1478.88
   324.9 1484.87   338.1 1491.74   350.7  1499.4   361.1 1502.31   374.1 1507.21
#Mann= 3 ,-1,0
       0      .1       0    51.9    .045       0    77.8      .1       0
#XS Ineff= 1 ,-1
   89.07   252.3 1483.29
Permanent Ineff=
       F
Bank Sta=115,142.3
XS Rating Curve= 0 ,0
Exp/Cntr(USF)=0,0
Exp/Cntr=0.3,0.1

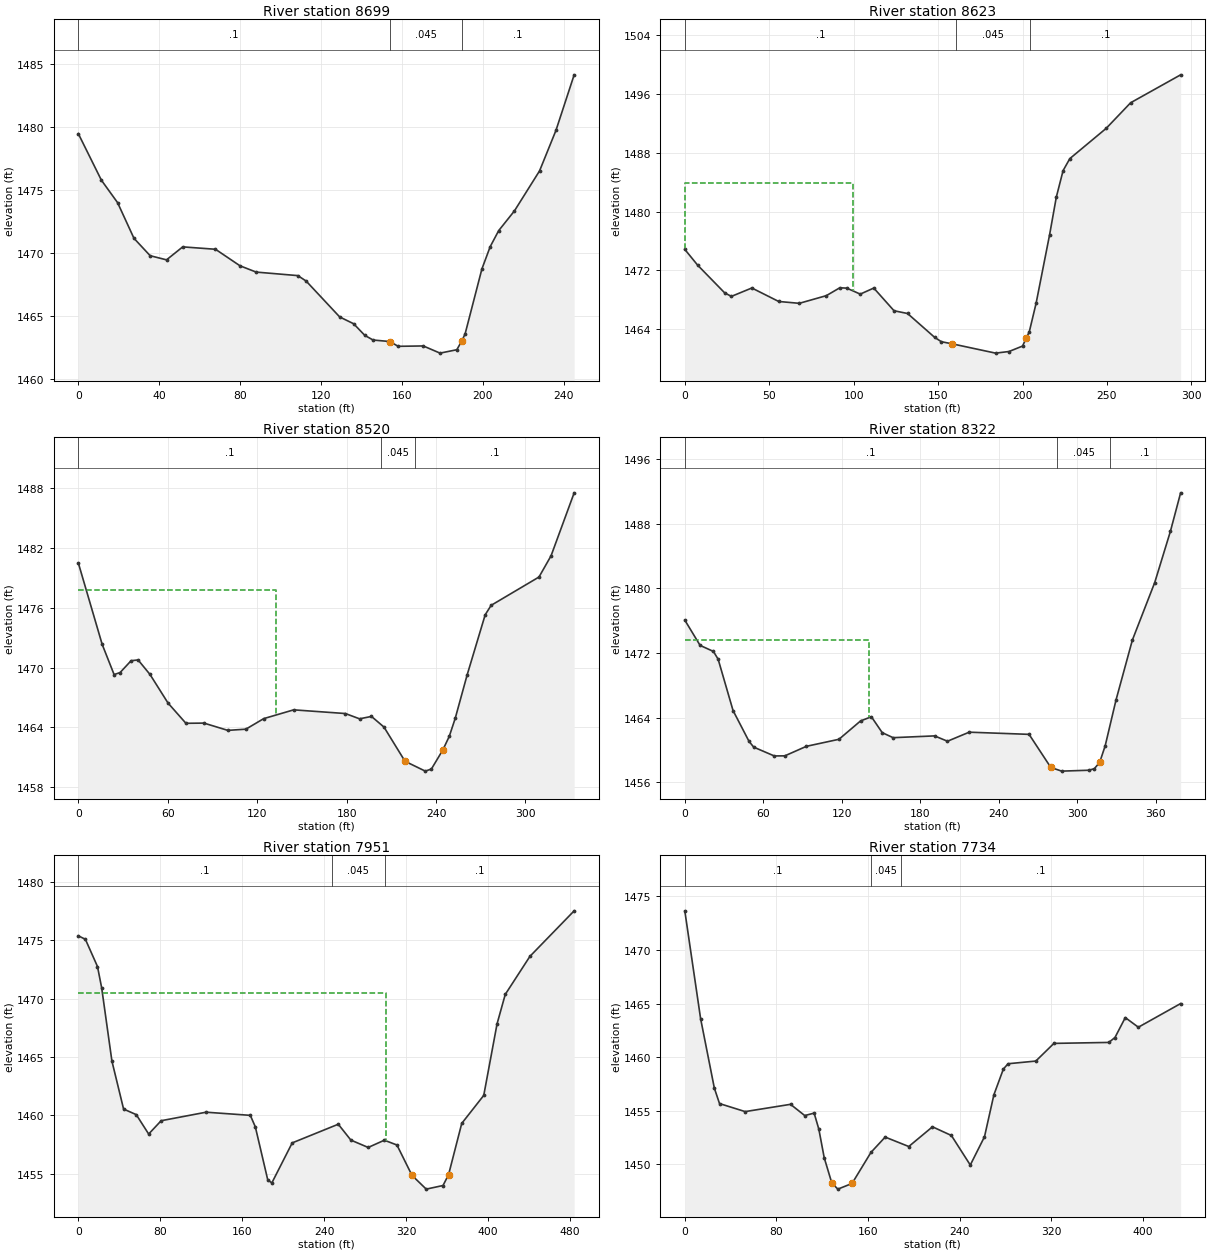
Type RM Length L Ch R = 1 ,8699    ,66.2,75.5,82.1
XS GIS Cut Line= 4
2154556.90524517628961.6218388132154647.38771284628972.602720811
2154765.98123842628941.4170159372154797.16694329628944.491662896
#Sta/Elev= 30
       0 1479.45    11.4 1475.76    19.4 1473.98    27.5 1471.15    35.5 1469.77
    43.6 1469.44    51.6 1470.47    67.8 1470.28    79.9 1468.97    87.9 1468.47
   108.5 1468.19   112.6 1467.76   129.2 1464.91   136.1 1464.37   141.6 1463.45
   145.7 1463.08     154 1462.96   158.1 1462.58   170.5 1462.61   178.8 1462.04
   187.1 1462.31   189.6 1463.02   191.2 1463.57   199.5 1468.72   203.6 1470.49
   207.8 1471.76   215.6 1473.33     228  1476.5   236.1 1479.71   245.1 1484.12
#Mann= 3 ,-1,0
       0      .1       0     154    .045       0   189.6      .1       0
Bank Sta=154,189.6
XS Rating Curve= 0 ,0
Exp/Cntr(USF)=0,0
Exp/Cntr=0.3,0.1

Type RM Length L Ch R = 1 ,8623    ,103.1,103.1,103.8
XS GIS Cut Line= 3
2154560.63424795629012.5864268612154654.12386511629020.185862085
2154853.72208858629029.863902675
#Sta/Elev= 30
       0 1474.86     7.6 1472.72    23.6 1468.96    27.6 1468.48    39.7 1469.62
    55.6 1467.79    67.8 1467.54    83.8 1468.58    91.8 1469.65    95.9  1469.6
   103.9 1468.79   111.9 1469.61   123.9 1466.53   131.9 1466.16   147.9 1462.93
   151.9 1462.33   158.41462.038     184 1460.78     192    1461     200 1461.74
   202.31462.867     204 1463.69     208 1467.52     216 1476.83     220 1481.96
     224 1485.55     228 1487.18   249.5 1491.28     264 1494.76   293.6 1498.55
#Mann= 3 ,-1,0
       0      .1       0   160.8    .045       0   204.6      .1       0
#XS Ineff= 2 , 0
           99.38 1483.93
Permanent Ineff=
       F       F
Bank Sta=158.4,202.3
XS Rating Curve= 0 ,0
Exp/Cntr(USF)=0,0
Exp/Cntr=0.3,0.1

Type RM Length L Ch R = 1 ,8520    ,194.6,197.9,207.9
XS GIS Cut Line= 2
2154508.24150461629106.7760708472154839.64254881629136.107351289
#Sta/Elev= 30
       0  1480.5      16 1472.33      24  1469.3      28  1469.5    35.4 1470.69
    40.1 1470.77    48.1 1469.31    60.2 1466.44    72.2 1464.41    84.3 1464.43
   100.3  1463.7   112.4 1463.82   124.4 1464.88   144.5 1465.76   179.2 1465.39
   188.7 1464.86   196.7  1465.1   205.1 1464.03   219.2  1460.6   232.8 1459.61
   236.9 1459.82   244.6 1461.74   248.9  1463.1   252.9 1464.91   260.9 1469.27
     273  1475.3     277 1476.25   309.1 1479.09   317.2 1481.22   332.7 1487.54
#Mann= 3 ,-1,0
       0      .1       0   203.3    .045       0   226.1      .1       0
#XS Ineff= 2 , 0
          132.31 1477.82
Permanent Ineff=
       F       F
Bank Sta=219.2,244.6
XS Rating Curve= 0 ,0
Exp/Cntr(USF)=0,0
Exp/Cntr=0.3,0.1

Type RM Length L Ch R = 1 ,8322    ,332.2,371.1,412.1
XS GIS Cut Line= 4
2154501.44572157629216.0735893582154537.16951314 629260.59533674
2154618.16378019629280.9520682012154847.70142912629346.148440863
#Sta/Elev= 30
       0 1476.07    11.7 1472.94    21.9 1472.19    25.5 1471.23    36.9 1464.88
    49.1 1461.07    52.7 1460.35    68.4 1459.26    76.5 1459.27      93 1460.45
   117.9 1461.32   134.4 1463.59   142.7 1464.11     151 1462.14   159.3 1461.52
     191 1461.74   200.9 1461.08   217.5  1462.2   263.3 1461.93   279.9 1457.84
   288.2 1457.38     309 1457.49   313.2 1457.68   317.3 1458.47   321.5 1460.51
   329.8 1466.19   342.3  1473.6   359.4 1480.72   371.4 1487.06   379.2 1491.82
#Mann= 3 ,-1,0
       0      .1       0     285    .045       0     325      .1       0
#XS Ineff= 2 , 0
          141.07 1473.59
Permanent Ineff=
       F       F
Bank Sta=279.9,317.3
XS Rating Curve= 0 ,0
Exp/Cntr(USF)=0,0
Exp/Cntr=0.3,0.1

Type RM Length L Ch R = 1 ,7951    ,209.5,217.2,225.4
XS GIS Cut Line= 5
2154499.03961883629227.9965434582154572.71404779629312.631209035
 2154581.1465502629419.4344978842154546.08617846629580.621061663
2154555.93240498  629680.1289243
#Sta/Elev= 30
       0 1475.39     6.9 1475.09    18.7 1472.76    22.8 1470.93    32.8 1464.66
    44.2 1460.55    56.6 1460.07    68.7 1458.41    80.9 1459.55   124.8 1460.28
     168 1460.01   172.9 1459.02     185 1454.49     189 1454.22   208.9 1457.65
   253.9 1459.25   266.2 1457.89   283.1 1457.26   298.9 1457.88   311.2 1457.47
   325.9 1454.87   339.8 1453.69   356.2    1454   361.6 1454.92   374.5 1459.32
     396 1461.72     409 1467.85     417 1470.37   441.1 1473.63   484.3 1477.53
#Mann= 3 ,-1,0
       0      .1       0   247.5    .045       0   299.3      .1       0
#XS Ineff= 2 , 0
          300.28  1470.5
Permanent Ineff=
       F       F
Bank Sta=325.9,361.6
XS Rating Curve= 0 ,0
Exp/Cntr(USF)=0,0
Exp/Cntr=0.3,0.1

Type RM Length L Ch R = 1 ,7734    ,238.9,217.2,194.3
XS GIS Cut Line= 3
2154446.93943409629255.8082132962154371.19608329 629550.95954714
2154445.33146569629655.400129898
#Sta/Elev= 30
       0 1473.66    13.8 1463.59    25.8  1457.1    30.3 1455.66    52.7 1454.91
    92.3 1455.59   104.7 1454.54   112.9 1454.77     117 1453.27   121.7  1450.6
   128.3 1448.25   133.6 1447.67     146  1448.2   162.5  1451.1   174.9 1452.53
   195.5 1451.65   216.2 1453.49   232.7 1452.68   249.2 1449.92   261.6 1452.56
   269.8 1456.48   278.1 1458.89   282.2 1459.38   306.4 1459.63   322.2 1461.28
   370.1 1461.37   375.5 1461.83   384.5 1463.69   395.9 1462.79   432.8    1465
#Mann= 3 ,-1,0
       0      .1       0   162.7    .045       0   188.3      .1       0
Bank Sta=128.3,146
XS Rating Curve= 0 ,0
Exp/Cntr(USF)=0,0
Exp/Cntr=0.3,0.1

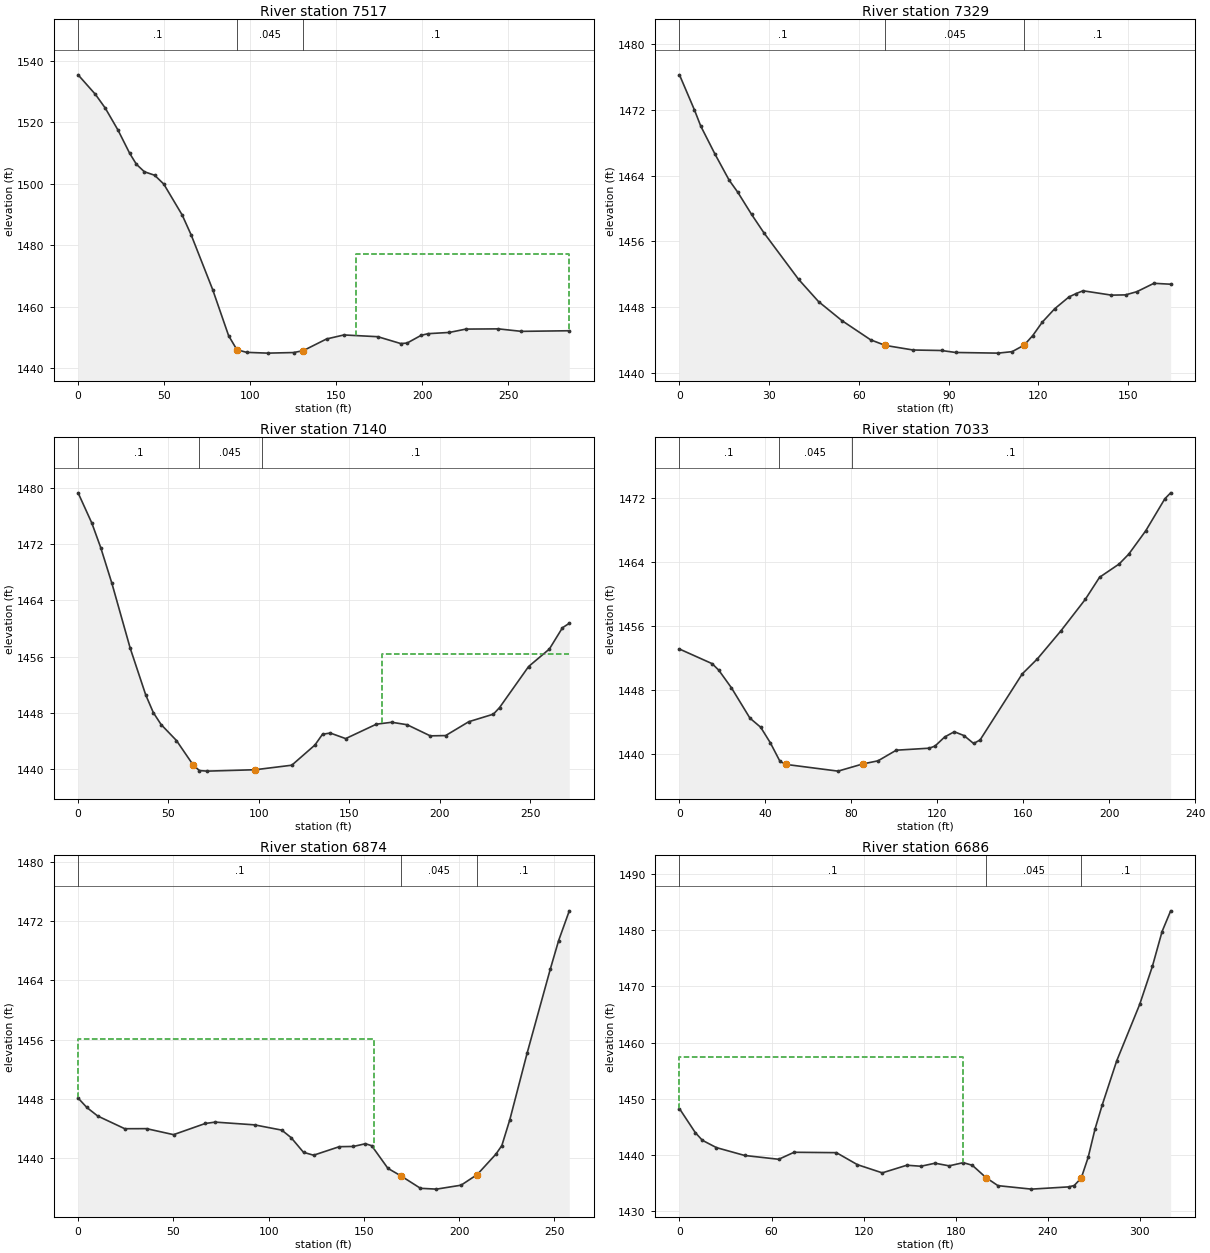
Type RM Length L Ch R = 1 ,7517    ,191.2,187.9,182.3
XS GIS Cut Line= 4
2154122.73037002629344.3110147952154183.66484892629397.853263522
2154236.95656775629451.6323773372154265.52689216629577.137730997
#Sta/Elev= 30
       0 1535.52    10.1 1529.13    15.8 1524.67    23.2 1517.51      30 1509.94
    33.9 1506.38    38.5 1503.96    44.5 1502.81    49.8 1499.94    60.5 1489.86
    65.8 1483.27    78.2  1465.6    87.5 1450.54    92.3 1445.99      98 1445.13
   110.3 1444.88   125.2 1445.07   130.8 1445.67   144.4 1449.49   154.5  1450.8
   174.2 1450.23   187.5    1448   191.2 1448.15   199.4 1450.68   203.5 1451.22
   215.8 1451.62   225.4 1452.71   244.3 1452.78   257.7 1451.97   285.5 1452.17
#Mann= 3 ,-1,0
       0      .1       0    92.3    .045       0   130.8      .1       0
#XS Ineff= 2 , 0
                          161.75         1477.19
Permanent Ineff=
       F       F
Bank Sta=92.3,130.8
XS Rating Curve= 0 ,0
Exp/Cntr(USF)=0,0
Exp/Cntr=0.3,0.1

Type RM Length L Ch R = 1 ,7329    ,195.4,188.5,183.5
XS GIS Cut Line= 2
2154046.14761544629536.3229818392154184.91776257629624.074692529
#Sta/Elev= 30
       0 1476.28       5 1472.01     7.1 1470.05    11.9 1466.61    16.6 1463.46
    19.5 1461.98    24.1 1459.29    28.2 1457.06    39.8 1451.39    46.5 1448.67
    54.3 1446.36    63.9 1444.02    68.8 1443.34    78.1 1442.78    87.6 1442.72
    92.3 1442.48   106.5  1442.4   111.2 1442.58   115.2 1443.37   118.1 1444.54
   121.3 1446.18   125.4 1447.79   130.2 1449.24   132.6 1449.65   134.9 1449.99
   144.4 1449.46   149.1 1449.49   152.9 1449.88   158.6  1450.9   164.2 1450.79
#Mann= 3 ,-1,0
       0      .1       0    68.8    .045       0   115.2      .1       0
Bank Sta=68.8,115.2
XS Rating Curve= 0 ,0
Exp/Cntr(USF)=0,0
Exp/Cntr=0.3,0.1

Type RM Length L Ch R = 1 ,7140    ,101.9,107.7,108.1
XS GIS Cut Line= 3
2153961.05502056629724.3194767152154166.35924185629798.773379406
2154193.85789847629844.470764587
#Sta/Elev= 30
       0 1479.25     7.6 1474.95    12.5 1471.48    18.7 1466.39    28.8  1457.2
    37.4 1450.55    41.6 1448.04    45.9 1446.34    54.4 1444.07    63.71440.573
    67.1  1439.8    71.4 1439.72      981439.919   118.2 1440.56     131 1443.43
   135.2 1444.96   139.5 1445.13     148 1444.34     165 1446.39   173.5 1446.66
     182 1446.31   194.8 1444.73   203.3 1444.77   216.1 1446.74   229.7 1447.81
   233.1 1448.74   249.2 1454.58   260.7 1457.07   267.9 1460.08   271.7 1460.72
#Mann= 3 ,-1,0
       0      .1       0      67    .045       0   101.5      .1       0
#XS Ineff= 2 , 0
                          168.34         1456.38
Permanent Ineff=
       F       F
Bank Sta=63.7,98
XS Rating Curve= 0 ,0
Exp/Cntr(USF)=0,0
Exp/Cntr=0.3,0.1

Type RM Length L Ch R = 1 ,7033    ,164.4,158.4,160
XS GIS Cut Line= 2
2153950.67675207629822.0386681462154153.50198681629927.489886291
#Sta/Elev= 30
       0 1453.13    15.2  1451.3    18.3 1450.48    24.2 1448.27    32.8 1444.48
    37.8 1443.34    42.3 1441.39    46.8 1439.06    49.71438.686    73.8 1437.85
    85.31438.748    92.4 1439.14   100.9 1440.47   116.2 1440.72   118.9 1440.98
   123.4 1442.12   127.9 1442.78   132.4  1442.3   136.9 1441.31   139.9 1441.75
   159.5 1450.01   166.6 1451.91   177.5  1455.4   188.9 1459.36   195.5 1462.11
   204.6 1463.77   209.1 1465.01     217 1467.93   225.9 1471.94   228.6 1472.68
#Mann= 3 ,-1,0
       0      .1       0    46.2    .045       0    80.2      .1       0
Bank Sta=49.7,85.3
XS Rating Curve= 0 ,0
Exp/Cntr(USF)=0,0
Exp/Cntr=0.3,0.1

Type RM Length L Ch R = 1 ,6874    ,168.6,188,213.1
XS GIS Cut Line= 3
2153857.44549522629889.4452962812153944.17683718629995.563644091
2154057.43776609630037.398761978
#Sta/Elev= 30
       0 1448.14     4.6 1446.87    10.3 1445.72    24.5 1444.01    35.9 1444.02
    50.1 1443.21    66.8 1444.72      72  1444.9    92.6 1444.53   106.9 1443.82
   111.8 1442.81   118.3 1440.83   123.6 1440.44   137.1 1441.59   144.5 1441.62
   150.8 1441.99   154.1 1441.72   162.6 1438.67   169.4 1437.66   179.7 1435.98
   188.1 1435.87     201  1436.4   209.5 1437.84   219.3 1440.59   222.4 1441.74
   226.6 1445.24   235.7 1454.23   247.9 1465.58   252.2 1469.36   257.8 1473.37
#Mann= 3 ,-1,0
       0      .1       0   169.4    .045       0   209.5      .1       0
#XS Ineff= 2 , 0
          155.49 1456.13
Permanent Ineff=
       F       F
Bank Sta=169.4,209.5
XS Rating Curve= 0 ,0
Exp/Cntr(USF)=0,0
Exp/Cntr=0.3,0.1

Type RM Length L Ch R = 1 ,6686    ,181.3,184.3,192.4
XS GIS Cut Line= 4
2153764.99504952629952.1916745392153856.82823512630114.430302441
2153897.64298428630191.9783258412153924.17257123630229.731968812
#Sta/Elev= 30
       0 1448.22    10.3 1443.95    14.9 1442.58    24.1 1441.27    42.5 1439.87
    64.7 1439.19    74.7 1440.44   102.3 1440.37     116 1438.23   132.2 1436.77
   148.2 1438.13   157.4 1437.95   166.6 1438.49   175.8 1438.02     185 1438.59
   190.9 1438.12   199.8 1435.93   207.6 1434.49   229.4 1433.87   253.7 1434.27
   257.3 1434.51   261.9 1435.84   266.4 1439.52   270.9  1444.6   275.5 1448.81
     285 1456.72     300  1466.8   308.3  1473.6   314.6 1479.79   320.2 1483.48
#Mann= 3 ,-1,0
       0      .1       0   199.8    .045       0   261.9      .1       0
#XS Ineff= 2 , 0
          184.56 1457.51
Permanent Ineff=
       F       F
Bank Sta=199.8,261.9
XS Rating Curve= 0 ,0
Exp/Cntr(USF)=0,0
Exp/Cntr=0.3,0.1

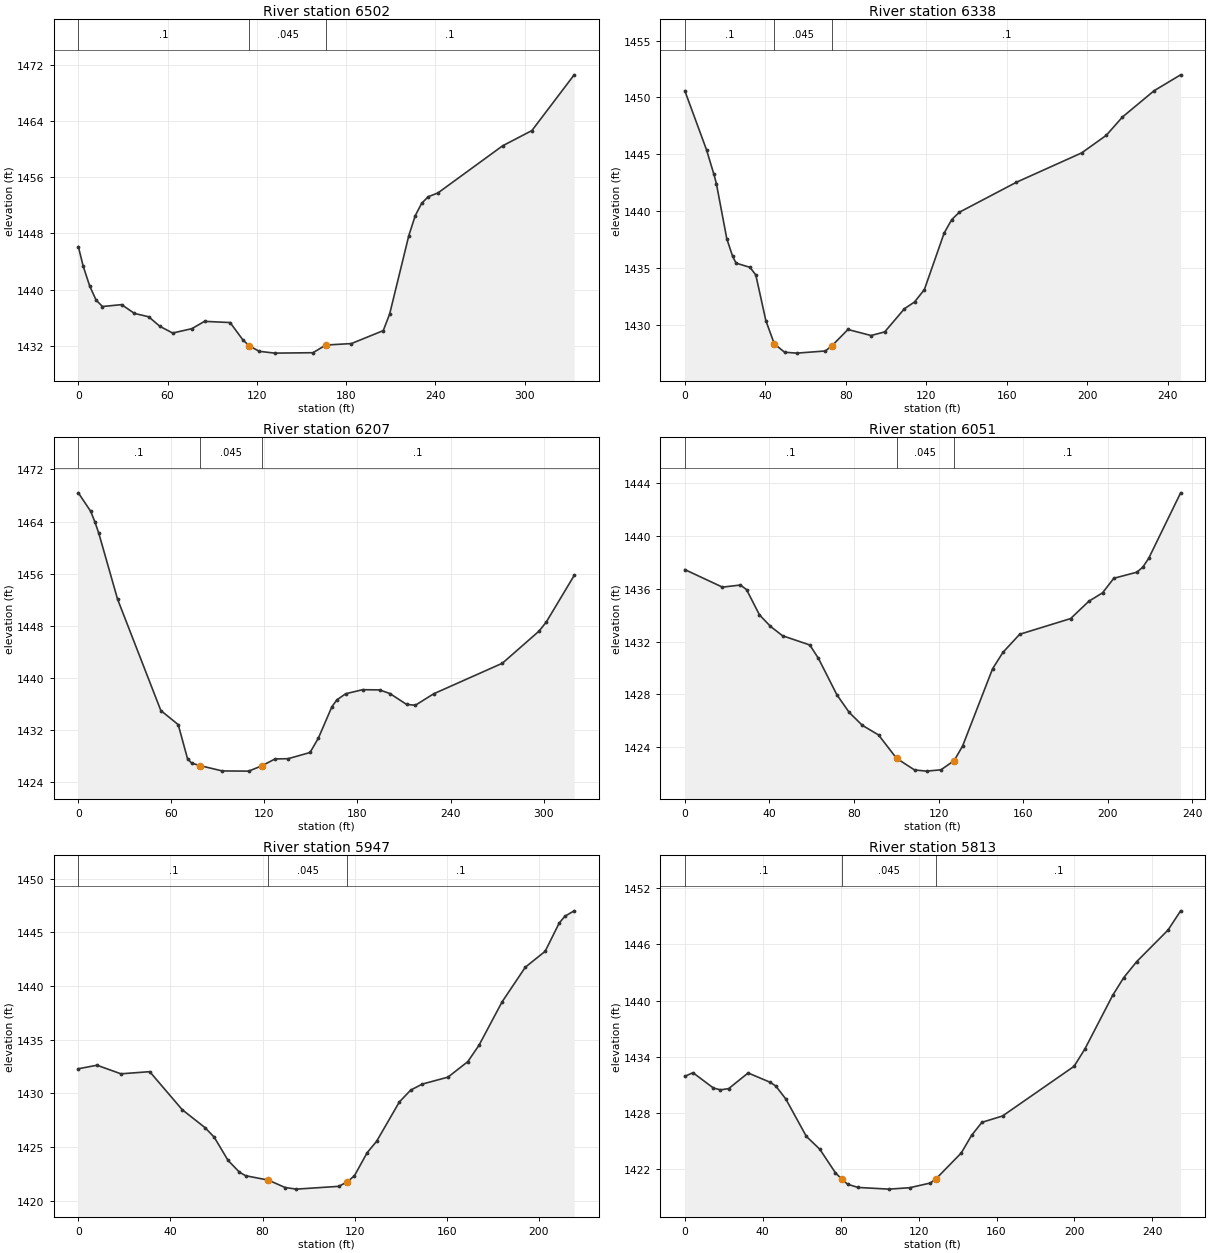
Type RM Length L Ch R = 1 ,6502    ,164.7,163.8,155.9
XS GIS Cut Line= 3
2153642.06371244630042.0667039692153726.04467779630259.017531111
2153811.42532589630312.205475829
#Sta/Elev= 30
       0  1446.1     3.3  1443.3     7.6 1440.52    11.9 1438.51    16.2 1437.58
    29.1 1437.85    37.7  1436.6    47.3 1436.12    54.8 1434.76    63.4 1433.81
    76.3 1434.43    84.8 1435.47     102  1435.3   110.6 1432.83   114.9 1431.99
   121.5 1431.21     132 1430.95   157.7 1431.01   166.3  1432.1   183.5 1432.31
   204.9 1434.15   209.2 1436.51   222.1 1447.68   226.4  1450.5   230.7 1452.26
   235.1  1453.2   241.6 1453.73   285.1 1460.44   304.8 1462.61   333.2 1470.54
#Mann= 3 ,-1,0
       0      .1       0   114.9    .045       0   166.3      .1       0
Bank Sta=114.9,166.3
XS Rating Curve= 0 ,0
Exp/Cntr(USF)=0,0
Exp/Cntr=0.3,0.1

Type RM Length L Ch R = 1 ,6338    ,134.3,130.7,127.5
XS GIS Cut Line= 3
2153507.69416789630176.4362485212153586.07640221 630285.61150347
2153696.65133992630303.807379295
#Sta/Elev= 30
       0 1450.59    10.8 1445.39    14.5 1443.22    15.7 1442.42    20.9 1437.55
    23.8 1436.01    25.5 1435.42    32.4 1435.05    35.3 1434.38    40.3 1430.36
    44.51428.317    49.6 1427.58    55.7  1427.5    69.9 1427.69    73.21428.155
    81.1 1429.58    92.6 1429.05    99.4 1429.37   109.2 1431.41   114.2    1432
   119.1 1433.09   128.9 1438.05   132.7 1439.25   136.5  1439.9   164.9 1442.54
   197.3 1445.12   209.5 1446.66   217.6 1448.28   233.3 1450.59   246.5 1451.99
#Mann= 3 ,-1,0
       0      .1       0    44.5    .045       0    73.2      .1       0
Bank Sta=44.5,73.2
XS Rating Curve= 0 ,0
Exp/Cntr(USF)=0,0
Exp/Cntr=0.3,0.1

Type RM Length L Ch R = 1 ,6207    ,157.7,156.4,152.3
XS GIS Cut Line= 3
2153378.17341511630243.898259862 2153520.9410562630385.266218193
2153604.92202154630469.247183538
#Sta/Elev= 30
       0 1468.41       8 1465.56    10.8 1463.86    13.2  1462.2    25.3 1452.08
    53.2 1434.99    64.4 1432.83    70.4  1427.6      73 1426.93    78.31426.543
    92.8 1425.72   109.8 1425.69   118.3  1426.5   126.8 1427.56   135.3  1427.6
   149.4 1428.55   154.8 1430.77   163.5 1435.58   166.7 1436.63   172.4 1437.57
   183.3 1438.19   194.2 1438.16   200.9  1437.6   211.6 1435.94   217.3  1435.8
   229.1 1437.56   273.4 1442.25     297 1447.17   301.7 1448.57   319.7 1455.72
#Mann= 3 ,-1,0
       0      .1       0    78.3    .045       0   118.3      .1       0
Bank Sta=78.3,118.3
XS Rating Curve= 0 ,0
Exp/Cntr(USF)=0,0
Exp/Cntr=0.3,0.1

Type RM Length L Ch R = 1 ,6051    ,104.5,103.5,101.7
XS GIS Cut Line= 2
2153273.19720843630367.0703423682153452.35660116630518.236079989
#Sta/Elev= 30
       0 1437.45    17.8 1436.12    26.3 1436.28    29.2 1435.93    35.3 1434.02
    40.5 1433.15    46.2 1432.44    59.1 1431.74    63.2 1430.72    71.9 1427.97
    77.7 1426.64    83.9 1425.66    91.6 1424.93   100.1 1423.16   108.6 1422.28
   114.3 1422.19   121.1 1422.29   127.3 1422.98   131.3 1424.08   145.5 1429.94
   150.4 1431.18   158.3 1432.55   182.4 1433.74     191 1435.05   197.5 1435.69
   202.8 1436.79   213.7 1437.25   216.5 1437.63   219.3  1438.3   234.4 1443.26
#Mann= 3 ,-1,0
       0      .1       0   100.1    .045       0   127.3      .1       0
Bank Sta=100.1,127.3
XS Rating Curve= 0 ,0
Exp/Cntr(USF)=0,0
Exp/Cntr=0.3,0.1

Type RM Length L Ch R = 1 ,5947    ,133.2,134.8,136.8
XS GIS Cut Line= 2
2153215.81021544630462.2487697592153389.37087715630589.619900533
#Sta/Elev= 30
       0  1432.3     8.1 1432.63    18.5 1431.83      31 1432.03    45.1 1428.49
      55 1426.82      59 1425.93      65 1423.77    69.9 1422.68    72.6 1422.34
    82.5 1421.93    89.8 1421.24    94.7 1421.09   113.1 1421.35   116.8 1421.77
   119.9 1422.34   125.4 1424.48   129.5 1425.54   139.4 1429.21   144.3 1430.31
   149.3 1430.87   160.5 1431.52   169.1 1432.96     174  1434.5     184 1438.53
   194.1 1441.76   202.7 1443.24   208.8 1445.87   211.3 1446.51   215.3 1447.01
#Mann= 3 ,-1,0
       0      .1       0    82.5    .045       0   116.8      .1       0
Bank Sta=82.5,116.8
XS Rating Curve= 0 ,0
Exp/Cntr(USF)=0,0
Exp/Cntr=0.3,0.1

Type RM Length L Ch R = 1 ,5813    ,126,126.7,128.5
XS GIS Cut Line= 2
2153129.11203564 630554.417040042153321.11241366630721.457368916
#Sta/Elev= 30
       0 1431.92     4.2 1432.31    14.7 1430.67    18.3 1430.48    22.5 1430.61
    32.5 1432.28    43.8 1431.29    46.7 1430.89    51.8 1429.52    62.4 1425.51
    69.3 1424.14    77.3 1421.63    80.7 1420.92    83.6  1420.4    88.9 1420.06
   104.8 1419.88   115.4 1420.03     126 1420.53   128.9 1420.97   141.9 1423.74
   147.2 1425.62   152.5 1427.01   163.1 1427.69   199.8 1432.99   205.3 1434.82
   219.6 1440.56   225.3 1442.46     232 1444.18     248 1447.53   254.5 1449.59
#Mann= 3 ,-1,0
       0      .1       0    80.7    .045       0   128.9      .1       0
Bank Sta=80.7,128.9
XS Rating Curve= 0 ,0
Exp/Cntr(USF)=0,0
Exp/Cntr=0.3,0.1