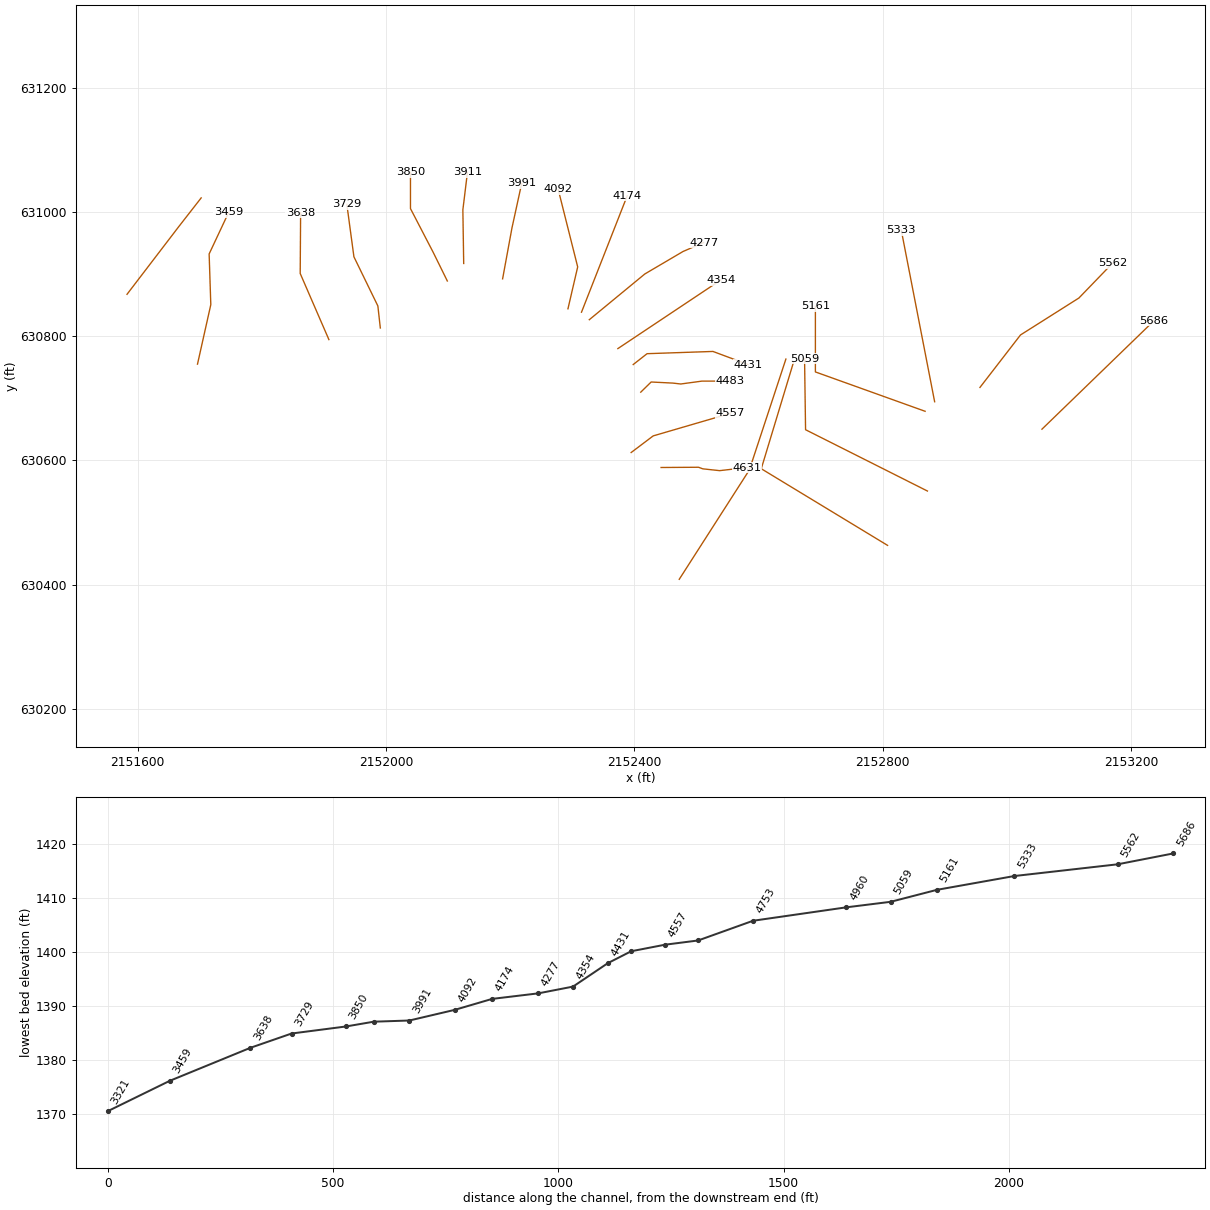
HEC-RAS study LFRFLIKANA.prj: LFRFLIKANA

--- LFRFLIKANA.g01 (geometry) --- (continued)

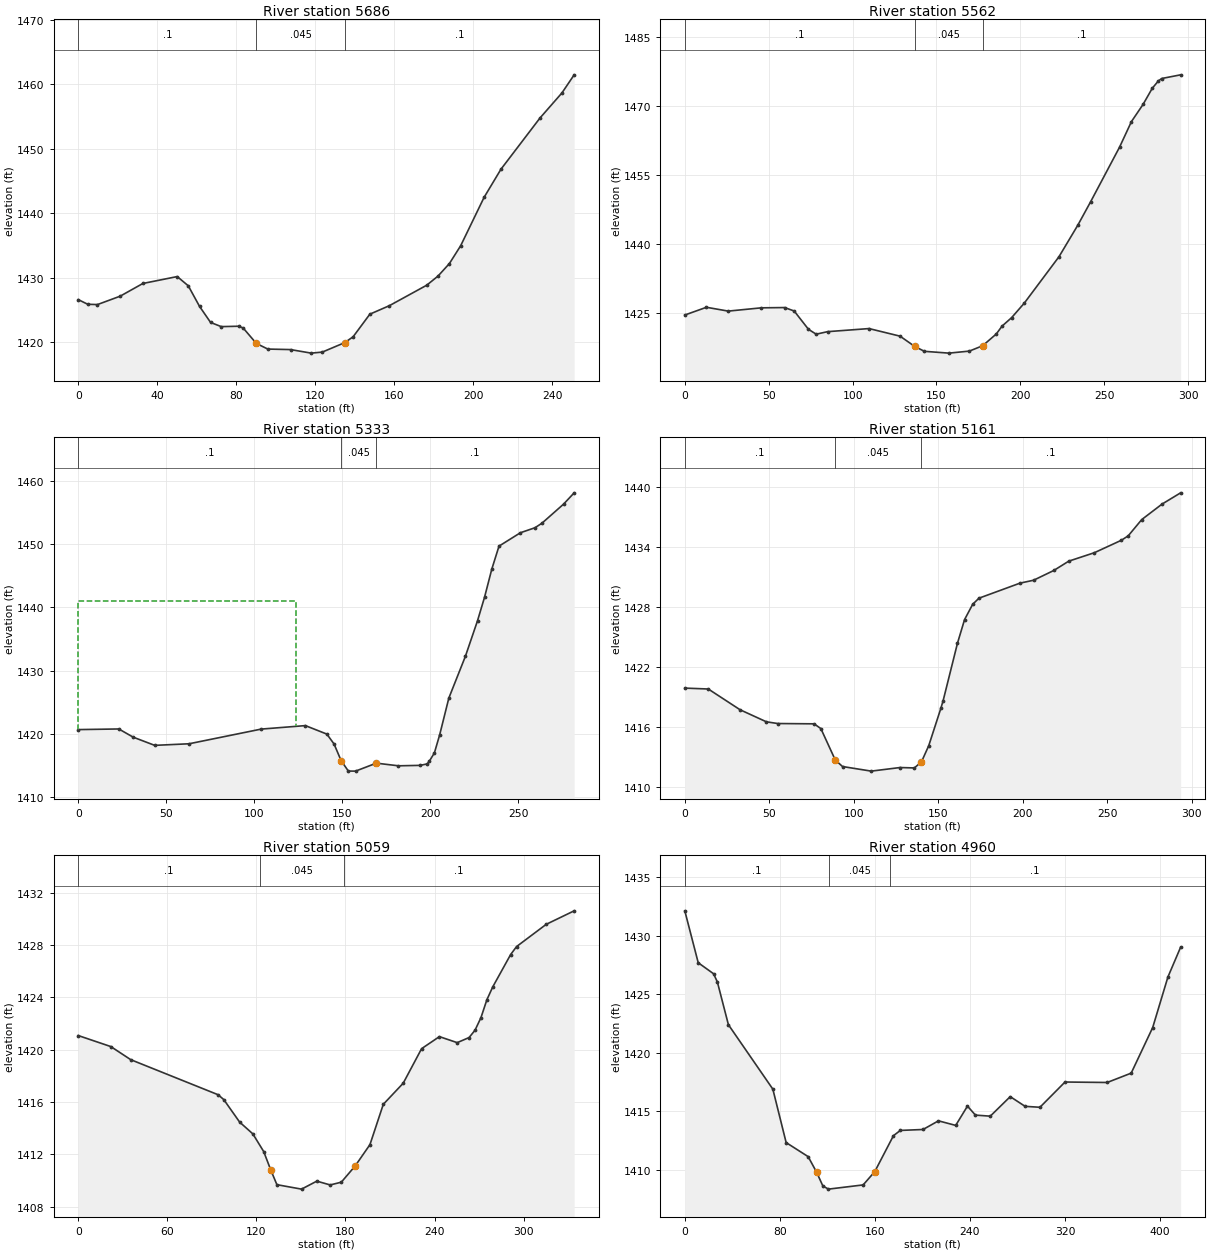
Type RM Length L Ch R = 1 ,5686    ,129.5,124,118.5
XS GIS Cut Line= 2
2153056.15189199630650.4172290492153236.63224733630825.137573046
#Sta/Elev= 30
       0  1426.6     4.8 1425.88     9.7 1425.84    21.2 1427.14    32.7 1429.11
    50.1 1430.18    55.7 1428.75    61.4 1425.56      67 1423.07    72.4 1422.42
    81.2 1422.48    83.5 1422.21    90.2 1419.81      96 1418.94   107.5 1418.86
     118 1418.31   123.6 1418.47   134.9 1419.93   139.2 1420.84   147.7 1424.35
   157.6 1425.67   176.5 1428.84   182.2 1430.25     188  1432.2   193.7 1434.96
   205.6 1442.48   214.1 1446.82   233.9 1454.77     245 1458.65   251.2 1461.46
#Mann= 3 ,-1,0
       0      .1       0    90.2    .045       0   134.9      .1       0
Bank Sta=90.2,134.9
XS Rating Curve= 0 ,0
Exp/Cntr(USF)=0,0
Exp/Cntr=0.3,0.1

Type RM Length L Ch R = 1 ,5562    ,199.8,229.1,255.5
XS GIS Cut Line= 4
2152956.31169542630717.6173613552153021.59182395630802.097527683
2153115.67200918630861.6176448692153169.43211502630917.297754494
#Sta/Elev= 30
       0 1424.56    12.9 1426.24    25.9 1425.41    45.6 1426.12    59.5 1426.18
    65.2 1425.43    73.7 1421.46    78.3  1420.4    85.1 1420.95   109.8 1421.62
   128.3 1419.97     137 1417.75   142.8 1416.68   157.4 1416.29   169.6 1416.73
   177.5 1417.89   185.6 1420.43   189.1 1422.16   194.8    1424   202.3 1427.13
     223 1437.21   234.2 1444.04   241.8  1449.1   259.1 1460.99   266.2 1466.55
   273.1 1470.26   278.6 1473.77   282.2 1475.35   284.2 1475.89   295.5 1476.69
#Mann= 3 ,-1,0
       0      .1       0     137    .045       0   177.5      .1       0
Bank Sta=137,177.5
XS Rating Curve= 0 ,0
Exp/Cntr(USF)=0,0
Exp/Cntr=0.3,0.1

Type RM Length L Ch R = 1 ,5333    ,151.4,171.9,189.1
XS GIS Cut Line= 2
2152883.35155177630694.5773159932152829.59144593 630971.05786034
#Sta/Elev= 30
       0 1420.68      23 1420.78    31.2 1419.48    43.4 1418.19    62.9 1418.44
   103.9 1420.76     129 1421.31   141.2 1419.97   145.3  1418.4   149.3 1415.78
   153.4 1414.13   157.5 1414.12   169.3 1415.38   181.9 1414.96   194.2 1415.03
   198.2 1415.26   199.4 1415.68   202.3    1417   205.3 1419.86   210.5 1425.66
   219.9 1432.25   226.8 1437.88   230.8  1441.6   234.9 1446.02     239 1449.66
   251.2 1451.78   259.4 1452.56   263.4 1453.28   275.7  1456.3   281.7 1458.08
#Mann= 3 ,-1,0
       0      .1       0   149.3    .045       0   169.3      .1       0
#XS Ineff= 2 , 0
          123.55 1441.03
Permanent Ineff=
       F       F
Bank Sta=149.3,169.3
XS Rating Curve= 0 ,0
Exp/Cntr(USF)=0,0
Exp/Cntr=0.3,0.1

Type RM Length L Ch R = 1 ,5161    ,104.7,102.3,96.3
XS GIS Cut Line= 3
2152867.99152153630679.2172857522152691.35117376630742.577410498
2152691.35117376630848.177618408
#Sta/Elev= 30
       0 1419.88    13.9 1419.79    32.7 1417.71    48.3  1416.5      55 1416.33
    76.5  1416.3    80.5 1415.82      89 1412.68    93.3 1412.02   110.3 1411.56
   127.3 1411.92   135.8 1411.88     140 1412.49   144.3 1414.11   151.5 1417.87
   152.8 1418.61   161.3 1424.38   165.5 1426.75   170.3 1428.28     174 1428.89
   198.3  1430.4   206.3 1430.69   218.3 1431.67   227.1  1432.6   242.3 1433.45
   258.3  1434.7   262.3 1435.14   270.3 1436.77   282.3 1438.32   293.3 1439.45
#Mann= 3 ,-1,0
       0      .1       0      89    .045       0     140      .1       0
Bank Sta=89,140
XS Rating Curve= 0 ,0
Exp/Cntr(USF)=0,0
Exp/Cntr=0.3,0.1

Type RM Length L Ch R = 1 ,5059    ,99.3,98.1,94.8
XS GIS Cut Line= 3
 2152871.7299063630550.8310894522152675.53384096 630649.53344425
2152673.91531513630763.958997903
#Sta/Elev= 30
       0 1421.08    21.9 1420.24    35.3 1419.24    94.2 1416.56      98 1416.19
   108.7 1414.47   117.6 1413.57   124.9 1412.22   129.61410.834   133.8 1409.69
   150.4 1409.35   160.7 1409.96   169.7 1409.67   177.2 1409.88   186.6 1411.13
   196.5 1412.75   205.5 1415.83   218.9 1417.44   231.3 1420.08   243.3    1421
   255.3 1420.54   263.3 1420.93   267.3 1421.49   271.3 1422.45   275.3 1423.82
   279.3 1424.81   291.3 1427.27   295.3 1427.88   315.3 1429.58   334.1 1430.61
#Mann= 3 ,-1,0
       0      .1       0   122.2    .045       0     179      .1       0
Bank Sta=129.6,186.6
XS Rating Curve= 0 ,0
Exp/Cntr(USF)=0,0
Exp/Cntr=0.3,0.1

Type RM Length L Ch R = 1 ,4960    ,250.7,207.3,168.9
XS GIS Cut Line= 3
 2152807.5589723630463.3271305382152604.21392879630586.712232106
2152656.21705486630758.441166206
#Sta/Elev= 30
       0 1432.13    11.3 1427.69    24.2 1426.75    27.4 1426.05    36.7 1422.39
    74.1 1416.88    85.3 1412.31   103.8 1411.11   110.91409.784   116.2  1408.6
   120.9 1408.33   150.1 1408.69   159.9 1409.83   175.6  1412.9   181.4 1413.35
   200.5 1413.43   213.5 1414.17     228 1413.78   237.9 1415.43   244.6 1414.66
   257.1 1414.57   273.9 1416.24   286.4 1415.41   298.9 1415.33     320 1417.49
   355.5 1417.45   375.7 1418.25   393.8 1422.15   406.6 1426.47   417.3 1429.02
#Mann= 3 ,-1,0
       0      .1       0   121.7    .045       0   172.5      .1       0
Bank Sta=110.9,159.9
XS Rating Curve= 0 ,0
Exp/Cntr(USF)=0,0
Exp/Cntr=0.3,0.1

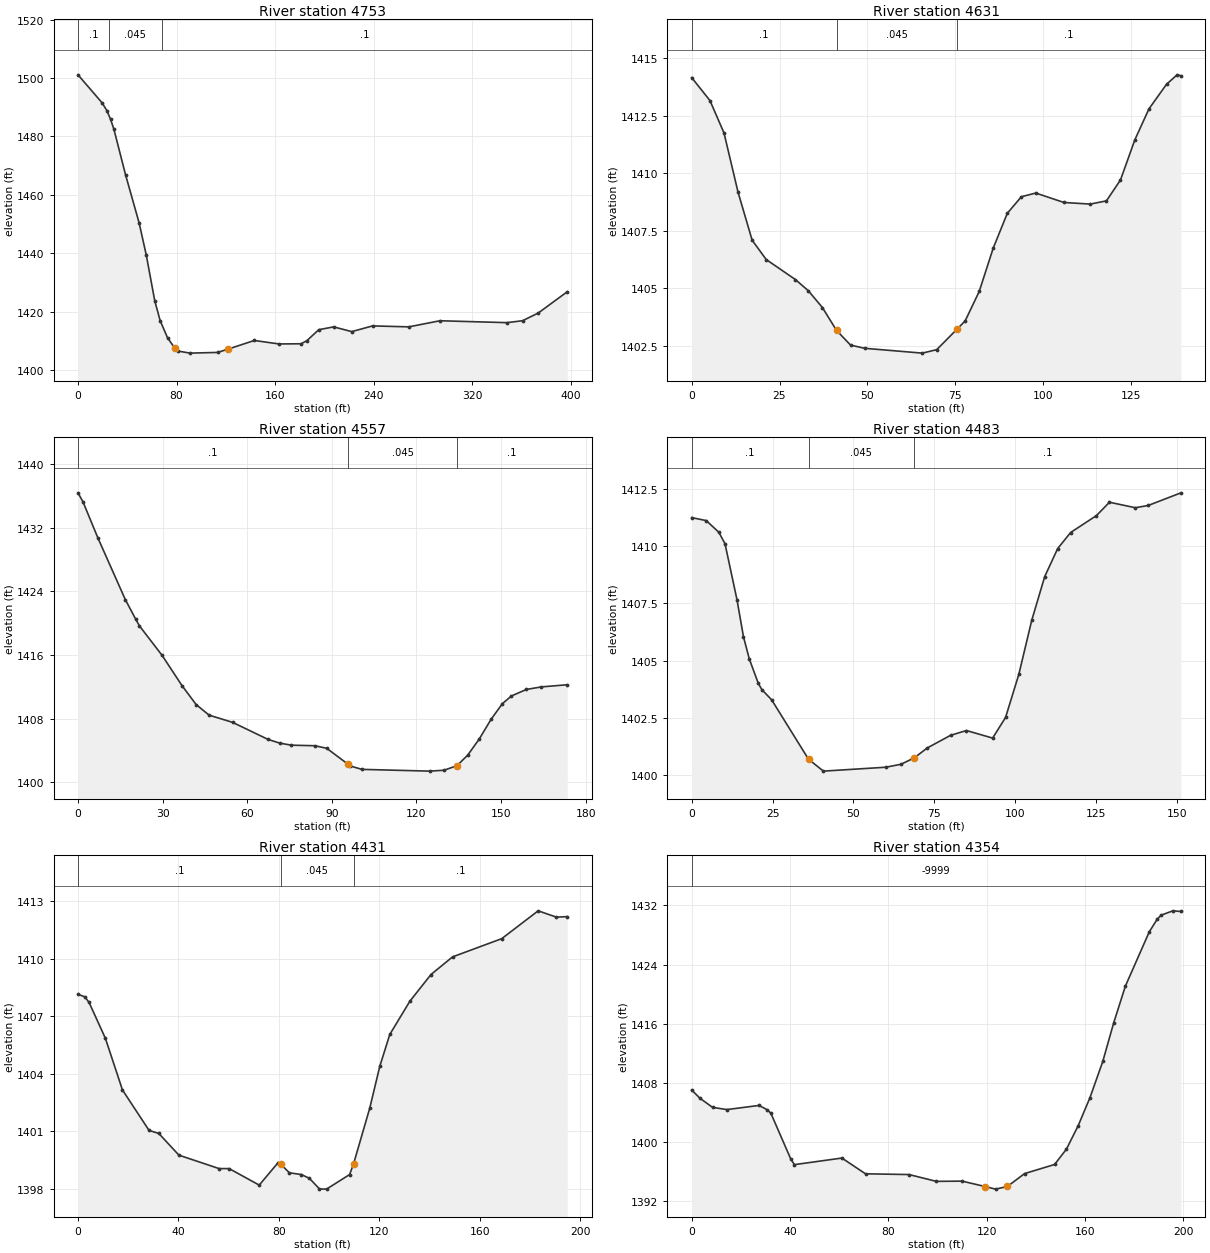
Type RM Length L Ch R = 1 ,4753    ,142.3,121.9,92.6
XS GIS Cut Line= 3
2152472.15143762630408.7016552722152584.98276395630584.641669857
2152643.87395404630763.305520426
#Sta/Elev= 30
       0 1501.08    19.6 1491.47    23.5 1488.79    26.4 1485.88    29.1 1482.51
    38.6 1466.86    49.6 1450.41    55.4 1439.42    62.3 1423.73    66.7 1416.93
    72.7 1411.05    78.81407.428    81.3 1406.54    90.9 1405.84   113.3 1406.08
   121.91407.228   143.1 1410.17   163.1 1408.98   181.1 1409.04   185.9 1410.15
   195.4 1413.86   207.5 1414.82   222.2  1413.2   239.1 1415.16   268.5 1414.83
   293.8 1416.92   348.2 1416.27   360.8 1416.93   373.5 1419.55   397.1 1426.85
#Mann= 3 ,-1,0
       0      .1       0    24.9    .045       0      68      .1       0
Bank Sta=78.8,121.9
XS Rating Curve= 0 ,0
Exp/Cntr(USF)=0,0
Exp/Cntr=0.3,0.1

Type RM Length L Ch R = 1 ,4631    ,64.5,73.8,81.5
XS GIS Cut Line= 5
2152442.94285686630588.7167501182152503.26189594630589.097710559
2152509.98461187630586.5766920862152537.08556046630583.635503867
2152581.20338373630588.677540813
#Sta/Elev= 30
       0 1414.17     5.2 1413.17     9.2 1411.76    13.2 1409.18    17.2  1407.1
    21.2 1406.26    29.5 1405.39    33.2  1404.9    37.2 1404.17    41.2 1403.18
    45.2 1402.54    49.2  1402.4    65.6 1402.19    69.7 1402.34    75.61403.248
    77.8 1403.59    81.8 1404.87    85.8 1406.76    89.8 1408.27    93.8 1408.99
    97.9 1409.15   105.9 1408.74   113.4 1408.67     118 1408.81     122 1409.72
   126.1 1411.47   130.1 1412.81   135.1 1413.88   138.1 1414.29   139.2 1414.25
#Mann= 3 ,-1,0
       0      .1       0    41.2    .045       0    75.6      .1       0
Bank Sta=41.2,75.6
XS Rating Curve= 0 ,0
Exp/Cntr(USF)=0,0
Exp/Cntr=0.3,0.1

Type RM Length L Ch R = 1 ,4557    ,85.6,74.8,75.9
XS GIS Cut Line= 3
 2152394.7414544630612.8174513482152430.22304233630639.596008271
2152554.07386809630675.747060116
#Sta/Elev= 30
       0 1436.36     1.8  1435.2       7 1430.74    16.8 1422.93    20.5 1420.46
    21.8 1419.64    29.8 1415.95    36.9 1412.13    41.9 1409.76    46.5 1408.43
    54.8 1407.53    67.3  1405.4    71.5 1404.92    75.7 1404.66      84 1404.59
    88.2 1404.27    95.7 1402.28    96.5 1402.05   100.7 1401.62   124.7  1401.4
   129.8 1401.51   134.4 1402.09   138.2 1403.41   142.3 1405.44   146.5 1407.92
   150.5 1409.88   153.7 1410.84     159 1411.66   164.3 1411.98   173.5 1412.25
#Mann= 3 ,-1,0
       0      .1       0    95.7    .045       0   134.4      .1       0
Bank Sta=95.7,134.4
XS Rating Curve= 0 ,0
Exp/Cntr(USF)=0,0
Exp/Cntr=0.3,0.1

Type RM Length L Ch R = 1 ,4483    ,58.1,51.7,59.9
XS GIS Cut Line= 6
2152410.18817415630709.9978065522152426.90986125630726.363713082
2152462.13213835630724.5848101982152474.58445854630723.161687891
 2152508.7393939630727.7868353892152554.27930772630727.786835389
#Sta/Elev= 30
       0 1411.24     4.5 1411.11     8.4  1410.6    10.3  1410.1      14 1407.66
      16 1406.05    17.8 1405.08    20.6 1404.01    21.7 1403.74    24.7  1403.3
    36.1 1400.71    40.7 1400.19      60 1400.36    64.7 1400.49    68.8 1400.77
    72.8  1401.2      80 1401.75    84.9 1401.96      93 1401.63      97 1402.53
   101.1 1404.41   105.1 1406.77   109.1 1408.67   113.1 1409.89   117.1 1410.59
   125.1 1411.33   129.1 1411.91   137.1 1411.67   141.1 1411.77   151.2 1412.32
#Mann= 3 ,-1,0
       0      .1       0    36.1    .045       0    68.8      .1       0
Bank Sta=36.1,68.8
XS Rating Curve= 0 ,0
Exp/Cntr(USF)=0,0
Exp/Cntr=0.3,0.1

Type RM Length L Ch R = 1 ,4431    ,65.7,77.2,87.2
XS GIS Cut Line= 4
2152398.04251128630754.4733129042152420.33565992630771.946321296
2152526.37874533630775.5614264812152583.01539323630754.473312904
#Sta/Elev= 30
       0 1408.14     2.7 1408.01     4.4 1407.72    10.9 1405.85    17.7 1403.16
    28.3 1401.05    32.2 1400.89    40.2 1399.76    56.2 1399.06    60.2 1399.06
    72.2  1398.2    79.7 1399.37    80.7  1399.3    84.2 1398.84      89 1398.75
    92.2 1398.55    96.2    1398      99 1397.99   108.2 1398.75   109.8 1399.32
   116.2  1402.2   120.2 1404.38   124.2 1406.05   132.2 1407.78   140.6 1409.17
   149.2 1410.09   168.8 1411.04   183.3 1412.49   190.6 1412.16   194.9 1412.19
#Mann= 3 ,-1,0
       0      .1       0    80.7    .045       0   109.8      .1       0
Bank Sta=80.7,109.8
XS Rating Curve= 0 ,0
Exp/Cntr(USF)=0,0
Exp/Cntr=0.3,0.1

Type RM Length L Ch R = 1 ,4354    ,76.7,76.9,79.8
XS GIS Cut Line= 2
2152373.36948373630780.1620365392152538.93039551630890.535977721
#Sta/Elev= 30
       0 1407.05     3.4 1405.92     8.5  1404.7    14.3  1404.4    27.4 1404.96
    30.7 1404.38    32.2 1403.91    40.3 1397.72    41.8 1396.96    61.1 1397.85
    70.7 1395.72    88.4 1395.62    99.5  1394.7     110 1394.73  119.47 1393.99
   123.6 1393.65   128.4 1394.01   135.4 1395.75   147.6 1396.98   152.4 1399.04
   157.2 1402.22     162 1406.02   167.2  1410.9   171.6 1416.07   176.4 1421.09
   186.1 1428.41   189.3 1430.11   190.9 1430.67   195.7 1431.26     199 1431.17
#Mann= 1 ,-1,0
       0   -9999       0
Bank Sta=119.47,128.4
XS Rating Curve= 0 ,0
Exp/Cntr(USF)=0,0
Exp/Cntr=0.3,0.1

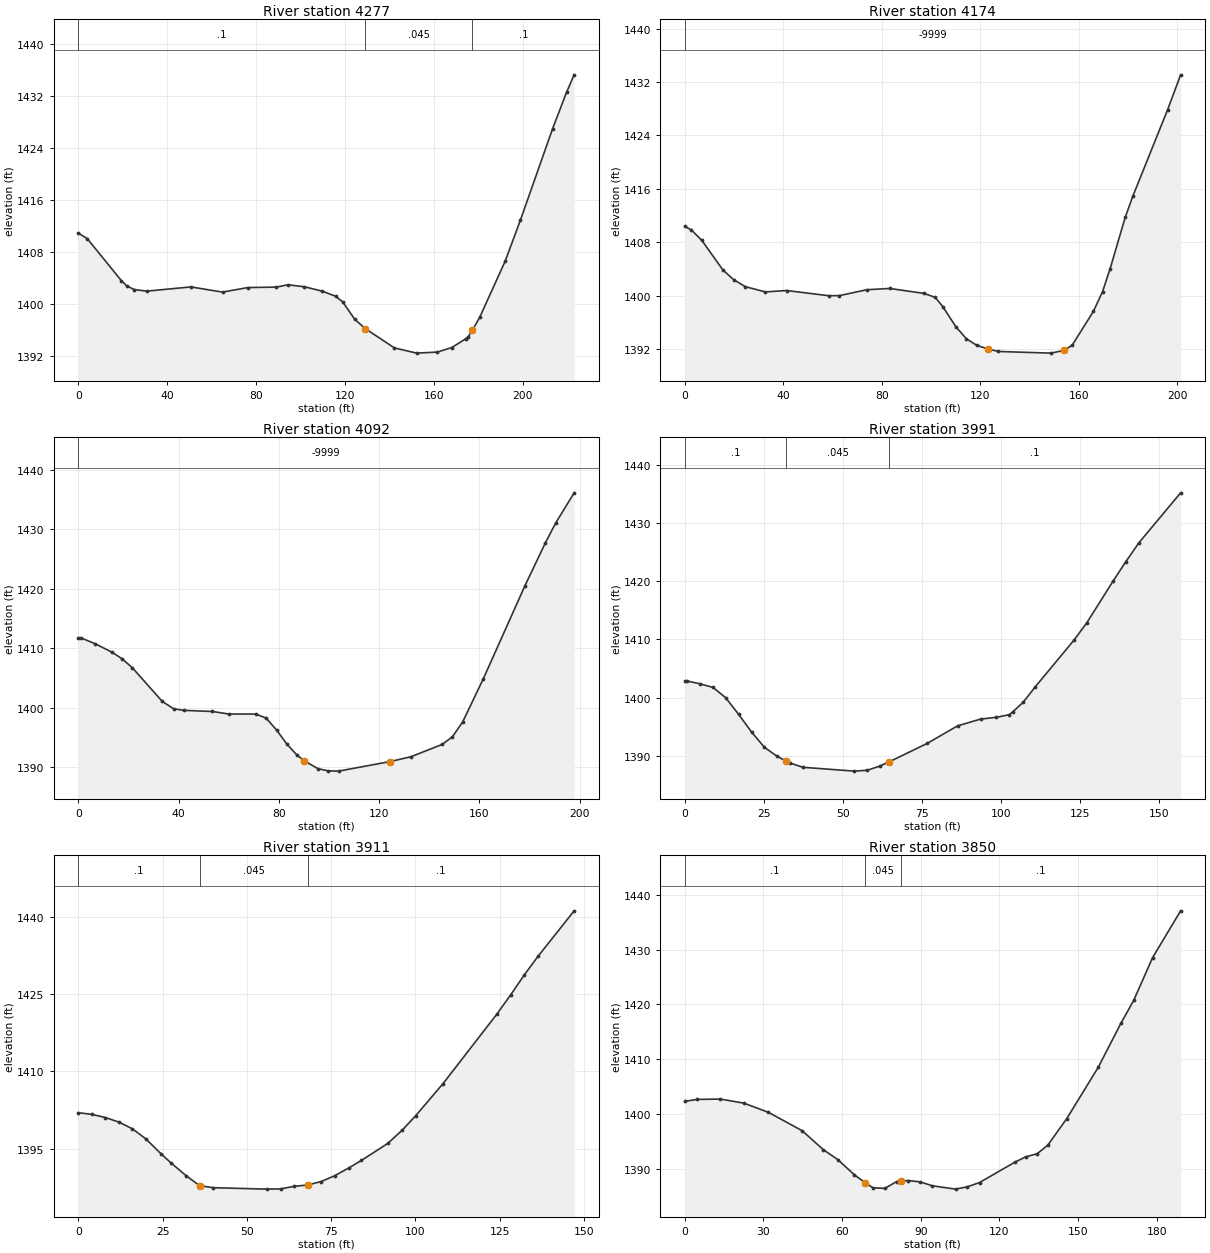
Type RM Length L Ch R = 1 ,4277    ,79.8,102.7,117.3
XS GIS Cut Line= 4
2152327.35240513  630826.66664142152416.72055474630900.282555347
2152478.17734287630936.4336071922152511.31580707 630950.89402793
#Sta/Elev= 30
       0 1410.87       4 1410.03    19.4 1403.54    21.8 1402.75    25.1 1402.19
    30.8 1401.94    50.7 1402.59    64.9 1401.79    76.3 1402.49    89.2 1402.56
    94.3 1402.92   101.8 1402.61   109.9 1401.93   115.8 1401.15     119 1400.29
   124.4 1397.62   129.1 1396.19   142.3  1393.2   152.3  1392.4   161.6 1392.56
   168.1 1393.26   174.5 1394.63   175.5 1394.92   177.4 1395.91   180.7 1397.93
   192.2 1406.59     199 1412.86   213.5 1426.94   219.8 1432.56   223.2 1435.23
#Mann= 3 ,-1,0
       0      .1       0   129.1    .045       0   177.4      .1       0
Bank Sta=129.1,177.4
XS Rating Curve= 0 ,0
Exp/Cntr(USF)=0,0
Exp/Cntr=0.3,0.1

Type RM Length L Ch R = 1 ,4174    ,61.9,82.5,87.8
XS GIS Cut Line= 2
2152314.77591002630838.7556102532152388.35853747631026.118782013
#Sta/Elev= 30
       0 1410.36     2.6 1409.85     6.9 1408.27    15.5 1403.82    19.8 1402.39
    24.5 1401.34    32.7 1400.54    41.3 1400.75    58.5 1399.97    62.8 1399.99
    73.9 1400.87    83.2 1401.06    97.1 1400.32   101.7 1399.72   104.8 1398.31
     110 1395.35   114.3 1393.53   118.6 1392.52   122.9 1392.02   127.2 1391.62
   148.7 1391.37   154.1 1391.79   157.3 1392.57   165.9 1397.63   169.6 1400.58
   172.7 1404.05   178.8 1411.71   181.9 1414.89     196 1427.82   201.3 1433.07
#Mann= 1 ,-1,0
       0   -9999       0
Bank Sta=122.9,154.1
XS Rating Curve= 0 ,0
Exp/Cntr(USF)=0,0
Exp/Cntr=0.3,0.1

Type RM Length L Ch R = 1 ,4092    ,113.4,101,94.2
XS GIS Cut Line= 3
2152292.97365003630844.206175249 2152308.6440244630911.656917083
2152277.30327567631036.338591382
#Sta/Elev= 30
       0 1411.76       1 1411.75     6.8 1410.73    13.3 1409.36    17.4 1408.24
    21.5 1406.74    33.5 1401.06      38 1399.83    42.1 1399.56    53.5 1399.37
    60.1 1398.94    70.8 1398.94    74.9 1398.26    79.1 1396.25    83.2 1393.89
    87.3 1392.02    90.21391.065    95.6 1389.76    99.7 1389.39   103.8 1389.35
   124.31390.953   132.7 1391.77   145.1 1393.83   149.2  1395.1   153.3  1397.6
   161.6  1404.9   178.1 1420.44   186.3 1427.69   190.4 1431.02   197.8 1436.11
#Mann= 1 ,-1,0
       0   -9999       0
Bank Sta=90.2,124.3
XS Rating Curve= 0 ,0
Exp/Cntr(USF)=0,0
Exp/Cntr=0.3,0.1

Type RM Length L Ch R = 1 ,3991    ,74.4,79.1,83
XS GIS Cut Line= 3
2152187.76389305630892.4498274472152202.82683132 630974.39221163
2152218.49228712 631046.09179779
#Sta/Elev= 30
       0 1402.85      .7 1402.87     4.8 1402.38     8.9 1401.76    12.9    1400
      17 1397.14    21.1 1394.09    25.1  1391.5    29.2 1389.91    31.9 1389.13
    33.3 1388.76    37.3 1388.03    53.6 1387.37    57.7 1387.52    61.7 1388.26
    64.61388.967    76.6 1392.13    86.2 1395.15    93.5 1396.32    98.5 1396.62
   102.5 1397.07   103.6 1397.53     107 1399.24   110.7 1401.82     123 1409.89
   127.1 1412.91   135.3 1419.99   139.4 1423.39   143.5 1426.61   156.7 1435.21
#Mann= 3 ,-1,0
       0      .1       0    31.9    .045       0    64.6      .1       0
Bank Sta=31.9,64.6
XS Rating Curve= 0 ,0
Exp/Cntr(USF)=0,0
Exp/Cntr=0.3,0.1

Type RM Length L Ch R = 1 ,3911    ,54.7,62,69.1
XS GIS Cut Line= 3
2152125.11559334630917.1982751412152123.77666549631003.559121216
2152131.14076865631063.810874292
#Sta/Elev= 28
       0 1401.97       4 1401.65       8 1401.04      12 1400.16      16 1398.86
      20 1396.92    24.5 1394.02    27.5 1392.24      32 1389.74      36 1387.82
      40 1387.43    55.9 1387.15      60 1387.19      64 1387.69      68 1387.95
      72 1388.61      76 1389.73    80.3 1391.28      84 1392.72    91.8 1396.01
    96.1 1398.59   100.1  1401.4   108.2 1407.61   124.1 1421.03   128.3 1424.86
   132.3 1428.68   136.4 1432.32   147.1 1441.12
#Mann= 3 ,-1,0
       0      .1       0      36    .045       0      68      .1       0
Bank Sta=36,68
XS Rating Curve= 0 ,0
Exp/Cntr(USF)=0,0
Exp/Cntr=0.3,0.1

Type RM Length L Ch R = 1 ,3850    ,120.6,120.3,119.5
XS GIS Cut Line= 4
2152098.75076512630888.9790318532152076.24255652630934.666788751
2152039.42421119631005.5675129852152039.42421119631063.810874292
#Sta/Elev= 30
       0  1402.3     4.7 1402.65    13.6 1402.71    22.5 1401.97    31.9 1400.29
    44.8 1396.92    52.8 1393.48    58.3 1391.67    64.7 1388.87    68.81387.413
    71.8  1386.5    76.3  1386.4    80.8 1387.64    82.41387.708    85.3 1387.83
    89.8 1387.58    94.4 1386.87   103.3 1386.26   107.8 1386.69   112.4 1387.46
   125.9 1391.19     130 1392.15   134.4 1392.73   138.4 1394.26   145.7 1399.16
   157.7 1408.53   166.4 1416.62   171.2 1420.73   178.4 1428.54   189.1  1437.1
#Mann= 3 ,-1,0
       0      .1       0    68.8    .045       0    82.4      .1       0
Bank Sta=68.8,82.4
XS Rating Curve= 0 ,0
Exp/Cntr(USF)=0,0
Exp/Cntr=0.3,0.1

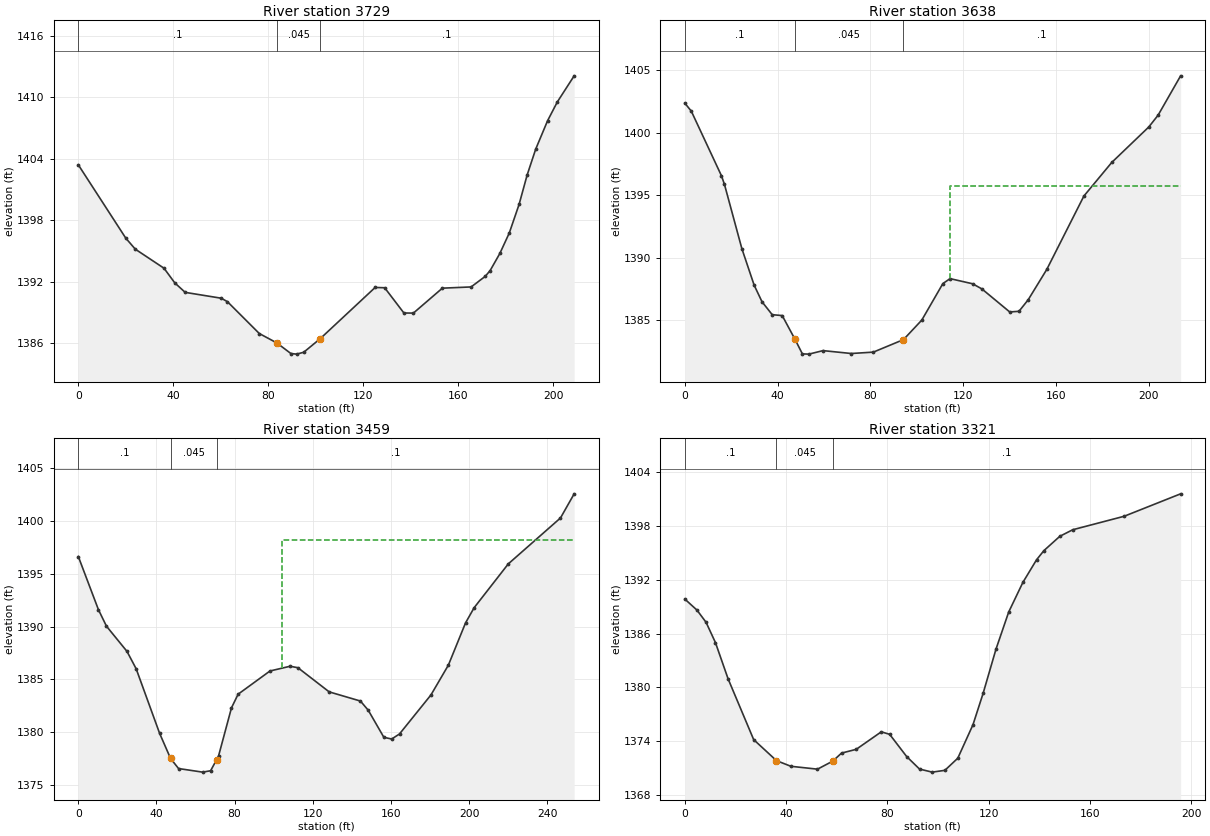
Type RM Length L Ch R = 1 ,3729    ,94.2,91.5,91.4
XS GIS Cut Line= 4
 2151990.8726791630813.3041689182151986.93138293 630848.77188956
2151948.37711765 630927.909697912151936.99623096631012.262152216
#Sta/Elev= 30
       0 1403.41      20 1396.26      24 1395.19    36.1 1393.33    40.6 1391.91
      45 1390.98    60.2 1390.41    62.8 1390.07    76.2 1386.97    83.6 1386.05
    89.5 1385.02    91.9 1384.96    94.9 1385.14   101.81386.453     125 1391.46
     129 1391.43   137.1 1388.97   141.1 1388.96   153.3 1391.39   165.4 1391.51
   171.3 1392.53   173.4  1393.1   177.5 1394.77   181.5 1396.78   185.6 1399.55
     189 1402.42   192.6 1404.94   197.6 1407.71   201.7 1409.54   208.8 1412.09
#Mann= 3 ,-1,0
       0      .1       0    83.6    .045       0   101.8      .1       0
Bank Sta=83.6,101.8
XS Rating Curve= 0 ,0
Exp/Cntr(USF)=0,0
Exp/Cntr=0.3,0.1

Type RM Length L Ch R = 1 ,3638    ,192,178.8,168.8
XS GIS Cut Line= 3
2151908.07602211630794.6393382232151861.88301142630901.084101989
2151862.55247534630998.825834756
#Sta/Elev= 30
       0 1402.36     2.8 1401.72    15.8 1396.56    17.1 1395.87    24.6 1390.74
    29.9 1387.82    33.3 1386.49    37.7 1385.46      42 1385.39    47.5  1383.5
    50.7 1382.33    53.5 1382.31    59.6 1382.59    71.8 1382.36    81.3 1382.47
    94.3 1383.47   102.2 1385.03   111.3 1387.95   114.4 1388.34   124.1 1387.93
   128.1 1387.52   140.1 1385.68   144.1 1385.73   148.1 1386.66   156.1 1389.08
   172.1 1394.94   184.1 1397.62   200.1 1400.46   204.1  1401.4   213.8 1404.54
#Mann= 3 ,-1,0
       0      .1       0    47.5    .045       0    94.3      .1       0
#XS Ineff= 2 , 0
                          114.23         1395.77
Permanent Ineff=
       F       F
Bank Sta=47.5,94.3
XS Rating Curve= 0 ,0
Exp/Cntr(USF)=0,0
Exp/Cntr=0.3,0.1

Type RM Length L Ch R = 1 ,3459    ,145.8,137.8,131.6
XS GIS Cut Line= 4
2151696.52542242630755.1409667622151717.94826796 630850.87430776
2151715.27041227630932.5489063732151746.73521665630999.495298679
#Sta/Elev= 30
       0 1396.64    10.3  1391.6    14.4 1390.04    24.9 1387.65    29.6    1386
    41.6 1379.88    47.2  1377.5    51.3 1376.54    63.6  1376.2    67.7 1376.33
    70.81377.385    71.8 1377.75    78.4  1382.3    81.8 1383.59    98.1 1385.79
   108.4 1386.24   112.4  1386.1   128.4 1383.81   144.4 1382.94   148.4 1382.07
   156.4  1379.5   160.4 1379.34   164.4 1379.82   180.5 1383.52   189.4 1386.34
   198.2 1390.35   202.6 1391.79   220.1 1395.95   246.8  1400.3   253.8 1402.59
#Mann= 3 ,-1,0
       0      .1       0    47.2    .045       0    70.8      .1       0
#XS Ineff= 2 , 0
                          104.28         1398.18
Permanent Ineff=
       F       F
Bank Sta=47.2,70.8
XS Rating Curve= 0 ,0
Exp/Cntr(USF)=0,0
Exp/Cntr=0.3,0.1

Type RM Length L Ch R = 1 ,3321    ,103.4,102.6,104.3
XS GIS Cut Line= 3
2151583.05174663630867.5659075752151666.61994553630976.847398445
2151702.43488792631022.763991248
#Sta/Elev= 30
       0 1389.85     4.8 1388.62     8.4 1387.26    12.1    1385    17.1 1380.96
    27.2 1374.19    36.2 1371.85    41.9 1371.22    52.4  1370.9    58.41371.791
    61.9 1372.69    67.7 1373.11    77.6 1375.06    80.9 1374.78    87.6 1372.31
    92.7 1370.91    97.7 1370.57   102.7 1370.77   107.8 1372.12   113.8 1375.85
   117.8 1379.34   122.9 1384.28   127.9  1388.4   133.5  1391.7   138.9 1394.22
   141.8 1395.24   148.1 1396.84   153.2 1397.57   173.5 1399.07   195.8 1401.57
#Mann= 3 ,-1,0
       0      .1       0    36.2    .045       0    58.4      .1       0
Bank Sta=36.2,58.4
XS Rating Curve= 0 ,0
Exp/Cntr(USF)=0,0
Exp/Cntr=0.3,0.1