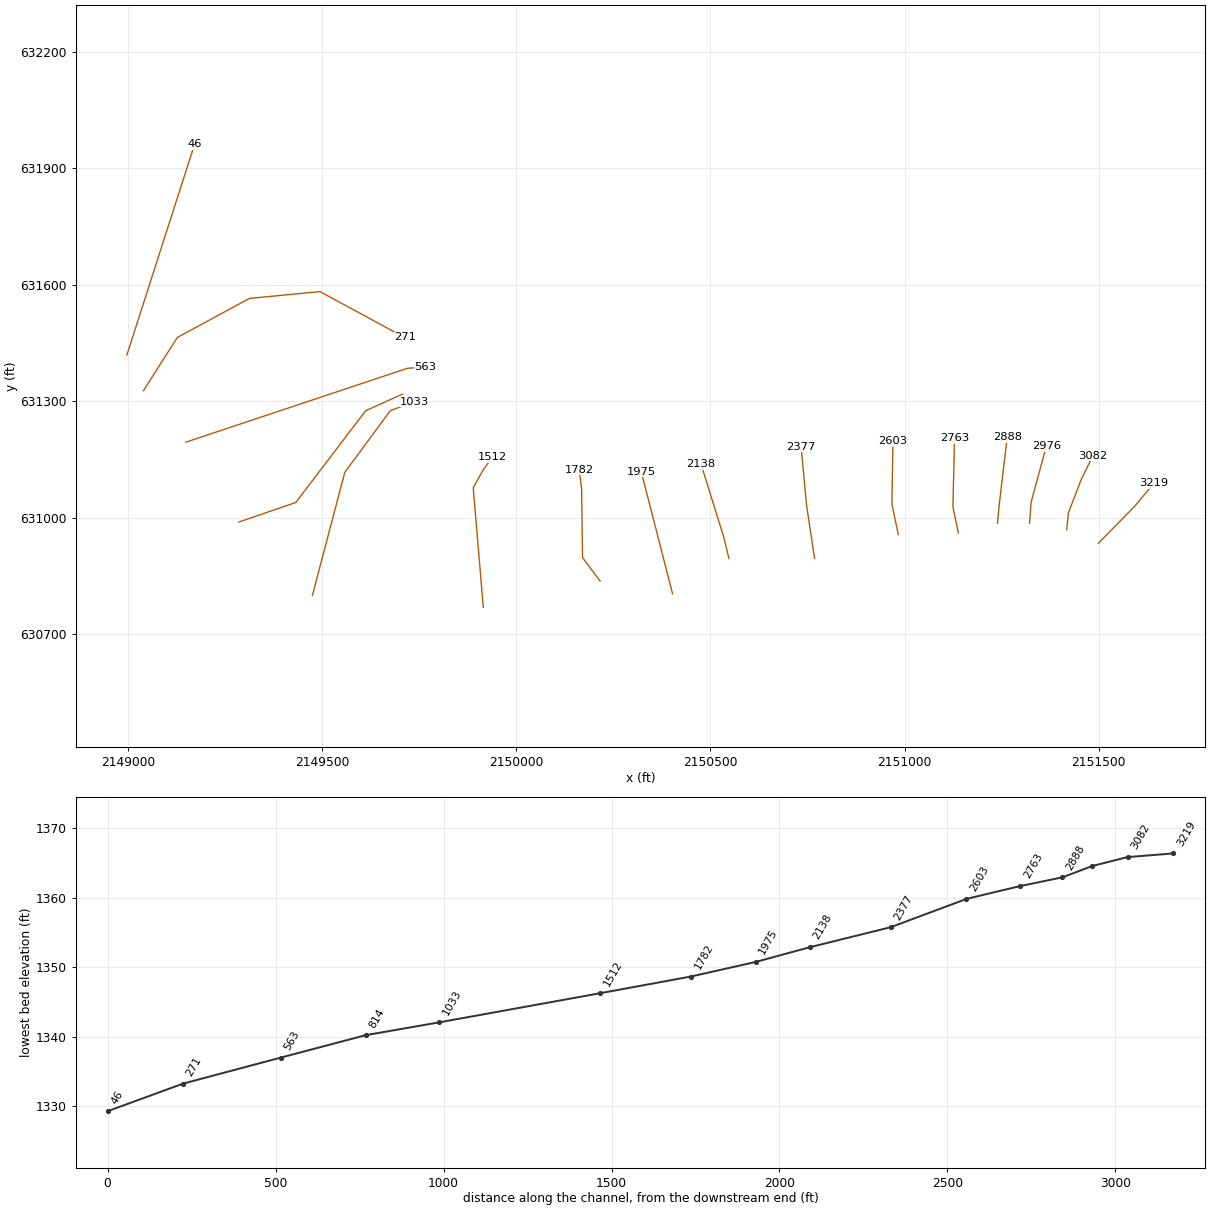
HEC-RAS study LFRFLIKANA.prj: LFRFLIKANA

--- LFRFLIKANA.g01 (geometry) --- (continued)

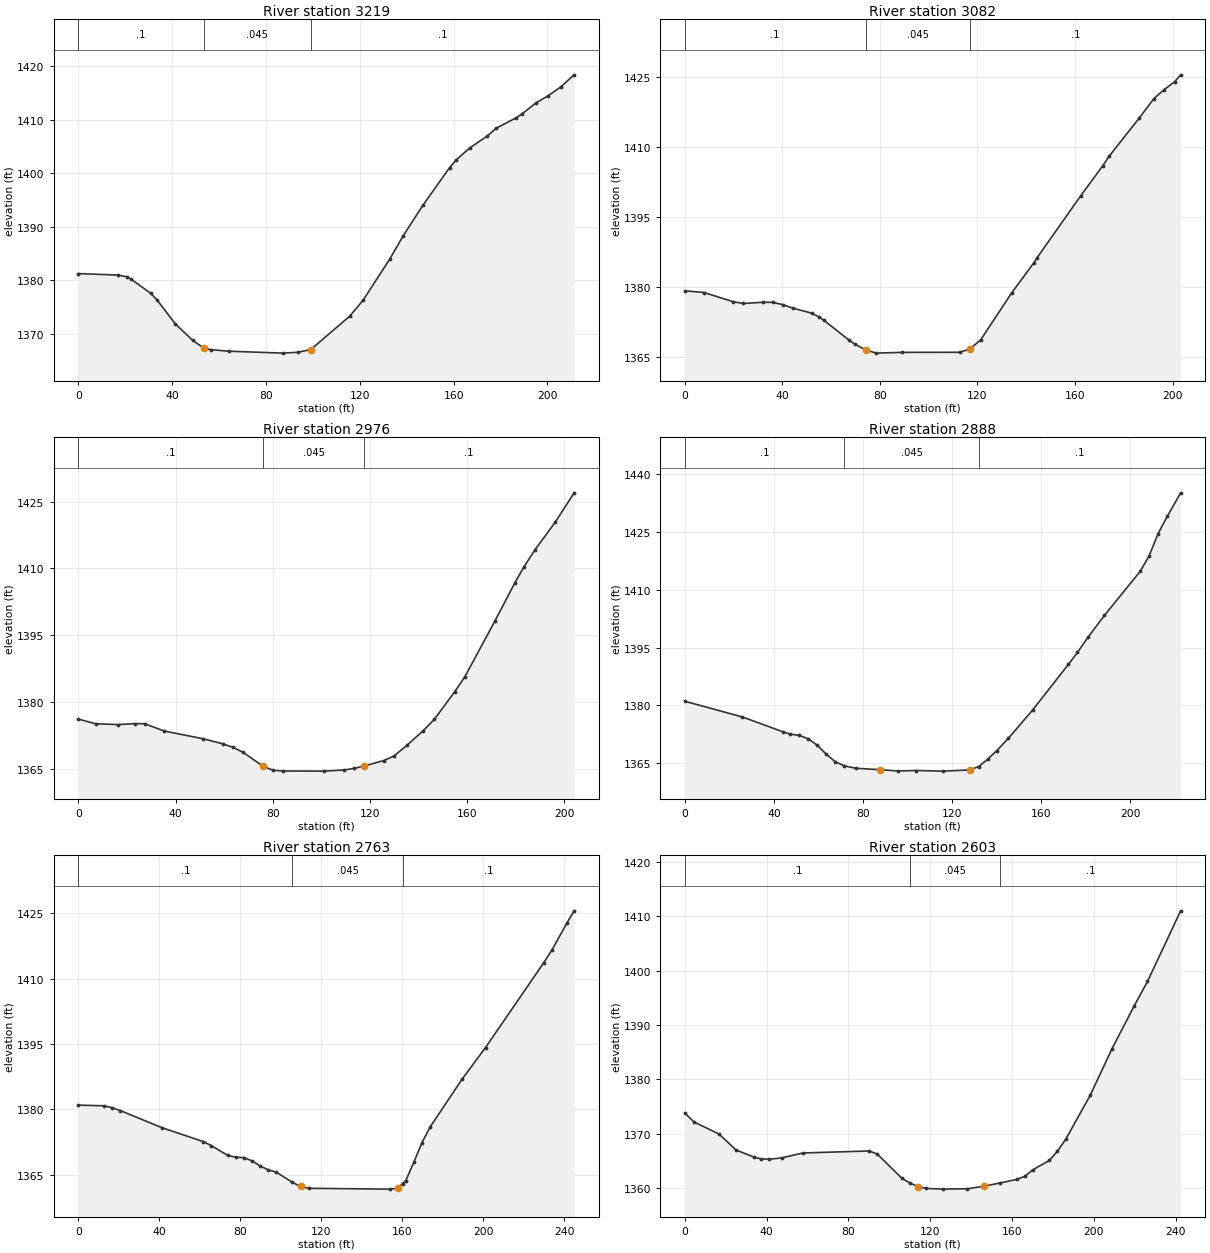
Type RM Length L Ch R = 1 ,3219    ,124.7,136.7,146.8
XS GIS Cut Line= 3
2151499.19185384630934.4427496452151592.86170316631029.949262675
2151642.45162339631089.640833318
#Sta/Elev= 30
       0 1381.21    16.8 1380.94    20.6 1380.63    22.4  1380.2    30.9 1377.52
    33.7 1376.21    41.4 1371.79    48.7 1368.77    53.5 1367.28    56.4    1367
    64.2 1366.71    87.1 1366.35    93.5 1366.51    99.1 1367.02   115.7 1373.25
   121.4 1376.23   132.7 1383.87   138.4 1388.19   146.9 1393.97   158.3 1401.02
   161.1 1402.46   166.8 1404.67   174.4 1406.94   178.2  1408.4   186.7 1410.33
     189    1411   195.2 1413.13   200.4 1414.48   205.6 1416.07   211.4 1418.36
#Mann= 3 ,-1,0
       0      .1       0    53.5    .045       0    99.1      .1       0
Bank Sta=53.5,99.1
XS Rating Curve= 0 ,0
Exp/Cntr(USF)=0,0
Exp/Cntr=0.3,0.1

Type RM Length L Ch R = 1 ,3082    ,102.7,105.6,108.3
XS GIS Cut Line= 4
2151417.46031865630969.3393601752151422.05197794631013.419289266
2151455.11192475631098.8241518782151484.49854415631159.434054378
#Sta/Elev= 30
       0 1379.15     7.9 1378.79    19.9 1376.81      24 1376.44      32  1376.7
      36 1376.69    40.1 1376.21    44.3 1375.44      52 1374.38    55.1 1373.54
    56.9  1372.9    67.4 1368.57    69.8 1367.72    74.1 1366.55    78.4 1365.82
    89.1 1365.98   112.7    1366   116.9 1366.71   121.3 1368.65   134.1 1378.76
     143 1385.05   144.4 1386.19   162.4 1399.53   171.4 1405.93   174.1 1408.02
   186.4 1416.16   192.3 1420.25   196.3 1422.09   200.8 1423.85   203.3 1425.36
#Mann= 3 ,-1,0
       0      .1       0    74.1    .045       0   116.9      .1       0
Bank Sta=74.1,116.9
XS Rating Curve= 0 ,0
Exp/Cntr(USF)=0,0
Exp/Cntr=0.3,0.1

Type RM Length L Ch R = 1 ,2976    ,84.7,88.1,91.2
XS GIS Cut Line= 3
2151321.74413315630986.0051028122151325.94318142631040.592730286
2151365.13429858631184.760054129
#Sta/Elev= 30
       0 1376.19     7.2 1375.15    16.4 1374.97    23.2 1375.18    27.3 1375.16
    35.3 1373.53    51.3  1371.8    59.5 1370.65    63.6 1369.88    67.8 1368.75
    76.1  1365.6    80.2 1364.72    84.4 1364.55     101 1364.53   109.2 1364.78
   113.4 1365.12   117.5 1365.66   125.8 1366.91     130 1367.95   135.3 1370.34
   141.8 1373.51   146.6 1376.17   154.9 1382.32     159  1385.6   171.4 1398.11
   179.7 1406.77   183.3 1410.23     188 1414.19   196.3 1420.35   204.1 1426.95
#Mann= 3 ,-1,0
       0      .1       0    76.1    .045       0   117.5      .1       0
Bank Sta=76.1,117.5
XS Rating Curve= 0 ,0
Exp/Cntr(USF)=0,0
Exp/Cntr=0.3,0.1

Type RM Length L Ch R = 1 ,2888    ,121,125.4,127.5
XS GIS Cut Line= 4
2151239.16285056630986.0051028122151243.36189883631030.794950996
2151257.35872638631149.7679852352151264.35714016631207.154978221
#Sta/Elev= 30
       0 1381.07    25.9 1376.98    44.2  1373.1    47.4 1372.52    51.4 1372.19
    55.4 1371.34    59.5 1369.61    63.5 1367.31    67.5 1365.37    71.6 1364.29
    76.7 1363.66    87.7 1363.28    95.7 1362.95   103.8 1363.07   115.9 1362.91
   127.9 1363.22     132 1364.11     136 1366.01     140 1368.21   145.2 1371.39
   156.1 1378.75   172.2 1390.63   176.3 1393.77   181.1 1397.77   188.4 1403.38
   204.5 1414.87   208.5  1418.9   212.5 1424.66   216.6 1429.09   222.6 1435.23
#Mann= 3 ,-1,0
       0      .1       0    71.6    .045       0     132      .1       0
Bank Sta=87.7,127.9
XS Rating Curve= 0 ,0
Exp/Cntr(USF)=0,0
Exp/Cntr=0.3,0.1

Type RM Length L Ch R = 1 ,2763    ,158,160.2,159
XS GIS Cut Line= 3
2151138.38569214630960.8108132082151124.38886459631027.995585484
2151128.58791285631204.355612709
#Sta/Elev= 30
       0 1380.95    12.6  1380.8    16.7 1380.37    20.8 1379.69    41.2 1375.79
    61.7 1372.58    65.8 1371.63    73.8 1369.41    77.8 1368.98    81.8 1368.89
    85.8 1368.16    89.8 1366.98    93.8  1366.1    97.8 1365.56   105.8 1363.21
   109.8 1362.27   113.8 1361.85   153.8 1361.66   157.8 1361.84   160.2 1362.93
   161.8 1363.62   165.8 1367.84   169.8 1372.32   173.8 1375.91   189.8 1387.03
   201.2 1394.18   229.9  1413.6   233.9 1416.48   241.5 1422.85     245 1425.57
#Mann= 3 ,-1,0
       0      .1       0   105.8    .045       0   160.2      .1       0
Bank Sta=109.8,157.8
XS Rating Curve= 0 ,0
Exp/Cntr(USF)=0,0
Exp/Cntr=0.3,0.1

Type RM Length L Ch R = 1 ,2603    ,223.6,225,229.4
XS GIS Cut Line= 3
2150983.78797324630956.7680681982150967.25799983631034.826275962
 2150970.0129954631197.371014483
#Sta/Elev= 30
       0 1373.81     4.5 1372.17    16.8 1369.93      25 1367.02    33.8  1365.7
    37.1 1365.38    41.3 1365.31    47.3 1365.55    57.7 1366.46    90.1 1366.83
    94.1 1366.26   106.1 1361.81   110.1 1360.92   114.1 1360.26   118.1 1359.94
   126.1 1359.81   138.2 1359.88   146.4 1360.35   154.2 1360.95   162.2 1361.59
   166.2 1362.16   170.2 1363.37   178.2 1365.08   182.2  1366.8   186.2 1368.96
   198.2 1377.07   208.9 1385.68   219.6 1393.45   226.2 1398.01   242.4 1411.01
#Mann= 3 ,-1,0
       0      .1       0   110.1    .045       0   154.2      .1       0
Bank Sta=114.1,146.4
XS Rating Curve= 0 ,0
Exp/Cntr(USF)=0,0
Exp/Cntr=0.3,0.1

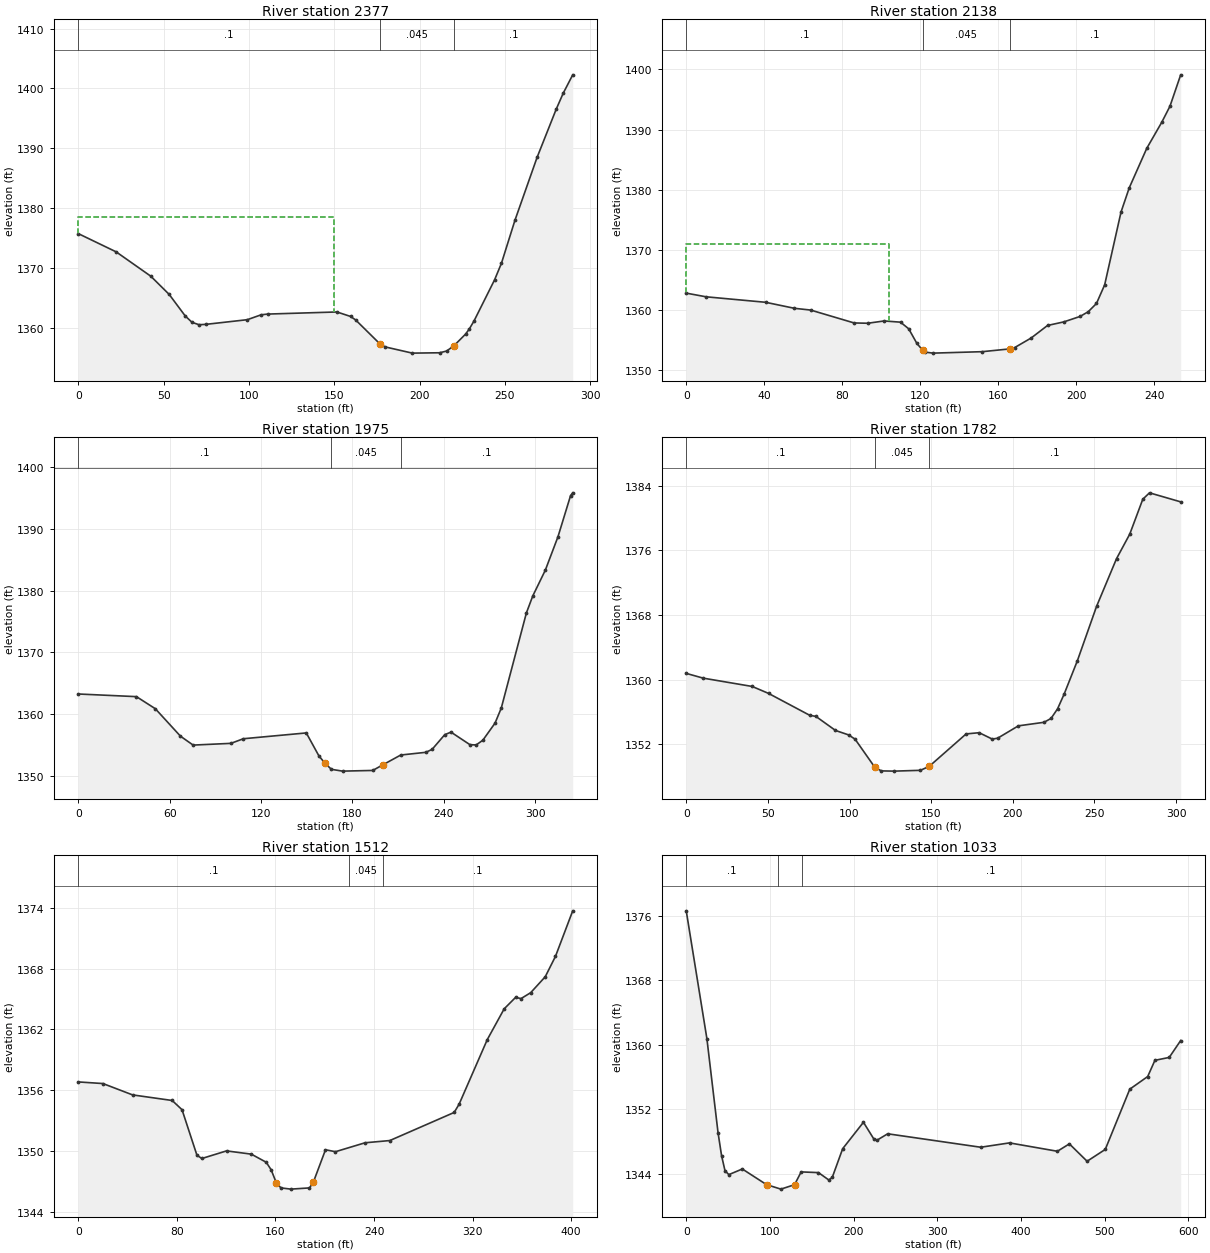
Type RM Length L Ch R = 1 ,2377    ,236.9,240,248
XS GIS Cut Line= 3
2150768.10565059630895.1968169262150747.44318382 631032.39559622
2150733.39270643631182.818354241
#Sta/Elev= 30
       0 1375.73    22.2 1372.68    42.5 1368.61    53.3 1365.56    62.7 1361.96
    66.7 1360.89    70.8  1360.5    74.8 1360.56    99.1 1361.34   107.2 1362.16
   111.2 1362.28   151.6 1362.63   159.6 1361.88   162.6 1361.29   176.61357.351
   179.7  1356.8   195.8 1355.75   211.8 1355.81   215.9  1356.1   220.2 1356.99
     227 1358.93   229.1 1359.75   231.9  1361.1     244    1368     248 1370.75
     256 1378.01   268.9 1388.46   280.1 1396.51   284.2 1399.18   289.8 1402.27
#Mann= 3 ,-1,0
       0      .1       0   176.6    .045       0   220.2      .1       0
#XS Ineff= 2 , 0
          149.92 1378.57
Permanent Ineff=
       F       F
Bank Sta=176.6,220.2
XS Rating Curve= 0 ,0
Exp/Cntr(USF)=0,0
Exp/Cntr=0.3,0.1

Type RM Length L Ch R = 1 ,2138    ,162.5,162.2,159.2
XS GIS Cut Line= 3
2150547.48744467630895.2803359962150533.63058539630951.967487604
 2150475.6837193631138.405230671
#Sta/Elev= 30
       0 1362.84    10.2 1362.23    40.7 1361.32    55.5 1360.32    63.8 1360.03
    86.1 1357.89    93.1 1357.84   101.5 1358.22   109.9 1358.02   114.1 1356.92
   118.3 1354.49   121.2 1353.39   122.5 1353.05   126.6 1352.88   151.8 1353.12
   165.9 1353.58   168.5 1353.81   176.9 1355.39   185.3 1357.47   193.7 1358.07
     202 1358.97   206.2 1359.76   210.4 1361.12   214.6 1364.21     223  1376.3
   227.2 1380.31   236.2 1386.88   243.9 1391.21   248.1 1393.87   253.6 1399.08
#Mann= 3 ,-1,0
       0      .1       0   121.2    .045       0   165.9      .1       0
#XS Ineff= 2 , 0
          103.77 1370.98
Permanent Ineff=
       F       F
Bank Sta=121.2,165.9
XS Rating Curve= 0 ,0
Exp/Cntr(USF)=0,0
Exp/Cntr=0.3,0.1

Type RM Length L Ch R = 1 ,1975    ,196.5,193.2,184.3
XS GIS Cut Line= 2
2150402.36610181630804.1551946782150321.72646165631118.563209737
#Sta/Elev= 30
       0 1363.25    38.2 1362.82    50.6 1360.86    67.1 1356.41    75.4 1354.97
   100.2 1355.25   108.4    1356   149.7 1356.94     158 1353.21   162.1 1351.99
   166.2 1351.04   173.5 1350.75   193.3 1350.86   199.8 1351.75   211.7 1353.36
   228.2  1353.8   232.3 1354.28   240.6 1356.66   244.7 1357.07   257.1 1355.04
   261.2 1354.99   265.6 1355.76   273.6 1358.53   277.7 1360.97   294.2  1376.4
   298.4 1379.15   306.6 1383.31   314.9 1388.72   323.2 1395.41   324.6 1395.85
#Mann= 3 ,-1,0
       0      .1       0   166.1    .045       0   211.7      .1       0
Bank Sta=162.1,199.8
XS Rating Curve= 0 ,0
Exp/Cntr(USF)=0,0
Exp/Cntr=0.3,0.1

Type RM Length L Ch R = 1 ,1782    ,268.6,270.3,271.3
XS GIS Cut Line= 4
2150215.89850303630836.8958288812150170.54878175 630897.36212393
2150168.02935279631076.2415801162150161.73078039631124.110730362
#Sta/Elev= 30
       0 1360.76    10.4 1360.17    40.4 1359.14    50.4 1358.28    75.6 1355.57
    79.4 1355.43    91.4 1353.69    99.4 1353.14   103.4 1352.61   115.4 1349.15
   119.4 1348.68   127.4 1348.65   143.4 1348.75   148.8 1349.24   171.4 1353.26
   179.4 1353.41   187.4 1352.62   190.7 1352.73   203.4 1354.26   219.1  1354.7
   223.4 1355.18   227.4 1356.37   231.4 1358.18   239.5 1362.31   251.3 1369.07
   263.5 1374.97   271.6 1378.01   279.6 1382.34   283.7 1383.13   302.8 1382.01
#Mann= 3 ,-1,0
       0      .1       0   115.4    .045       0   148.8      .1       0
Bank Sta=115.4,148.8
XS Rating Curve= 0 ,0
Exp/Cntr(USF)=0,0
Exp/Cntr=0.3,0.1

Type RM Length L Ch R = 1 ,1512    ,482.4,479.3,472.4
XS GIS Cut Line= 4
2149914.91847897630769.2590778392149888.94780653631077.095263078
2149914.21109544631122.6629427382149937.53653131631155.409218475
#Sta/Elev= 30
       0 1356.82      20 1356.66    44.1 1355.54    76.2 1354.99    84.2 1354.08
    96.3 1349.59   100.3 1349.27   120.3 1350.02   140.4  1349.7   152.5  1348.9
   156.5 1348.16   160.71346.869   164.5 1346.37   172.5 1346.25   187.6 1346.37
   190.71346.922   200.6 1350.13   208.7 1349.94   232.7 1350.82   252.8 1351.04
     305 1353.81     309 1354.62   331.9    1361   345.6 1364.03   354.8 1365.15
   359.3 1365.04   367.1 1365.62   378.9 1367.19   387.2  1369.2   401.2 1373.69
#Mann= 3 ,-1,0
       0      .1       0   219.5    .045       0     247      .1       0
Bank Sta=160.7,190.7
XS Rating Curve= 0 ,0
Exp/Cntr(USF)=0,0
Exp/Cntr=0.3,0.1

Type RM Length L Ch R = 1 ,1033    ,233.4,218.3,182.6
XS GIS Cut Line= 4
2149474.80350523630800.4173900412149558.21701104631117.141120083
2149675.41410066631275.772921369  2149736.961202631299.449765433
#Sta/Elev= 30
       0 1376.61    24.7 1360.73      38 1349.07    42.2 1346.22    46.3 1344.35
    50.9 1343.86      67 1344.56    95.9 1342.62   113.1 1342.06   129.4 1342.61
   137.3  1344.2     158 1344.11   170.4 1343.19   174.5 1343.53   186.9 1347.08
   211.7 1350.36   224.2 1348.27   228.3 1348.16   240.7 1348.93   351.8 1347.26
   386.2  1347.8   443.4 1346.76   457.7 1347.68   478.9 1345.52   500.6 1346.99
   529.9 1354.47   551.3 1356.04   559.9 1358.05     577 1358.41   590.7 1360.51
#Mann= 3 ,-1,0
       0      .1       0   109.1    .045       0   137.8      .1       0
Bank Sta=95.9,129.4
XS Rating Curve= 0 ,0
Exp/Cntr(USF)=0,0
Exp/Cntr=0.3,0.1

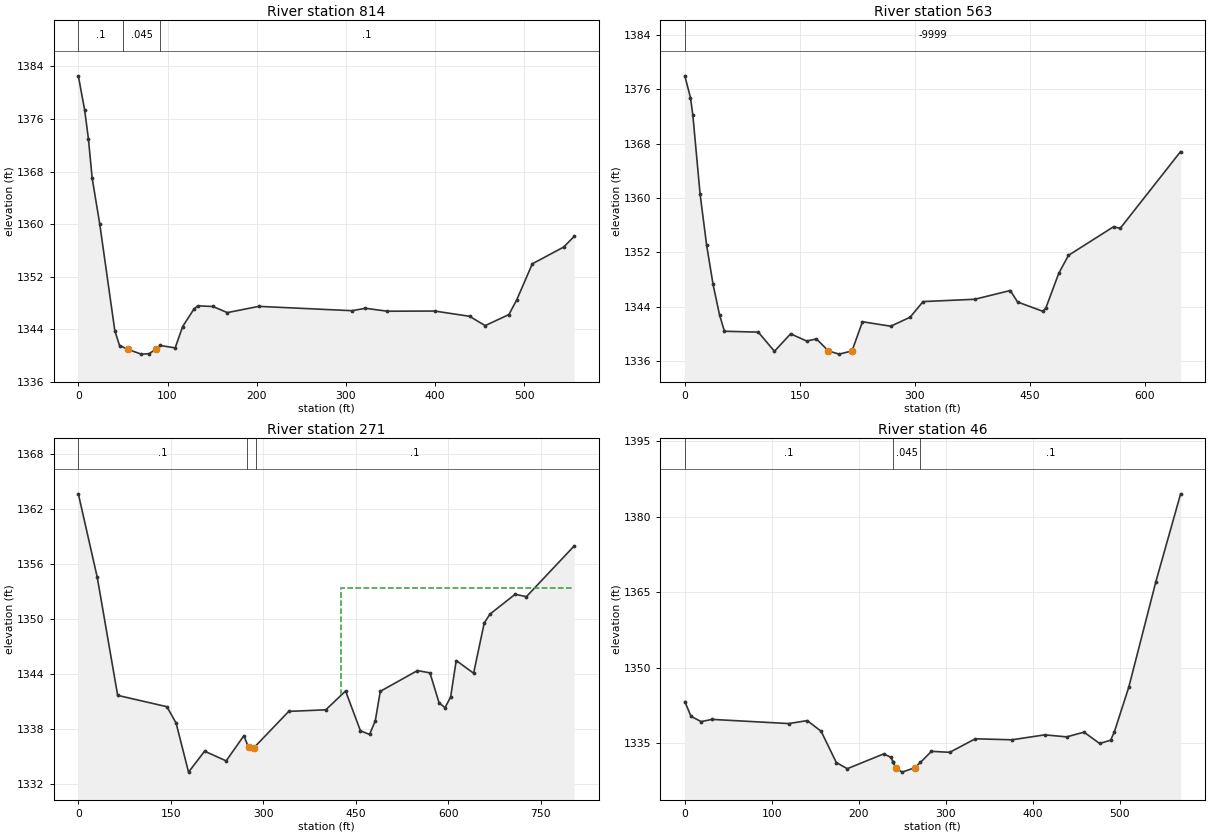
Type RM Length L Ch R = 1 ,814     ,249.8,251.6,247.5
XS GIS Cut Line= 4
2149285.50751293630989.1105410732149431.94702332631039.431726002
2149611.90357519 631275.621314042149706.87394897 631318.56551595
#Sta/Elev= 30
       0 1382.58     7.1 1377.36    11.3    1373    15.5 1367.02      24 1360.03
    40.9  1343.8    46.2 1341.53    55.7 1340.94    70.5 1340.22      79 1340.28
    87.1 1340.94    91.6 1341.54   108.6 1341.17     117 1344.42   129.7  1347.1
   133.9 1347.57   150.9 1347.47   167.1 1346.54   202.3 1347.49     307 1346.83
   321.8  1347.2   346.6 1346.75   399.4 1346.78   438.7 1345.98   456.2 1344.56
   482.8 1346.24   491.6 1348.48   509.1 1353.97   544.3 1356.52     556 1358.14
#Mann= 3 ,-1,0
       0      .1       0    50.3    .045       0    91.6      .1       0
Bank Sta=55.7,87.1
XS Rating Curve= 0 ,0
Exp/Cntr(USF)=0,0
Exp/Cntr=0.3,0.1

Type RM Length L Ch R = 1 ,563     ,287.4,291.7,293.7
XS GIS Cut Line= 3
2149149.15582723631194.8746162362149720.29794507631385.255322185
2149765.29702103631387.562967106
#Sta/Elev= 30
       0    1378     7.4 1374.79    10.5 1372.21      20 1360.54    28.5 1353.05
    36.9 1347.28    45.3 1342.81    51.7 1340.38    95.9 1340.25     117 1337.43
   138.1    1340   159.1 1338.94   171.8 1339.25  187.45 1337.48   201.4 1337.01
   218.2 1337.48   231.9 1341.78   268.8 1341.12   294.1 1342.45     311 1344.75
   378.4 1345.09   424.8 1346.38   434.3 1344.69     467 1343.33   471.2  1343.8
     488  1348.9   500.7 1351.56   559.7 1355.78   568.2 1355.53   647.1 1366.85
#Mann= 1 ,-1,0
       0   -9999       0
Bank Sta=187.45,218.2
XS Rating Curve= 0 ,0
Exp/Cntr(USF)=0,0
Exp/Cntr=0.3,0.1

Type RM Length L Ch R = 1 ,271     ,209.7,224.9,235.5
XS GIS Cut Line= 5
2149039.63867594631327.3438600482149126.73004741631464.201729499
2149312.39834729631564.9400414252149494.14874286631582.558962897
2149712.38726911631464.339498066
#Sta/Elev= 30
       0 1363.68    30.7 1354.55    63.8 1341.65   143.7 1340.41   158.6 1338.62
   178.8 1333.26   204.8 1335.55   239.8 1334.49   268.5 1337.24   276.1 1335.96
     285 1335.94   341.3  1339.9   401.4 1340.07   433.5 1342.13   457.6 1337.78
   472.4 1337.38   481.7 1338.87   489.8 1342.09   550.1 1344.36   570.4 1344.11
   585.1 1340.85   594.8  1340.3   603.9 1341.47     613 1345.46   641.2 1344.07
   658.4 1349.56   667.7 1350.53   708.5  1352.7   726.8 1352.44   804.3 1357.98
#Mann= 3 ,-1,0
       0      .1       0   274.2    .045       0   287.5      .1       0
#XS Ineff= 2 , 0
                          425.92         1353.39
Permanent Ineff=
       F       F
Bank Sta=276.1,285
XS Rating Curve= 0 ,0
Exp/Cntr(USF)=0,0
Exp/Cntr=0.3,0.1

Type RM Length L Ch R = 1 ,46      ,,,
XS GIS Cut Line= 2
2148996.99168241631419.4033790832149171.22761023631961.778479565
#Sta/Elev= 30
       0  1343.3     7.1 1340.38    18.7 1339.32    31.3 1339.76   119.5 1338.93
   140.7 1339.52   156.6 1337.41   174.1  1331.2   186.7 1329.97   228.7 1332.92
   237.1  1332.2   239.2 1331.32   239.2 1331.31   242.4 1330.14   249.7 1329.29
     264 1330.15   270.8 1331.23   283.4 1333.42   304.4 1333.22   333.8 1335.91
   375.8 1335.71   413.6 1336.69   438.8 1336.29   458.7 1337.23   476.6 1334.98
   489.2 1335.62   493.4 1337.19   510.2  1346.2   541.3 1367.13   569.7 1384.54
#Mann= 3 ,-1,0
       0      .1       0   239.2    .045       0   270.8      .1       0
Bank Sta=242.4,264
XS Rating Curve= 0 ,0
Exp/Cntr=0.3,0.1
LCMann Table=0

Chan Stop Cuts=-1
Use User Specified Reach Order=0
Composite Channel Slope=5